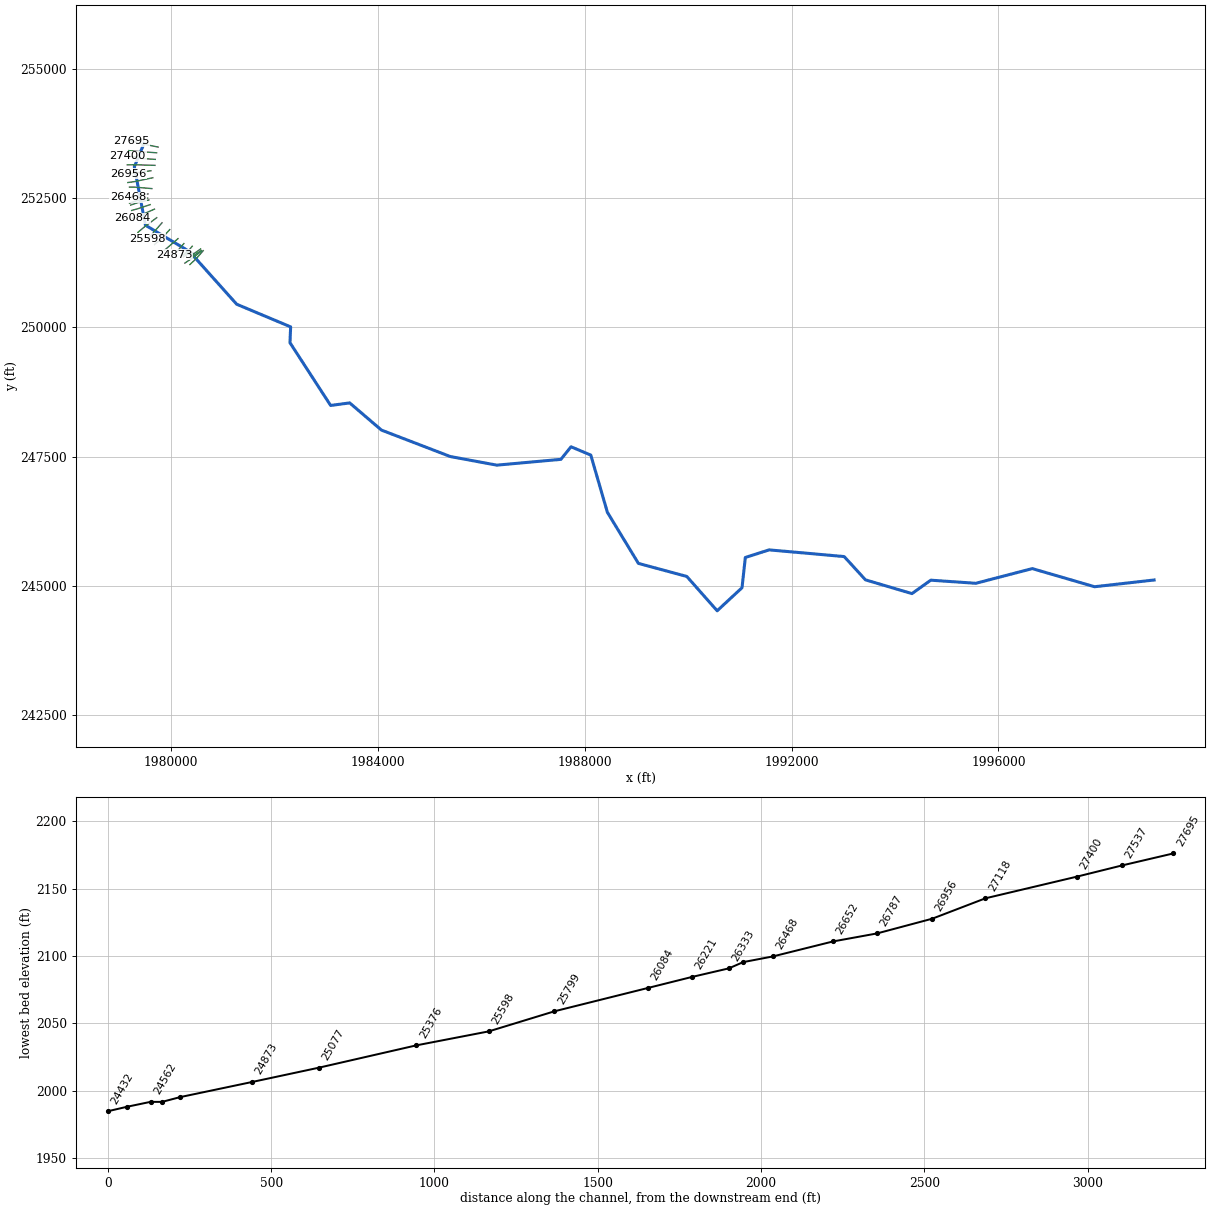
--- MADAMCK.prj (project) ---

Proj Title=MADAMCK
Current Plan=p01
Default Exp/Contr=0,0
English Units
Geom File=g01
Flow File=f01
Plan File=p01
BEGIN DESCRIPTION:
Stream Name: Madam Creek
Flood Zone: Detailed
Summers County, West Virginia
HEC-RAS Version: 5.0.7
Hydrology Method: Regression
Model Notes:
END DESCRIPTION:
DSS Export Rating Curves= 0
DSS Export Rating Curve Sorted= 0
DSS Export Volume Flow Curves= 0
DXF OffsetX= 0
DXF OffsetY= 0
DXF ScaleX= 0
DXF ScaleY= 0

--- MADAMCK.p01 (plan) ---

Plan Title=Floodplain
Program Version=5.07
Short Identifier=Floodplain
Geom File=g01
Flow File=f01
Subcritical Flow
K Sum by GR= 0
Std Step Tol= 0.01
Critical Tol= 0.01
Num of Std Step Trials= 20
Max Error Tol= 0.3
Flow Tol Ratio= 0.001
Split Flow NTrial= 30
Split Flow Tol= 0.02
Split Flow Ratio= 0.02
Log Output Level= 0
Friction Slope Method= 1
Unsteady Friction Slope Method= 2
Unsteady Bridges Friction Slope Method= 1
Parabolic Critical Depth
Global Vel Dist= 0 , 0 , 0
Global Log Level= 0
CheckData=True
Encroach Param=-1 ,5,5, 2
Encroach River=MADAMCK
Encroach Reach=Main
Encroach Node=27695
       1   270.6   293.3
Encroach Node=27537
       1   254.1     282
Encroach Node=27400
       1     210   233.5
Encroach Node=27118
       1   385.6   411.8
Encroach Node=26956
       1   273.7   309.3
Encroach Node=26787
       1   269.1   292.2
Encroach Node=26652
       1   236.9   263.9
Encroach Node=26468
       1   209.2   233.9
Encroach Node=26377
       1   186.4   221.4
Encroach Node=26333
       1   195.6   216.8
Encroach Node=26221
       1   170.7   194.9
Encroach Node=26084
       1   220.9     246
Encroach Node=25799
       1   247.9     281
Encroach Node=25598
       1     193   225.8
Encroach Node=25376
       1    95.6   122.3
Encroach Node=25077
       1   246.1   269.7
Encroach Node=24873
       1   178.6   206.2
Encroach Node=24652
       1   107.5   131.4
Encroach Node=24597
       1     219     249
Encroach Node=24562
       1     213   237.6
Encroach Node=24490
       1     182     211
Encroach Node=24432
       1     213     245
Encroach Node=24388
       1  224.06  240.58
Encroach Node=24280
       1   214.1   240.3
Encroach Node=24093
       1   122.7   154.2
Encroach Node=23906
       1   210.8   232.2
Encroach Node=23711
       1   179.9   201.7
Encroach Node=23527
       1   242.9   266.7
Encroach Node=23338
       1   218.4   252.1
Encroach Node=23170
       1   263.6   292.5
Encroach Node=23040
       1   269.2   292.4
Encroach Node=22906
       1   216.1   236.1
Encroach Node=22763
       1   181.2   203.7
Encroach Node=22694
       1   151.9   173.6
Encroach Node=22665
       1  152.17   171.3
Encroach Node=22556
       1     169     194
Encroach Node=22358
       1  137.24   161.3
Encroach Node=22217
       1     186   226.4
Encroach Node=22030
       1   135.6   168.7
Encroach Node=21785
       1     154   187.8
Encroach Node=21660
       1     185   234.4
Encroach Node=21553
       1     148   187.9
Encroach Node=21512
       1   159.4   187.5
Encroach Node=21360
       1     151   182.2
Encroach Node=21185
       1   189.9   227.5
Encroach Node=21046
       1   209.6   245.6
Encroach Node=20829
       1   138.9     180
Encroach Node=20620
       1   157.2   191.2
Encroach Node=20508
       1   112.4   135.5
Encroach Node=20414
       1   118.9   137.5
Encroach Node=20386
       1   122.3  142.83
Encroach Node=20290
       1   131.9   162.8
Encroach Node=20149
       1   180.2   203.7
Encroach Node=20017
       1   220.6   242.7
Encroach Node=19868
       1   163.2     185
Encroach Node=19785
       1   135.9     165
Encroach Node=19769
       1   138.3     163
Encroach Node=19688
       1   131.3   164.7
Encroach Node=19595
       1  148.75  177.25
Encroach Node=19561
       1  150.75   173.3
Encroach Node=19463
       1     159   182.3
Encroach Node=19347
       1   190.5     216
Encroach Node=19205
       1   162.9   189.1
Encroach Node=19068
       1   111.4   144.5
Encroach Node=18935
       1  126.79   163.5
Encroach Node=18857
       1   147.1   173.6
Encroach Node=18829
       1   146.8   173.6
Encroach Node=18709
       1   146.5   176.4
Encroach Node=18532
       1   144.5   173.5
Encroach Node=18300
       1   153.5     180
Encroach Node=18162
       1     210   236.7
Encroach Node=17925
       1   210.2     239
Encroach Node=17651
       1   195.8   222.8
Encroach Node=17459
       1   126.2   155.9
Encroach Node=17284
       1   143.3   182.1
Encroach Node=17126
       1   136.9   163.8
Encroach Node=17064
       1   193.3     223
Encroach Node=17025
       1   188.6   214.8
Encroach Node=16913
       1     135     180
Encroach Node=16777
       1   155.8   181.8
Encroach Node=16670
       1     195   229.3
Encroach Node=16492
       1   188.8   230.2
Encroach Node=16306
       1   258.3   287.6
Encroach Node=16122
       1   170.9   192.4
Encroach Node=16017
       1     125  151.45
Encroach Node=15979
       1   150.4  172.83
Encroach Node=15841
       1     171   200.6
Encroach Node=15662
       1   226.8     255
Encroach Node=15508
       1   202.3   232.3
Encroach Node=15256
       1   277.1   300.2
Encroach Node=15081
       1     170   201.5
Encroach Node=14943
       1     207   251.9
Encroach Node=14856
       1  227.75     263
Encroach Node=14806
       1   237.5   263.4
Encroach Node=14717
       1     108     158
Encroach Node=14471
       1    73.9   130.4
Encroach Node=14374
       1     120   170.8
Encroach Node=14209
       1   103.3   140.3
Encroach Node=14039
       1  100.75   132.9
Encroach Node=13845
       1   153.8     184
Encroach Node=13633
       1   288.9   318.2
Encroach Node=13510
       1     273   301.1
Encroach Node=13371
       1     325   365.6
Encroach Node=13242
       1   265.8   304.1
Encroach Node=13200
       1     264     300
Encroach Node=13069
       1   338.7   371.6
Encroach Node=12896
       1     295   348.3
Encroach Node=12773
       1     198   248.3
Encroach Node=12652
       1  186.55   212.4
Encroach Node=12618
       1   185.5   213.3
Encroach Node=12523
       1   193.6     224
Encroach Node=12407
       1   243.4     277
Encroach Node=12355
       1  240.04     287
Encroach Node=12334
       1   241.2   275.4
Encroach Node=12275
       1   226.5   270.2
Encroach Node=12122
       1   212.9   245.7
Encroach Node=11951
       1     235     273
Encroach Node=11863
       1     402   449.5
Encroach Node=11777
       1   390.1     440
Encroach Node=11625
       1   341.4   376.2
Encroach Node=11376
       1   224.1     268
Encroach Node=11223
       1   196.2     250
Encroach Node=11100
       1   227.6   286.8
Encroach Node=11010
       1   249.3   285.8
Encroach Node=10976
       1   259.2     283
Encroach Node=10885
       1   237.4  268.99
Encroach Node=10784
       1   108.3   135.1
Encroach Node=10686
       1   115.6     158
Encroach Node=10550
       1   141.6     184
Encroach Node=10440
       1     133   195.8
Encroach Node=10386
       1     160     220
Encroach Node=10342
       1  173.67   209.1
Encroach Node=10233
       1   191.1     225
Encroach Node=10062
       1     300     350
Encroach Node=9775
       1     470   549.4
Encroach Node=9565
       1   453.1   513.9
Encroach Node=9354
       1     380   458.5
Encroach Node=9133
       1     310     431
Encroach Node=8824
       1     270   341.8
Encroach Node=8521
       1   195.5     233
Encroach Node=8305
       1   171.8     207
Encroach Node=8204
       1   157.4   200.5
Encroach Node=8173
       1  152.35   195.2
Encroach Node=7964
       1   337.2   375.8
Encroach Node=7730
       1  143.95     225
Encroach Node=7692
       1   127.4     225
Encroach Node=7321
       1   214.1     295
Encroach Node=7015
       1   177.4     245
Encroach Node=6689
       1     188     268
Encroach Node=6591
       1   163.9     270
Encroach Node=6561
       1   170.4     270
Encroach Node=6474
       1   153.5     215
Encroach Node=6388
       1   147.8   197.5
Encroach Node=6329
       1   134.6     185
Encroach Node=6305
       1   131.7     176
Encroach Node=6224
       1   119.1     178
Encroach Node=6132
       1   134.8     187
Encroach Node=6067
       1     140     204
Encroach Node=6040
       1     159     206
Encroach Node=5946
       1     130   184.5
Encroach Node=5860
       1     132     188
Encroach Node=5775
       1   128.8     171
Encroach Node=5663
       1   155.6     198
Encroach Node=5562
       1     139   183.2
Encroach Node=5539
       1   141.7   178.6
Encroach Node=5530
       1   137.6   177.3
Encroach Node=5522
       1   145.1   184.6
Encroach Node=5504
       1   145.1     186
Encroach Node=5411
       1   194.3   235.9
Encroach Node=5222
       1   279.9   320.2
Encroach Node=5056
       1   367.7   413.1
Encroach Node=4860
       1   440.7   489.7
Encroach Node=4714
       1     321   366.8
Encroach Node=4549
       1   234.2   282.9
Encroach Node=4346
       1     132   178.1
Encroach Node=4233
       1     149  204.96
Encroach Node=4188
       1     151   199.5
Encroach Node=4059
       1     205     256
Encroach Node=3868
       1   216.8     287
Encroach Node=3787
       1   209.8     303
Encroach Node=3763
       1     213     285
Encroach Node=3705
       1     254     315
Encroach Node=3529
       1     273   317.4
Encroach Node=3284
       1   255.8   301.7
Encroach Node=3170
       1   199.8   245.9
Encroach Node=3036
       1     210     265
Encroach Node=2902
       1     215     263
Encroach Node=2744
       1     275   316.2
Encroach Node=2550
       1     290   354.6
Encroach Node=2419
       1   233.5   282.7
Encroach Node=2169
       1   197.4     246
Encroach Node=1983
       1   168.7     215
Encroach Node=1785
       1   205.5   252.5
Encroach Node=1615
       1     230   275.8
Encroach Node=1378
       1   263.3   315.8
Encroach Node=1202
       1     314   383.6
Encroach Node=1044
       1     350     396
Encroach Node=911
       1   335.8     387
Encroach Node=788
       1  314.25     365
Encroach Node=714
       1     309     359
Encroach Node=641
       1   461.5     533
Encroach Node=582
       1     540  600.85
Encroach Node=506
       1     515   588.5
Mapping Interval=1HOUR
Computation Time Step Use Courant=        0
Computation Time Step Use Time Series=    0
Computation Time Step Count To Double=0
Computation Time Step Max Doubling=0
Computation Time Step Max Halving=0
Computation Time Step Residence Courant=0
Run HTab= 0
Run UNet= 0
Run Sediment= 0
Run PostProcess= 0
Run WQNet= 0
Run RASMapper= 0
UNET Theta= 0
UNET Theta Warmup= 0
UNET ZTol= 0
UNET ZSATol= 0
UNET MxIter= 0
UNET Max Iter WO Improvement= 0
UNET MaxInSteps= 0
UNET DtIC= 0
UNET DtMin= 0
UNET MaxCRTS= 0
UNET WFStab= 0
UNET SFStab= 0
UNET WFX= 1
UNET SFX= 1
UNET 1D Methodology=Finite Difference
UNET DSS MLevel= 1
UNET Pardiso=0
UNET DZMax Abort= 0
UNET Use Existing IB Tables= 0
UNET Froude Reduction=False
UNET Froude Limit= 0
UNET Froude Power= 0
UNET D1 Cores= 0
UNET D2 Coriolis=0
UNET D2 Cores= 0
UNET D2 Theta= 1
UNET D2 Theta Warmup= 1
UNET D2 Z Tol= 0.01
UNET D2 Volume Tol= 0.01
UNET D2 Max Iterations= 20
UNET D2 Equation= 0
UNET D2 RampUpFraction=0.1
UNET D2 TimeSlices= 1
UNET D2 BCVolumeCheck=0
UNET D1D2 MaxIter= 0
UNET D1D2 ZTol=0.01
UNET D1D2 QTol=0.1
UNET D1D2 MinQTol=1
Write IC File= 0
Write IC File at Fixed DateTime=0
Write IC File at Sim End=0
Echo Input=False
Echo Parameters=False
Echo Output=False
Write Detailed= 0
HDF Write Warmup=0
HDF Write Time Slices=0
HDF Flush=0
HDF Face Node Velocities=0
HDF Compression= 1
HDF Chunk Size= 1
HDF Spatial Parts= 1
HDF Use Max Rows=0
HDF Fixed Rows= 1
Calibration Method= 0
Calibration Iterations= 20
Calibration Max Change=0.05
Calibration Tolerance=0.2
Calibration Maximum=1.5
Calibration Minimum=0.5
Calibration Optimization Method= 1
WQ AD Non Conservative
WQ ULTIMATE=-1
WQ Max Comp Step=1HOUR
WQ Output Interval=15MIN
WQ Output Selected Increments= 0
WQ Output face flow=0
WQ Output face velocity=0
WQ Output face area=0
WQ Output face dispersion=0
WQ Output cell volume=0
WQ Output cell surface area=0
WQ Output cell continuity=0
WQ Output cumulative cell continuity=0
WQ Output face conc=0
WQ Output face dconc_dx=0
WQ Output face courant=0
WQ Output face peclet=0
WQ Output face adv mass=0
WQ Output face disp mass=0
WQ Output cell mass=0
WQ Output cell source sink temp=0
WQ Output nsm pathways=0
WQ Output nsm derived pathways=0
WQ Output MaxMinRange=-1
WQ Daily Max Min Mean=-1
WQ Daily Range=0
WQ Daily Time=0
WQ Create Restart=0
WQ Fixed Restart=0
WQ System Summary=0
WQ Write To DSS=0
WQ Use Fixed Temperature=0
Sorting and Armoring Iterations= 10
XS Update Threshold= 0.02
Bed Roughness Predictor= 0
Hydraulics Update Threshold= 0.02
Energy Slope Method= 1
Volume Change Method= 1
Sediment Retention Method= 0
XS Weighting Method= 0
Number of US Weighted Cross Sections= 1
Number of DS Weighted Cross Sections= 1
Upstream XS Weight=0
Main XS Weight=1
Downstream XS Weight=0
Number of DS XS's Weighted with US Boundary= 1
Upstream Boundary Weight= 1
Weight of XSs Associated with US Boundary= 0
Number of US XS's Weighted with DS Boundary= 1
Downstream Boundary Weight= 0.5
Weight of XSs Associated with DS Boundary= 0.5
Percentile Method= 0
Sediment Output Level= 3
Mass or Volume Output= 0
Output Increment Type= 1
Profile and TS Output Increment= 1
XS Output Flag= 0
XS Output Increment= 10
Write Gradation File= 0
Read Gradation Hotstart= 0
Write HDF5 File= 1
Write Binary Output= 1
Write DSS Sediment File= 0
SV Curve= 0
Specific Gage Flag= 0

--- MADAMCK.f01 (steady flow) ---

Flow Title=Flows
Program Version=5.07
Number of Profiles= 7
Profile Names=01pct,FW,10pct,04pct,02pct,0_2pct,01plus
River Rch & RM=MADAMCK,Main            ,27695
     439     439     229     307     370     616     649
River Rch & RM=MADAMCK,Main            ,26084
     490     490     257     343     414     686     725
River Rch & RM=MADAMCK,Main            ,24280
     557     557     294     391     471     778     823
River Rch & RM=MADAMCK,Main            ,22217
     640     640     340     451     542     892     946
River Rch & RM=MADAMCK,Main            ,21046
     730     730     390     516     620    1016    1080
River Rch & RM=MADAMCK,Main            ,14717
     852     852     457     604     724    1181    1260
River Rch & RM=MADAMCK,Main            ,12896
     992     992     536     705     844    1372    1467
River Rch & RM=MADAMCK,Main            ,12122
    1411    1411     772    1010    1204    1938    2087
River Rch & RM=MADAMCK,Main            ,7964
    1924    1924    1065    1385    1646    2627    2845
River Rch & RM=MADAMCK,Main            ,4549
    2209    2209    1230    1595    1892    3008    3266
Boundary for River Rch & Prof#=MADAMCK,Main            , 1
Up Type= 0
Dn Type= 3
Dn Slope=0.02216
Boundary for River Rch & Prof#=MADAMCK,Main            , 2
Up Type= 0
Dn Type= 3
Dn Slope=0.02216
Boundary for River Rch & Prof#=MADAMCK,Main            , 3
Up Type= 0
Dn Type= 3
Dn Slope=0.02216
Boundary for River Rch & Prof#=MADAMCK,Main            , 4
Up Type= 0
Dn Type= 3
Dn Slope=0.02216
Boundary for River Rch & Prof#=MADAMCK,Main            , 5
Up Type= 0
Dn Type= 3
Dn Slope=0.02216
Boundary for River Rch & Prof#=MADAMCK,Main            , 6
Up Type= 0
Dn Type= 3
Dn Slope=0.02216
DSS Import GetInterval= 0
DSS Import GetPeak= 0
DSS Import FillOption= 0

--- MADAMCK.g01 (geometry) ---

Geom Title=Geometry
Program Version=5.07

River Reach=MADAMCK         ,Main
Reach XY= 30
1979485.21121687253555.2813383341979297.87563351253104.511898682
1979511.92310566251975.5587760061980366.41516313 251463.23237285
 1981275.8772549250446.6527131051982318.88796419250008.639481515
 1982305.6081351249702.5692275021983092.03011867248488.464044169
  1983460.136994248538.3284457771984073.36706674248012.769457504
1985404.96414107247501.050664693 1986302.1952863247334.611036941
1987541.68296477247446.3631100061987738.29740095247689.852780506
1988120.24184701247528.3944420221988440.83963105246422.382218346
1989040.24460018 245434.385506691989975.27685085245182.040210843
1990562.34785518244518.0146360251991042.78258985244963.637432441
1991107.01868185 245548.707128421991566.21986318 245695.84233284
1993017.09655458245566.6454127581993429.24238384245116.049201086
1994327.50469497244850.2118062681994691.21984679245109.760171682
1995562.50419343245049.6274179371996653.02563441245333.718713254
 1997857.4526875244983.0242046861999006.92619807 245113.23446393

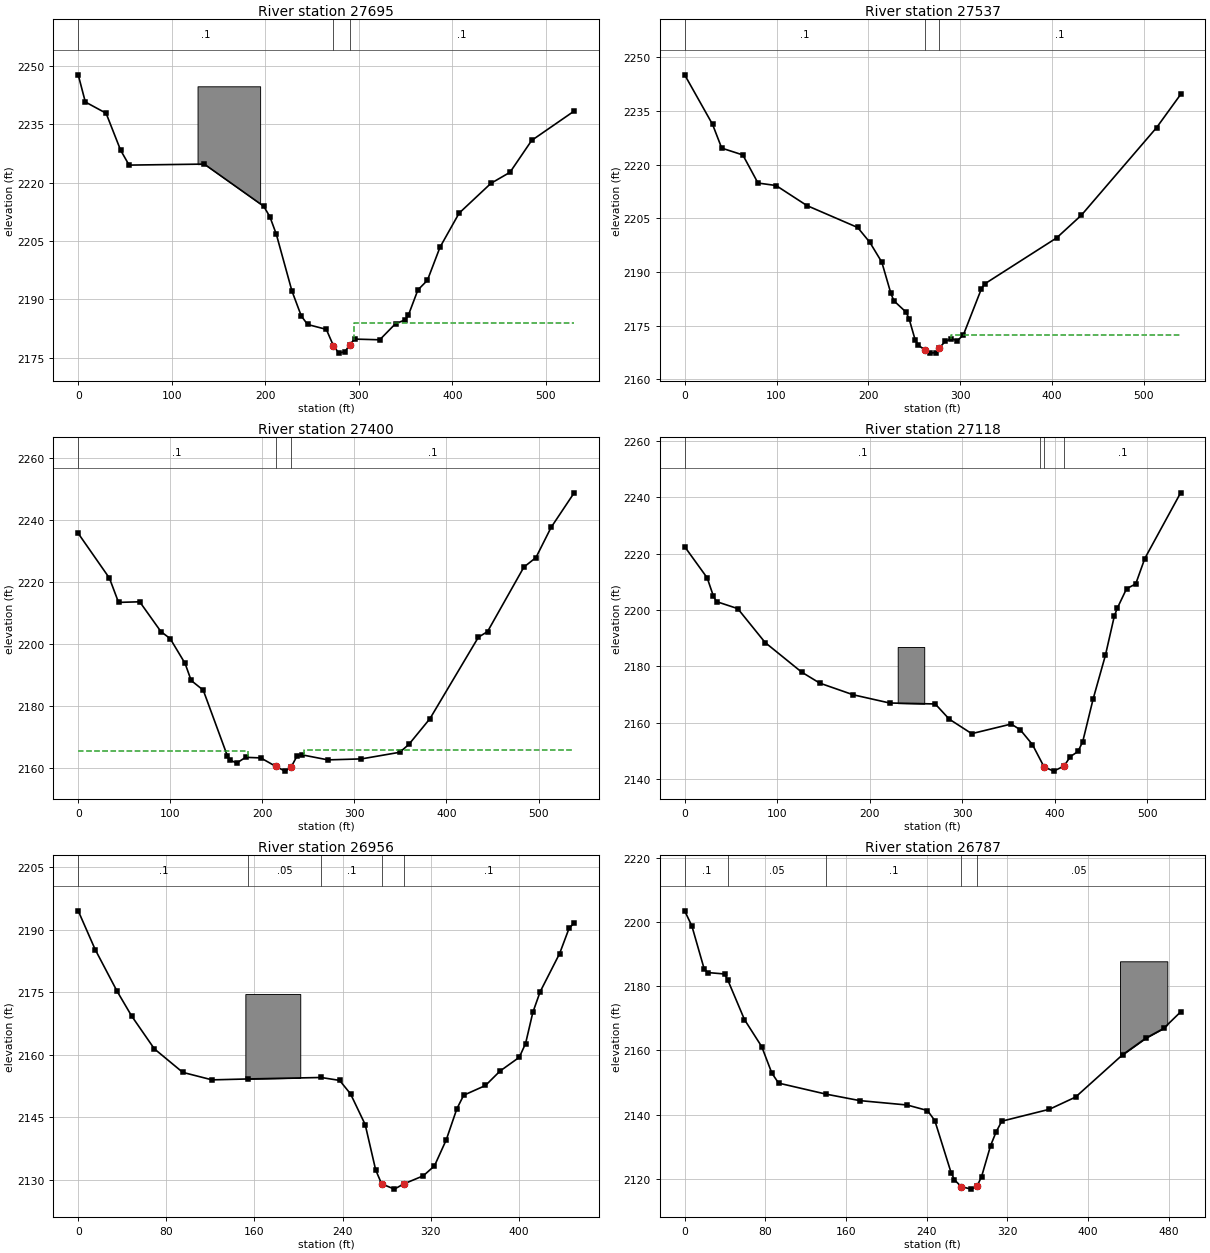
Type RM Length L Ch R = 1 ,27695   ,155.9,157.5,159
Node Name=I
XS GIS Cut Line= 3
     1979758.297      253485.737     1979451.006      253548.236
     1979241.804       253604.66
#Sta/Elev= 30
       0 2247.76     7.6 2240.78    29.8 2237.89    45.3  2228.4    54.4 2224.55
   134.8 2224.81   198.4 2213.96     205 2211.24   211.8  2206.8   228.5 2192.21
   238.5 2185.78   245.2 2183.58   265.3 2182.32   272.9 2178.11   278.7 2176.21
   285.4  2176.6  290.09 2178.32   295.5 2179.82   322.4 2179.64   339.4 2183.81
   349.6 2184.74     353 2185.94   363.2 2192.45   373.4 2194.94   386.9 2203.46
   407.3  2212.2   441.3 2219.86   461.7  2222.7   484.9  2230.9   530.3 2238.44
#Mann= 3 ,-1 , 0
       0      .1       0   272.9    .045       0  290.09      .1       0
#XS Ineff= 2 , 0
                             295            2184
Permanent Ineff=
       F       F
#Block Obstruct= 1 ,-1
   127.6  194.51 2244.81
Bank Sta=272.9,290.09
XS Rating Curve= 0 ,0
Exp/Cntr=0.3,0.1

Type RM Length L Ch R = 1 ,27537   ,135,137,136.3
XS GIS Cut Line= 3
     1979728.783      253375.493     1979410.207      253398.063
     1979190.589      253418.028
#Sta/Elev= 30
       0 2245.15    30.4 2231.25    40.3 2224.64    63.3 2222.73    79.8 2214.87
    99.5 2214.17   133.1 2208.56   188.3 2202.43   201.5  2198.3   214.6 2192.73
   224.5 2183.96   227.8  2181.9   240.9 2178.77   244.2 2176.96   250.8 2171.08
   254.1 2169.57   261.32168.156   267.3 2167.27   273.8 2167.44     277 2168.68
   283.8 2170.59   290.3 2171.28   296.9 2170.77   303.4 2172.37   322.9 2185.19
   326.5 2186.63     405 2199.53   431.9 2205.88   513.7 2230.37   539.9 2239.66
#Mann= 3 ,-1 , 0
       0      .1       0   261.3    .045       0     277      .1       0
#XS Ineff= 2 , 0
                          290.37         2172.44
Permanent Ineff=
       F       F
Bank Sta=261.3,277
XS Rating Curve= 0 ,0
Exp/Cntr=0.3,0.1

Type RM Length L Ch R = 1 ,27400   ,273.9,281.3,283.7
XS GIS Cut Line= 4
     1979702.741      253247.889     1979438.852      253264.382
1979380.44861617253292.487427236 1979171.4917779253307.419553499
#Sta/Elev= 30
       0 2235.76    33.9 2221.31    43.8 2213.48    66.8 2213.67    89.8 2204.07
    99.9 2201.78   116.1 2193.77   122.7 2188.27   135.8 2185.16   162.1 2163.88
   165.4 2162.56     172 2161.59   181.8 2163.47   198.3 2163.29   214.7 2160.53
   224.6 2159.02   231.2 2160.29   237.7 2163.89   243.2 2164.27   271.3 2162.65
   307.7 2162.97   349.2  2165.1   359.1 2167.62   382.1 2175.97   434.7 2202.25
   444.6 2204.05   484.1 2224.87   497.2 2227.95   513.7  2237.7   538.7 2248.84
#Mann= 3 , 0 , 0
       0      .1       0   214.7    .045       0   231.2      .1       0
#XS Ineff= 2 , 0
          184.23 2165.48  245.07         2165.93
Permanent Ineff=
       F       F
Bank Sta=214.7,231.2
XS Rating Curve= 0 ,0
Exp/Cntr=0.3,0.1

Type RM Length L Ch R = 1 ,27118   ,160.6,162.8,165.3
XS GIS Cut Line= 3
     1979696.665      253132.438     1979279.131      253144.591
     1979161.075      253141.987
#Sta/Elev= 30
       0 2222.52    24.3 2211.46    31.1 2204.91    34.4 2203.02    57.3 2200.54
    86.9 2188.51   126.3 2178.02   145.9  2174.1   182.1 2169.95   221.4 2167.04
   270.7  2166.7   285.8 2161.32   310.1 2156.16   352.8 2159.57   362.6 2157.52
   375.7 2152.29   388.32144.344   398.7 2142.86     4102144.698   416.6    2148
   424.9 2149.83     430 2153.28   441.3 2168.49   454.5 2183.91   464.3 2198.05
   467.6 2200.84   477.4 2207.59   487.3  2209.3   497.1 2218.32   535.8 2241.63
#Mann= 4 ,-1 , 0
       0      .1       0   384.4      .1       0   388.3    .045       0
     410      .1       0
#Block Obstruct= 1 ,-1
  230.15   258.8 2186.91
Bank Sta=388.3,410
XS Rating Curve= 0 ,0
Exp/Cntr=0.3,0.1

Type RM Length L Ch R = 1 ,26956   ,166.6,168.6,168
XS GIS Cut Line= 3
      1979618.54      253028.271     1979290.415      252983.132
      1979172.36      252968.375
#Sta/Elev= 30
       0 2194.53    15.4 2185.24    35.3 2175.22    48.5 2169.28    69.1  2161.4
    94.9 2155.75   121.5 2153.95   154.5 2154.17   220.5 2154.52   237.3 2153.82
   247.2 2150.59   260.5 2143.22     270 2132.35   275.42128.992     287 2127.72
   295.42128.954   313.2 2130.91   323.4  2133.3   334.1 2139.56   343.7 2146.99
   349.9 2150.26   369.7  2152.6   382.9 2156.06   400.4 2159.37   406.1 2162.67
   412.7 2170.15   419.3 2175.08     437 2184.27   445.7 2190.41   450.2 2191.57
#Mann= 5 ,-1 , 0
       0      .1       0   154.5     .05       0   220.5      .1       0
   275.4    .045       0   295.4      .1       0
#Block Obstruct= 1 ,-1
  151.73  201.56 2174.55
Bank Sta=275.4,295.4
XS Rating Curve= 0 ,0
Exp/Cntr=0.3,0.1

Type RM Length L Ch R = 1 ,26787   ,137.4,135.2,132.6
XS GIS Cut Line= 3
     1979654.999      252892.855     1979298.228      252817.334
      1979172.36      252799.972
#Sta/Elev= 30
       0 2203.49     7.2  2198.7    19.3 2185.43    22.7 2184.27    39.5 2183.82
    42.8 2181.89    59.3  2169.6    76.4 2161.18    86.4 2152.96    93.1 2149.83
   140.1  2146.4   173.6 2144.38   220.6 2143.01   240.7 2141.29     248 2138.15
   264.1 2121.97   267.5  2119.7   274.12117.606   283.9 2116.81   289.82117.704
   294.3 2120.65   303.3 2130.36   308.8 2134.65   314.4 2137.97   361.6 2141.68
   387.5 2145.47   434.3  2158.7   457.3 2163.86   474.8 2166.85   491.7    2172
#Mann= 5 ,-1 , 0
       0      .1       0    42.8     .05       0   140.1      .1       0
   274.1    .045       0   289.8     .05       0
#Block Obstruct= 1 ,-1
  431.65  478.52 2187.77
Bank Sta=274.1,289.8
XS Rating Curve= 0 ,0
Exp/Cntr=0.3,0.1

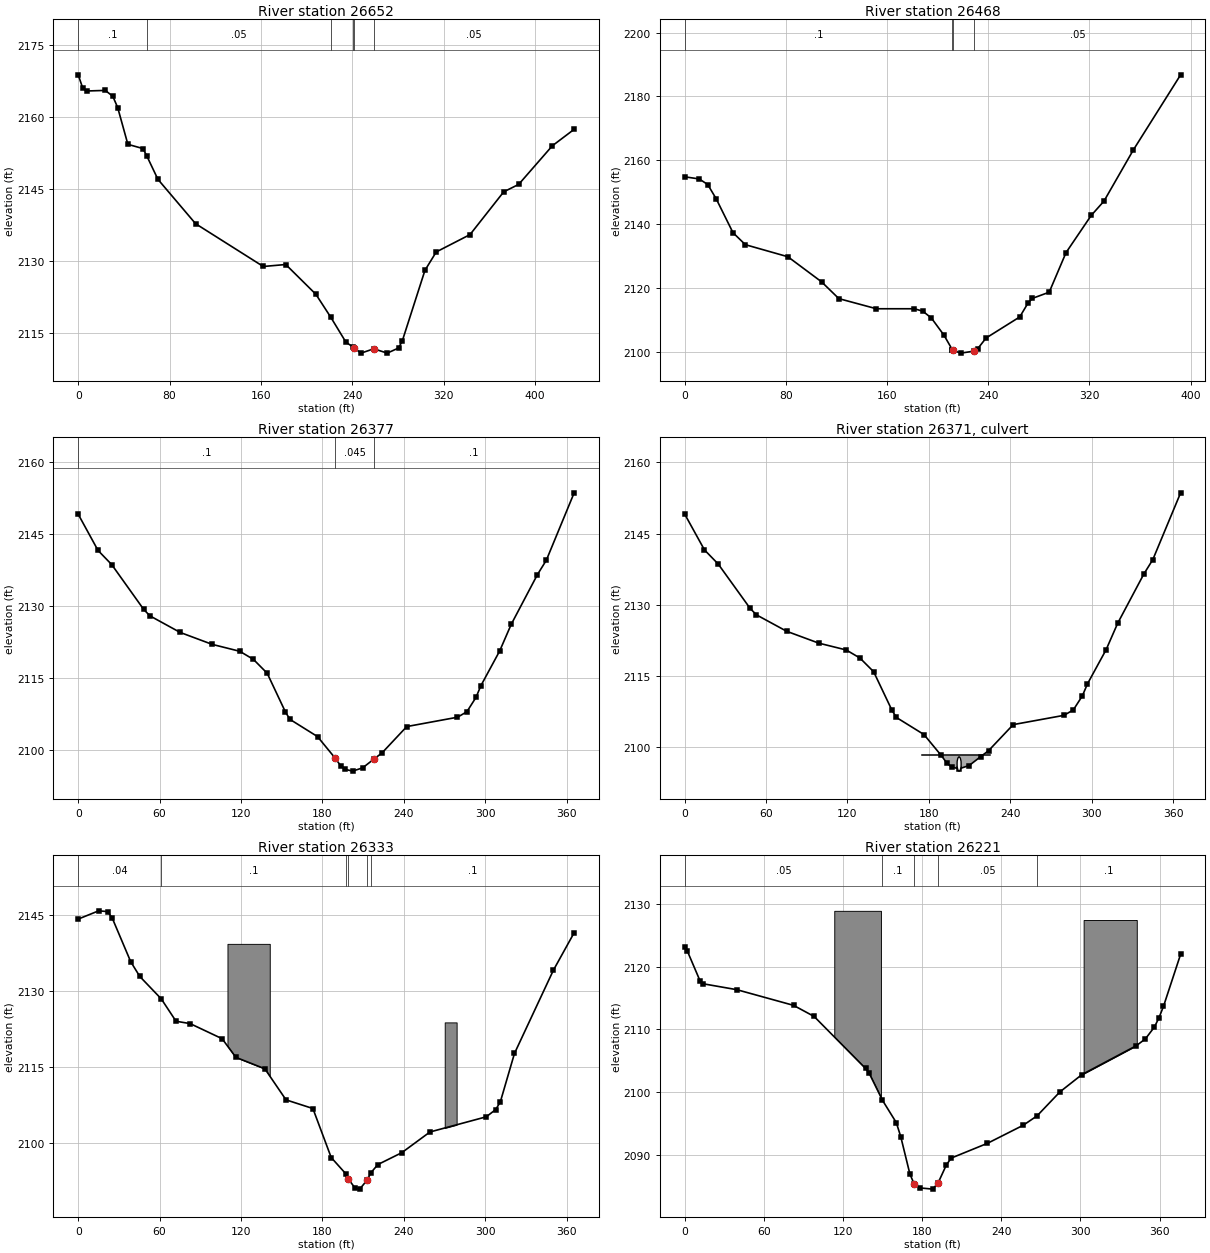
Type RM Length L Ch R = 1 ,26652   ,172.3,184.2,183.9
XS GIS Cut Line= 3
     1979636.769      252682.785     1979294.756      252712.299
      1979203.61      252712.299
#Sta/Elev= 30
       0 2168.84       4 2166.04     7.3 2165.47    23.7 2165.59    30.3 2164.37
    34.6    2162    43.5 2154.35    56.7 2153.47      60 2151.97    69.8 2147.06
   102.8 2137.81   162.1 2128.89   181.8  2129.3   208.2 2123.09   221.3 2118.28
   234.5 2113.11   241.1 2112.04   241.92111.863   247.7 2110.83   258.9 2111.73
   270.7 2110.83   280.6  2111.9   283.9  2113.4   303.7 2128.08   313.6 2131.92
   343.2 2135.54   372.7 2144.45   385.8    2146   415.3 2154.05   434.4 2157.48
#Mann= 6 ,-1 , 0
       0      .1       0      60     .05       0   221.3      .1       0
   241.1      .1       0   241.9    .045       0   258.9     .05       0
Bank Sta=241.9,258.9
XS Rating Curve= 0 ,0
Exp/Cntr=0.3,0.1

Type RM Length L Ch R = 1 ,26468   ,88.8,90.8,92.6
XS GIS Cut Line= 3
     1979562.117      252580.354     1979314.721      252535.216
     1979175.832      252513.514
#Sta/Elev= 30
       0 2154.86    11.5 2154.19    18.2 2152.45    24.9 2147.99    38.2 2137.37
      48 2133.62    81.6 2129.85   108.2 2122.01   121.9 2116.75   151.6 2113.58
   181.6 2113.58   188.3 2112.81     195  2110.7     205 2105.32   211.6 2100.76
   211.6 2100.75   212.3 2100.56   218.3  2099.7   228.92100.335   231.6 2101.05
   238.3 2104.43   264.9 2111.02   271.6 2115.46   274.9 2116.83   288.2 2118.76
   301.5 2131.14   321.4 2142.77   331.5 2147.25   354.7 2163.25   392.1 2186.76
#Mann= 4 ,-1 , 0
       0      .1       0   211.6      .1       0   212.3    .045       0
   228.9     .05       0
Bank Sta=212.3,228.9
XS Rating Curve= 0 ,0
Exp/Cntr=0.5,0.3

Type RM Length L Ch R = 1 ,26377   ,41.9,43.8,44.8
XS GIS Cut Line= 4
     1979555.123      252499.929      1979378.04      252458.263
     1979337.675      252446.544     1979203.561      252400.971
#Sta/Elev= 30
       0  2149.1    14.6 2141.55    24.7 2138.59    48.3 2129.23    52.9 2127.89
    75.2 2124.43    98.8 2121.94   119.1  2120.5   129.2  2118.8   139.3 2115.92
   152.8 2107.81   156.1 2106.29   176.4  2102.7   189.1 2098.31   193.4 2096.65
   196.8 2095.86   202.3 2095.49   209.7 2096.18   218.2 2098.05     224  2099.3
   242.2 2104.79   279.6 2106.74   286.5 2107.88   293.2 2110.86   296.9 2113.35
   310.7 2120.57   319.2 2126.12   338.5 2136.49   345.1 2139.51   365.6 2153.57
#Mann= 3 , 0 , 0
       0      .1       0   189.1    .045       0   218.2      .1       0
#XS Ineff= 2 , 0
           181.1  2098.3     231          2098.3
Permanent Ineff=
       F       F
Bank Sta=189.1,218.2
XS Rating Curve= 0 ,0
Exp/Cntr=0.5,0.3

Type RM Length L Ch R = 2 ,26371   ,,,
BEGIN DESCRIPTION:
Unnamed Road
Road deck based on LiDAR and bridge opening determined by imagery
END DESCRIPTION:
Bridge Culvert--1,0,-1,-1, 0
Deck Dist Width WeirC Skew NumUp NumDn MinLoCord MaxHiCord MaxSubmerge Is_Ogee
20,12,2.6,0, 2, 2, , , 0.98, 0, 0,0,,
     175     225
  2098.3  2098.3
                
     175     250
  2098.3  2098.3
                
BR Coef=-1 , 1 , 0 ,, 0 ,,,0.8,0,1.2,0,
WSPro=,,,, 1 ,,,, 0 ,,,, 0 ,,,,-1 ,-1 ,-1 , 0 , 0 , 0 , 0 , 0
Culvert=1,3,,23,0.019,0.9,1,2,3,2095,202.3,2090.8,206.5,Culvert #1  , 0 ,17
   202.3   206.5
BC Culvert Barrel=1,Barrel1,0
Culvert Bottom n=0.019
BC Design=,, 0 ,, 0 ,,,,,,
BC Use User HTab Curves=0
BC User HTab FreeFlow(D)= 0

Type RM Length L Ch R = 1 ,26333   ,112.4,112.4,112.8
XS GIS Cut Line= 4
     1979578.561      252463.471     1979401.478      252421.804
     1979361.113      252410.085     1979226.998      252364.512
#Sta/Elev= 30
       0 2144.25    15.1 2145.88    21.8 2145.73    25.2 2144.37    38.7 2135.82
    45.4  2132.9    61.2 2128.48    72.1 2124.05    82.5 2123.58   106.1 2120.59
   116.2 2116.91   137.6 2114.64   153.2  2108.5     173 2106.79   186.5  2097.1
   197.1 2093.93   199.22092.842   204.1 2091.04   207.5 2090.85   213.22092.711
   215.6 2094.04   220.9 2095.71   238.5 2098.05   259.3 2102.15   300.8 2105.15
   307.8 2106.59   311.2 2108.12   321.6 2117.68   350.3 2134.14   365.6 2141.55
#Mann= 6 ,-1 , 0
       0     .04       0    61.2      .1       0   197.1      .1       0
   199.2    .045       0   213.2      .1       0   215.6      .1       0
#XS Ineff= 2 , 0
             194  2093.5     218          2093.5
Permanent Ineff=
       F       F
#Block Obstruct= 2 ,-1
  110.03   141.2 2139.35  270.18  278.96 2123.82
Bank Sta=199.2,213.2
XS Rating Curve= 0 ,0
Exp/Cntr=0.5,0.3

Type RM Length L Ch R = 1 ,26221   ,133.3,136.3,136.7
XS GIS Cut Line= 3
     1979604.652      252372.889     1979357.256      252291.292
     1979246.144      252260.042
#Sta/Elev= 30
       0 2123.14       2  2122.5    11.8 2117.66      14 2117.27    39.5 2116.33
    82.5 2113.83    98.1 2112.06   137.1 2103.76   139.7 2103.06   149.9 2098.69
   160.4 2095.12   163.8 2092.86   170.7 2086.92   173.8  2085.4   178.6  2084.7
     188 2084.51   192.1 2085.51   198.4 2088.39     202 2089.46   229.5 2091.82
   256.6  2094.7   267.1  2096.2   284.4 2100.02     301 2102.77   342.3 2107.39
   349.2 2108.48     356 2110.36   359.4  2111.8   362.9 2113.66   375.9 2121.98
#Mann= 5 ,-1 , 0
       0     .05       0   149.9      .1       0   173.8    .045       0
   192.1     .05       0   267.1      .1       0
#Block Obstruct= 2 ,-1
  113.38  148.75 2128.91  302.38  342.67 2127.44
Bank Sta=173.8,192.1
XS Rating Curve= 0 ,0
Exp/Cntr=0.3,0.1

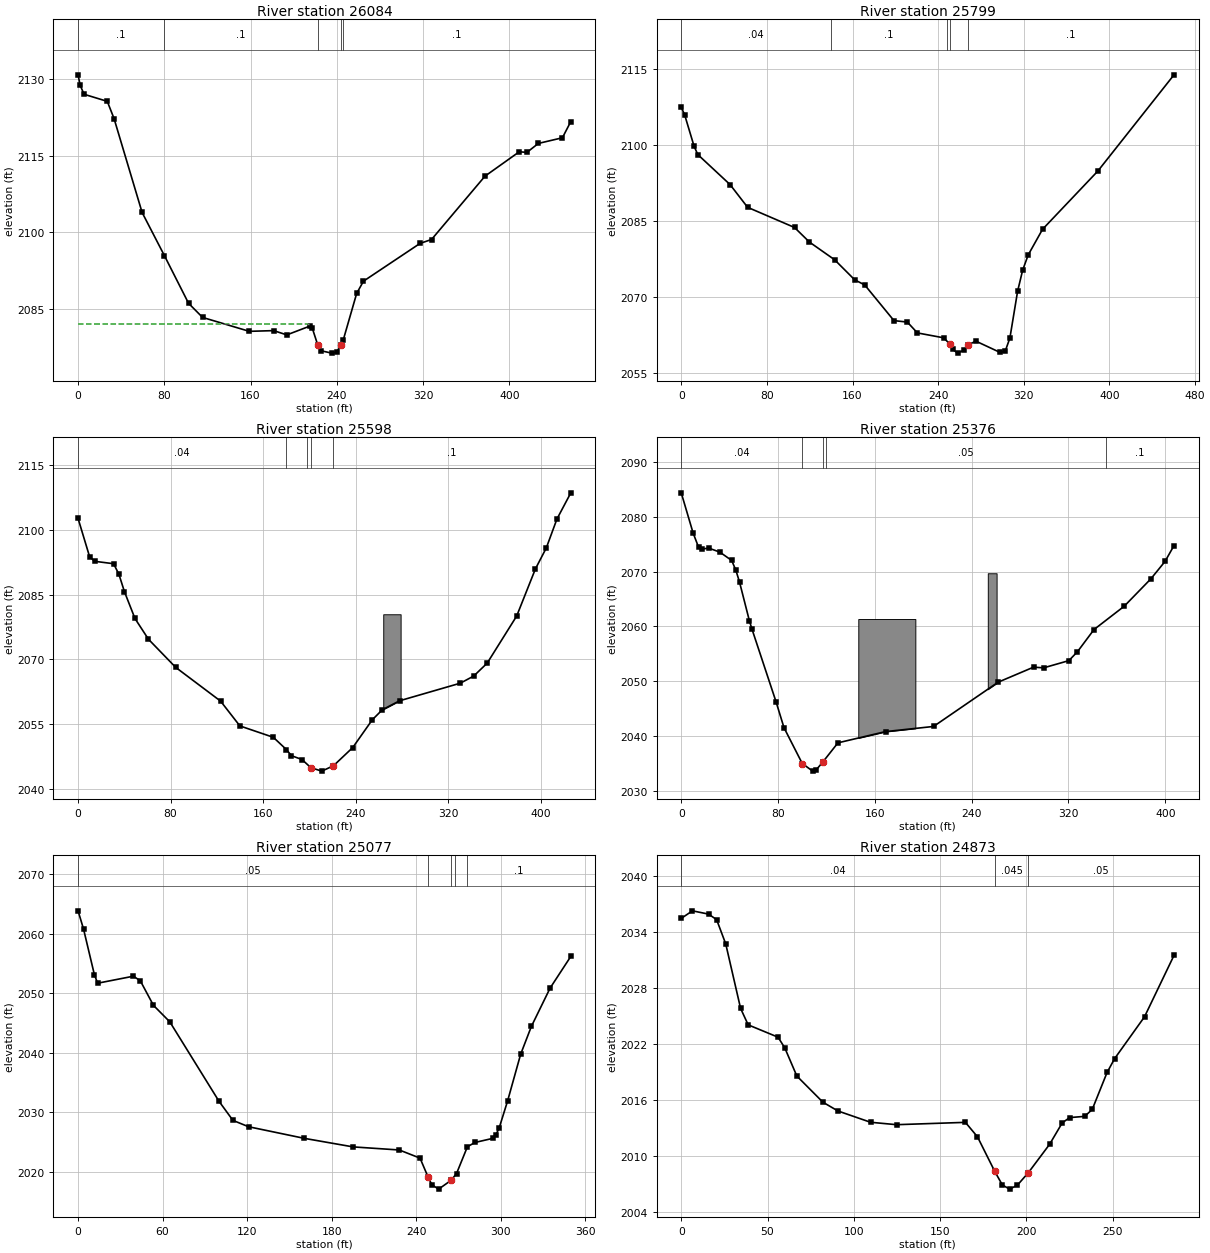
Type RM Length L Ch R = 1 ,26084   ,280.6,285.2,284.7
XS GIS Cut Line= 3
     1979687.117      252286.084     1979430.172      252172.368
     1979266.978      252106.396
#Sta/Elev= 30
       0 2130.89       2  2128.8     5.6 2127.07    27.1 2125.68    33.4 2122.29
    59.4 2103.86    80.1 2095.38   102.5 2086.02   115.5 2083.25   158.8 2080.52
   181.4 2080.66   193.6 2079.82     215 2081.55   217.3  2081.1   222.22077.905
   224.9 2076.73   235.2 2076.24   239.8 2076.43   244.12077.852     246 2078.86
   258.4 2087.97   264.7 2090.37   317.2 2097.79   327.8 2098.55   377.4 2110.99
   409.2 2115.78   416.3 2115.66   426.9 2117.42   449.2 2118.53     457 2121.72
#Mann= 5 ,-1 , 0
       0      .1       0    80.1      .1       0   222.2    .045       0
   244.1      .1       0     246      .1       0
#XS Ineff= 2 , 0
          214.54 2082.01
Permanent Ineff=
       F       F
Bank Sta=222.2,244.1
XS Rating Curve= 0 ,0
Exp/Cntr=0.3,0.1

Type RM Length L Ch R = 1 ,25799   ,198.4,201.2,203
XS GIS Cut Line= 3
     1979730.519      252120.285     1979490.936      251940.598
     1979367.672      251837.299
#Sta/Elev= 30
       0 2107.52     3.2 2106.02      12 2099.82    15.5 2098.18    45.6 2092.26
      62 2087.77   105.8 2083.79   119.8  2080.9   143.3 2077.41     162 2073.46
   171.4 2072.44   198.7  2065.4   211.2 2065.11   220.6 2062.97   245.2    2062
   250.62060.829   253.4 2059.75   258.1 2058.98   264.3 2059.61     2682060.637
   275.3 2061.34   297.9 2059.11   302.6 2059.35     307 2061.96   314.2  2071.2
   318.9 2075.34   324.1 2078.37   337.5 2083.43   389.2 2094.94   460.3 2113.93
#Mann= 5 ,-1 , 0
       0     .04       0     140      .1       0     248      .1       0
   250.6    .045       0     268      .1       0
Bank Sta=250.6,268
XS Rating Curve= 0 ,0
Exp/Cntr=0.3,0.1

Type RM Length L Ch R = 1 ,25598   ,224.1,221.9,224
XS GIS Cut Line= 3
      1979832.95      252021.327     1979633.297      251794.764
     1979545.623      251707.091
#Sta/Elev= 30
       0  2102.7      10  2093.8    14.4 2092.75    30.7 2092.19    35.3 2089.76
    40.1  2085.7    49.2 2079.48    60.9 2074.65    84.4 2068.14   123.2 2060.31
   139.9 2054.55   168.8 2051.91   180.1 2049.07   184.5 2047.64   193.6 2046.75
   201.32044.856   210.7 2044.06   220.82045.303   237.5 2049.54   254.4 2055.98
     263 2058.29   277.9 2060.38   330.5 2064.47   342.1 2066.13   353.7 2069.12
   379.2 2080.05   395.4 2090.99   404.8 2095.85     414 2102.56     426 2108.64
#Mann= 5 ,-1 , 0
       0     .04       0   180.1      .1       0   198.2      .1       0
   201.3    .045       0   220.8      .1       0
#Block Obstruct= 1 ,-1
  263.84  278.86 2080.46
Bank Sta=201.3,220.8
XS Rating Curve= 0 ,0
Exp/Cntr=0.3,0.1

Type RM Length L Ch R = 1 ,25376   ,300.3,298.8,297.5
XS GIS Cut Line= 3
     1979982.255      251890.251     1979807.777      251696.674
     1979692.325      251606.396
#Sta/Elev= 30
       0 2084.32     9.8 2077.01    14.3 2074.43    17.2 2074.07    22.6 2074.27
    31.9 2073.53    41.7 2072.01    45.2 2070.19    48.2 2068.05    56.4 2060.96
    58.4 2059.55    78.4 2046.25    84.9 2041.58     1002035.058   108.6 2033.67
   111.4 2033.87   117.32035.414   129.5 2038.82   168.8 2040.86   208.5  2041.8
   261.8 2049.85   291.1 2052.59   299.5 2052.47   320.3 2053.78   327.4  2055.4
   341.1 2059.44   366.1 2063.69   388.1 2068.67   399.8 2071.84   407.2 2074.72
#Mann= 5 ,-1 , 0
       0     .04       0     100    .045       0   117.3     .05       0
     120     .05       0   350.6      .1       0
#Block Obstruct= 2 ,-1
   146.3  193.46 2061.35  253.31   260.6 2069.68
Bank Sta=100,117.3
XS Rating Curve= 0 ,0
Exp/Cntr=0.3,0.1

Type RM Length L Ch R = 1 ,25077   ,201.3,203.8,202.9
XS GIS Cut Line= 2
     1980141.978      251714.903     1979876.353      251487.472
#Sta/Elev= 30
       0 2063.86     3.9 2060.79    11.6 2053.12    13.9 2051.69    39.3 2052.87
    44.2 2052.09    53.5 2047.97    65.1  2045.2     100 2031.85   109.9 2028.63
     121 2027.56   160.5 2025.61   195.2 2024.17     228 2023.65   242.7 2022.28
   248.42019.102   251.1  2017.8   255.9 2017.07   264.72018.546   268.6 2019.69
   276.3 2024.19   281.6 2024.91   294.6 2025.62   296.5 2026.17   298.9 2027.39
   304.8 2031.87   314.1 2039.75   321.7 2044.42     335 2050.87   349.7  2056.2
#Mann= 5 ,-1 , 0
       0     .05       0   248.4    .045       0   264.7     .05       0
   267.7     .05       0   276.3      .1       0
Bank Sta=248.4,264.7
XS Rating Curve= 0 ,0
Exp/Cntr=0.3,0.1

Type RM Length L Ch R = 1 ,24873   ,218.7,221,223.4
XS GIS Cut Line= 2
     1980255.693      251620.285     1980069.061      251404.139
#Sta/Elev= 30
       0 2035.48     6.5 2036.29    15.8 2035.94    20.5 2035.35    25.8 2032.74
    34.4 2025.84    38.8 2024.08    56.1 2022.76      60 2021.62      67  2018.6
    82.1  2015.8    90.8 2014.86   109.7 2013.65   124.8 2013.39   164.7 2013.64
   171.7 2012.09   181.72008.391   186.1 2006.94   190.3 2006.49   194.8 2006.91
   201.22008.255   213.5 2011.29   220.8 2013.58   225.1 2014.15   233.8 2014.28
   238.2 2015.02   246.8 2018.98   251.2 2020.47   268.5 2024.94   285.6 2031.52
#Mann= 3 ,-1 , 0
       0     .04       0   181.7    .045       0   201.2     .05       0
Bank Sta=181.7,201.2
XS Rating Curve= 0 ,0
Exp/Cntr=0.3,0.1

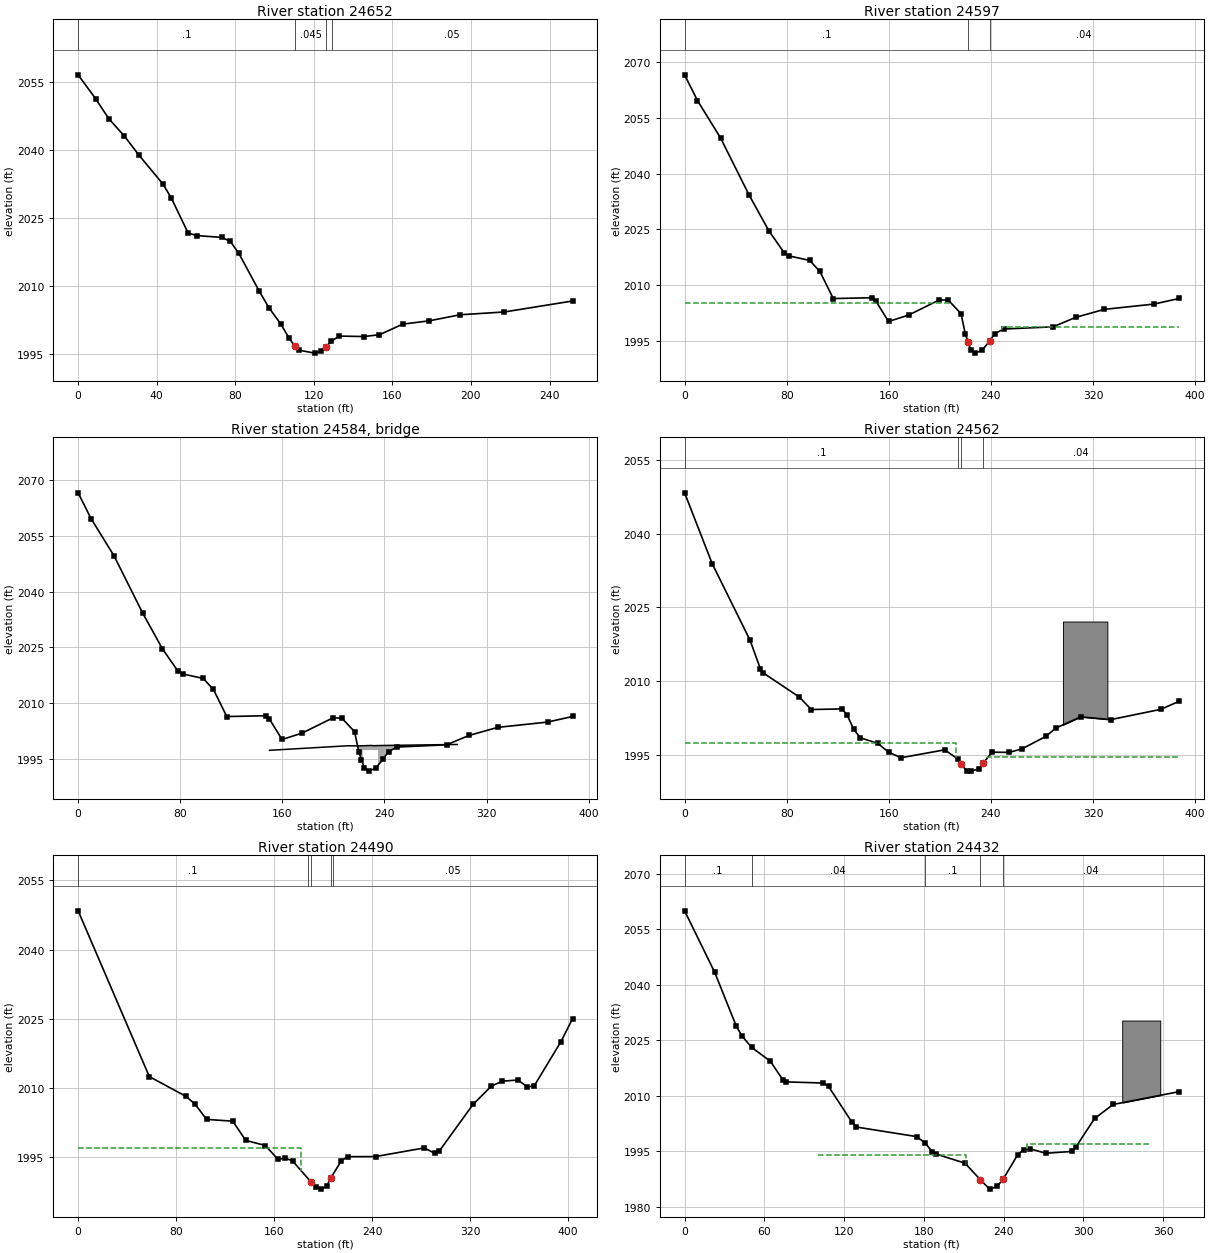
Type RM Length L Ch R = 1 ,24652   ,65.8,54.9,38.6
Node Name=H
XS GIS Cut Line= 3
     1980417.151      251568.202     1980329.478      251464.035
     1980233.992      251398.931
#Sta/Elev= 30
       0 2056.61     8.9 2051.34    15.6 2046.94    23.6 2043.07    30.9 2038.93
    43.2  2032.5    47.5 2029.38      56 2021.71    60.3 2021.15    73.2 2020.75
    77.5 2019.85    81.8 2017.24    92.1 2008.96    97.2 2005.19   103.2 2001.62
   107.5 1998.45   110.21996.866   112.5 1995.87   120.4 1995.22   123.7  1995.6
   126.41996.667   128.9 1997.87     133 1998.98   145.5 1998.88   153.4 1999.28
   165.3 2001.62   178.8 2002.35   194.4 2003.68     217  2004.3   251.7 2006.72
#Mann= 4 ,-1 , 0
       0      .1       0   110.2    .045       0   126.4     .05       0
   129.1     .05       0
Bank Sta=110.2,126.4
XS Rating Curve= 0 ,0
Exp/Cntr=0.5,0.3

Type RM Length L Ch R = 1 ,24597   ,35.1,35.3,34.8
XS GIS Cut Line= 6
     1980579.429      251515.163     1980448.135      251424.018
     1980406.903      251438.123      1980359.16      251446.804
     1980323.353      251447.889     1980239.802      251393.636
#Sta/Elev= 30
       0 2066.63    10.1  2059.7    28.2 2049.62    50.5  2034.3      66 2024.65
      78 2018.73      82 2017.86      98 2016.66     106 2013.69   116.5 2006.39
   147.2 2006.62   149.9 2005.71   159.8 2000.22   175.5 2001.94   199.6 2006.03
   206.6 2005.98   216.6 2002.33   219.9 1996.95     2221994.786  224.16  1992.6
  227.78  1991.7  233.28 1992.52     2391994.968   243.2 1996.95     250 1998.19
   288.7 1998.78   306.4 2001.32   328.8 2003.48   367.9 2004.91   387.4 2006.41
#Mann= 3 ,-1 , 0
       0      .1       0     222    .045       0     239     .04       0
#XS Ineff= 2 , 0
             209 2005.28     249         1998.65
Permanent Ineff=
       F       F
Bank Sta=222,239
XS Rating Curve= 0 ,0
Exp/Cntr=0.5,0.3

Type RM Length L Ch R = 3 ,24584   ,,,
BEGIN DESCRIPTION:
Normal Farley Dr
Survey ID: MAC280
END DESCRIPTION:
Bridge Culvert--1,0,-1,-1, 0
Deck Dist Width WeirC Skew NumUp NumDn MinLoCord MaxHiCord MaxSubmerge Is_Ogee
13,12,2.6,0, 11, 10, , , 0.98, 0, 0,0,,
     150     211     218     223     223     229     232     235     235     240
     297
1997.3031998.5231998.495 1998.52 1998.521998.6111998.548 1998.58 1998.581998.611
1998.879
                                 1997.321997.4111997.348 1997.38
        
     150     211     218     219     219     229     231     231     240     297
1997.3031998.5231998.495 1998.52 1998.521998.6111998.5481998.5481998.6111998.879
                                 1997.321997.4111997.348
BR Coef=-1 , 1 , 0 ,, 0 ,,,0.8,0,1.2,0,
WSPro=,,,, 1 ,,,, 0 ,,,, 0 ,,,,-1 ,-1 ,-1 , 0 , 0 , 0 , 0 , 0
BC Design=,, 0 ,, 0 ,,,,,,
BC Use User HTab Curves=0
BC User HTab FreeFlow(D)= 0

Type RM Length L Ch R = 1 ,24562   ,64.4,72.6,85.2
XS GIS Cut Line= 6
     1980587.024      251483.697     1980455.731      251392.551
     1980414.498      251406.657     1980366.755      251415.337
     1980330.948      251416.422     1980247.398      251362.169
#Sta/Elev= 30
       0 2048.29    21.6  2033.9    51.3 2018.32    59.3 2012.57    61.7 2011.67
      90 2006.76    99.2 2004.24   123.2 2004.37   127.2 2003.22   132.4 2000.29
   137.6  1998.5   151.4 1997.36   159.8 1995.58   169.6 1994.44   203.8 1996.05
   214.3 1994.15   216.4 1993.17     221 1991.83   224.2 1991.72     231 1992.18
     2341993.362     241 1995.58   254.3 1995.53   264.1 1996.22     283 1998.76
   290.9 2000.48   310.4 2002.75   333.9 2002.19     373 2004.27   387.4  2005.9
#Mann= 4 ,-1 , 0
       0      .1       0   214.3      .1       0   216.4    .045       0
     234     .04       0
#XS Ineff= 2 , 0
             213 1997.34     237          1994.6
Permanent Ineff=
       F       F
#Block Obstruct= 1 ,-1
  296.49  331.28 2022.13
Bank Sta=216.4,234
XS Rating Curve= 0 ,0
Exp/Cntr=0.5,0.3

Type RM Length L Ch R = 1 ,24490   ,56.1,57.9,59.8
XS GIS Cut Line= 3
     1980601.179      251478.358     1980472.056      251377.446
     1980274.573      251241.813
#Sta/Elev= 30
       0 2048.41    58.1 2012.45    88.1 2008.15    95.5 2006.46   104.8 2003.17
   126.2 2002.78   136.8 1998.61   152.8  1997.5   163.2 1994.47   169.2 1994.79
   175.1 1994.12   189.81989.685   193.9  1988.4   198.2 1988.04   202.9  1988.7
     2061990.375   214.8 1994.18   219.9 1995.08   242.7  1995.1   282.5 1996.98
   290.9 1995.82   294.5 1996.21   322.3 2006.41   337.3  2010.4   346.2 2011.46
   359.1 2011.71   366.3 2010.24   372.1 2010.39     394 2020.01   403.5 2024.98
#Mann= 5 ,-1 , 0
       0      .1       0   187.6      .1       0   189.8    .045       0
     206     .05       0   207.6     .05       0
#XS Ineff= 2 , 0
          181.97 1997.06
Permanent Ineff=
       F       F
Bank Sta=189.8,206
XS Rating Curve= 0 ,0
Exp/Cntr=0.5,0.3

Type RM Length L Ch R = 1 ,24432   ,44.2,43.4,43.5
XS GIS Cut Line= 3
     1980629.342      251482.611     1980499.134      251331.787
     1980372.181      251214.599
#Sta/Elev= 30
       0 2059.98    22.6  2043.4    38.9  2028.8    43.3 2026.09    50.5 2023.05
    64.5 2019.34      74 2014.27    76.1 2013.75   103.9 2013.44   108.3 2012.52
   125.6 2003.02   129.3 2001.54   174.5 1998.96   180.8 1997.31   186.3  1994.9
   189.5 1994.23     211 1991.76   222.6 1987.28   229.6 1984.76  235.17 1985.49
   239.7 1987.46   250.5 1993.98   255.1 1995.46   259.8 1995.66   271.8 1994.46
   291.2 1994.94   294.6 1996.25   308.5 2003.86   322.5 2007.65     372  2011.1
#Mann= 5 ,-1 , 0
       0      .1       0    50.5     .04       0   180.8      .1       0
   222.6    .045       0   239.7     .04       0
#XS Ineff= 3 ,-1
     100     212  1993.9     254     258  1993.2     258     350    1997
Permanent Ineff=
       F       F       F
#Block Obstruct= 1 ,-1
  329.29   357.9 2030.33
Bank Sta=222.6,239.7
XS Rating Curve= 0 ,0
Exp/Cntr=0.5,0.3