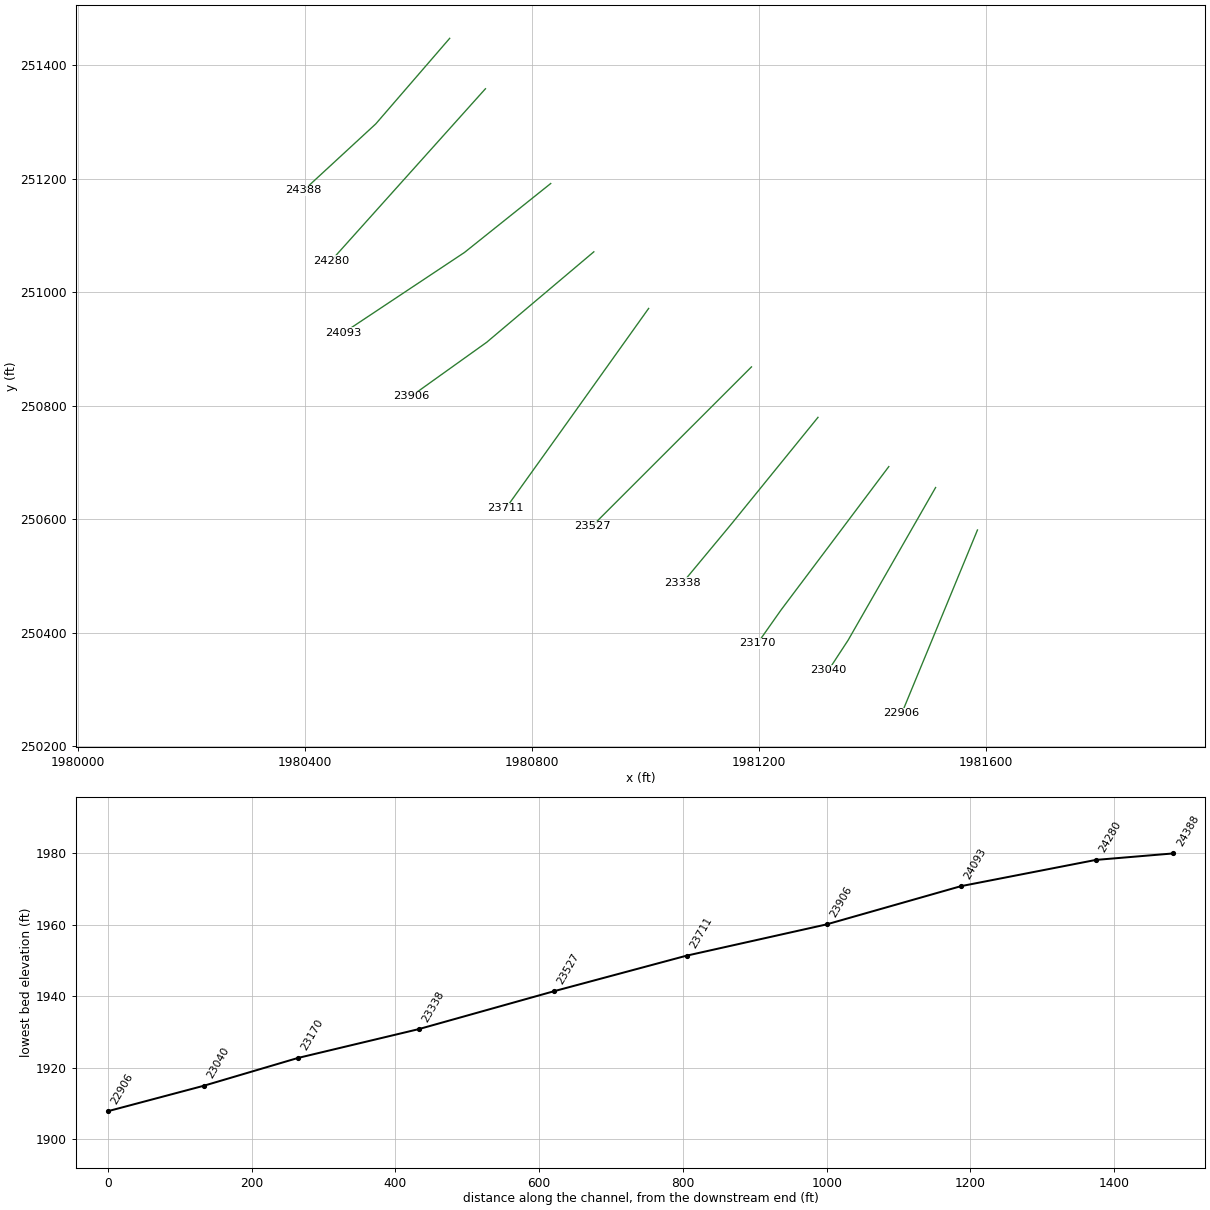
HEC-RAS study MADAMCK.prj: MADAMCK

--- MADAMCK.g01 (geometry) --- (continued)

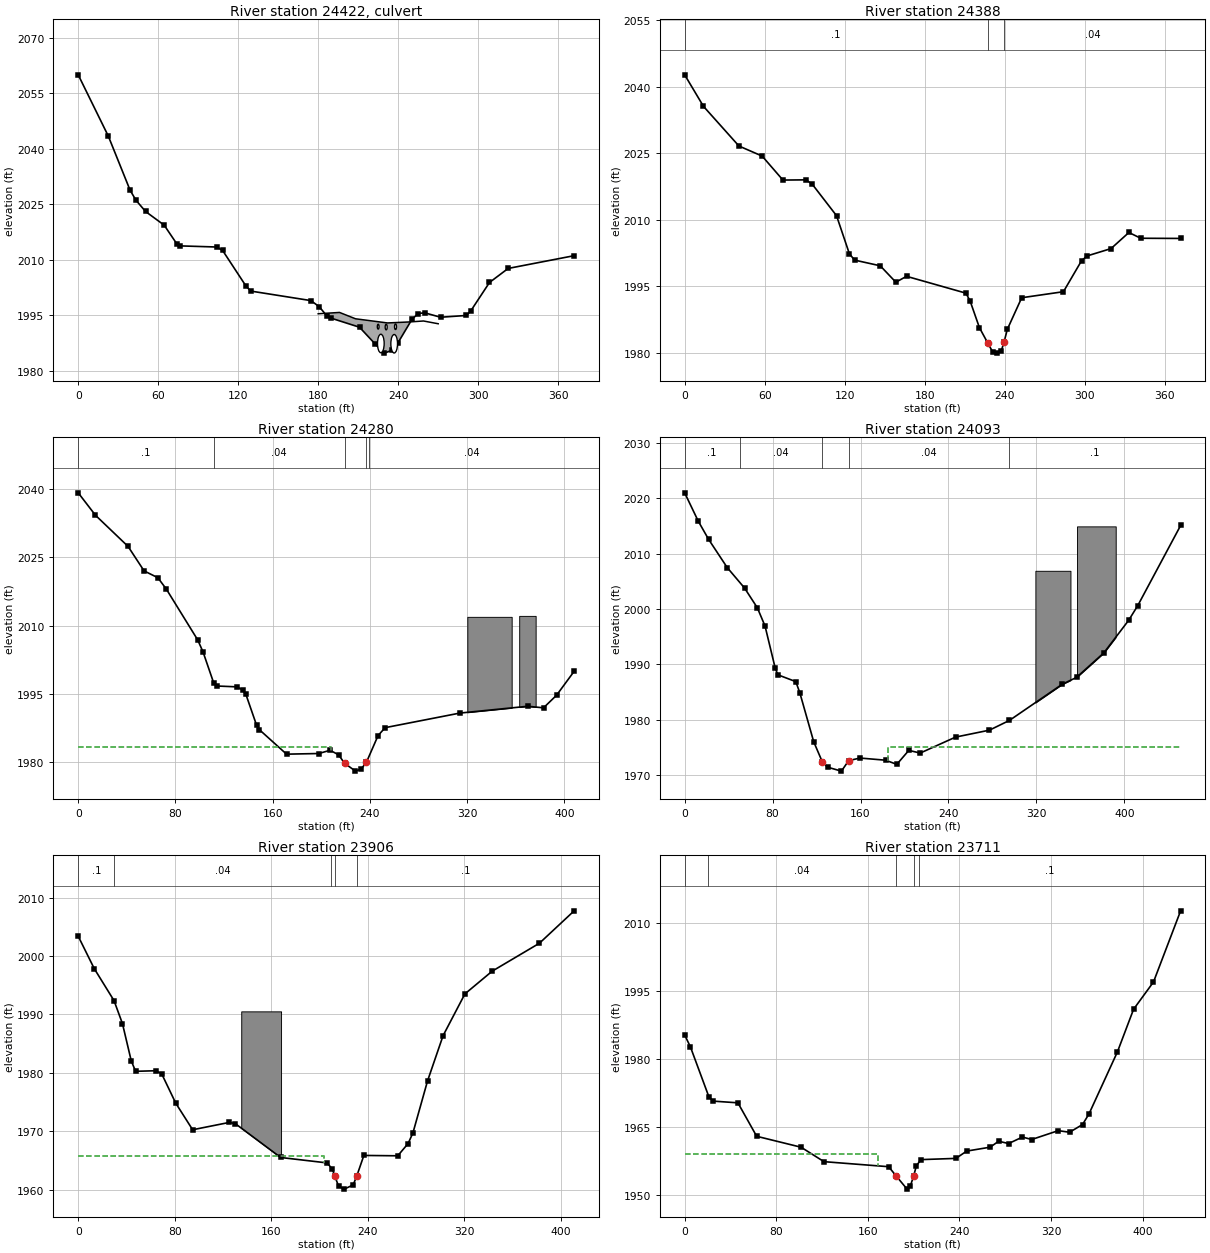
Type RM Length L Ch R = 2 ,24422   ,,,
BEGIN DESCRIPTION:
Private Driveway
Survey ID: MAC270
END DESCRIPTION:
Bridge Culvert--1,0,-1,-1, 0
Deck Dist Width WeirC Skew NumUp NumDn MinLoCord MaxHiCord MaxSubmerge Is_Ogee
14,12,2.6,0, 7, 7, , , 0.98, 0, 0,0,,
     180     196     208     232     249     259     270
  1995.4 1995.761994.0451992.9181993.1991993.447  1992.7
                                                        
     180     196     208     232     249     259     270
  1995.4 1995.761994.0451992.9181993.1991993.447  1992.7
                                                        
BR Coef=-1 , 1 , 0 ,, 0 ,,,0.8,0,1.2,0,
WSPro=,,,, 1 ,,,, 0 ,,,, 0 ,,,,-1 ,-1 ,-1 , 0 , 0 , 0 , 0 , 0
Culvert=1,1.3,,20,0.019,0.5,1,2,1,1991.264,225,1990.821,225,Culvert #1  , 0 ,11
     225     225
BC Culvert Barrel=1,Barrel1,0
Culvert Bottom n=0.019
Culvert=1,5,,24,0.019,0.9,1,2,3,1984.867,227,1982.417,227,Culvert #4  , 0 ,8.5
     227     227
BC Culvert Barrel=1,Barrel1,0
Culvert Bottom n=0.019
Culvert=1,1.5,,20,0.019,0.5,1,2,1,1991.056,231,1988.438,231,Culvert #2  , 0 ,11
     231     231
BC Culvert Barrel=1,Barrel1,0
Culvert Bottom n=0.019
Culvert=1,5,,24,0.019,0.9,1,2,3,1984.795,237,1979.921,237,Culvert #5  , 0 ,8.5
     237     237
BC Culvert Barrel=1,Barrel5,0
Culvert Bottom n=0.019
Culvert=1,1.5,,20,0.019,0.5,1,2,1,1991.144,238,1989.604,238,Culvert #3  , 0 ,11
     238     238
BC Culvert Barrel=1,Barrel1,0
Culvert Bottom n=0.019
BC Design=,, 0 ,, 0 ,,,,,,
BC Use User HTab Curves=0
BC User HTab FreeFlow(D)= 0

Type RM Length L Ch R = 1 ,24388   ,106.3,108,108.9
XS GIS Cut Line= 3
     1980655.384      251447.889     1980525.176      251297.065
     1980398.223      251179.877
#Sta/Elev= 30
       0 2042.66    14.1 2035.55    40.7 2026.61    58.1 2024.34    73.7 2018.93
    90.9 2018.98    95.6 2018.03   113.9  2010.9   123.5 2002.35   127.4 2000.89
   146.7  1999.6   158.4  1995.9   166.4 1997.23     211 1993.43   214.2 1991.58
   221.1 1985.64  227.21 1982.26   231.1 1980.14  234.04 1979.91   237.4 1980.33
  239.66 1982.51     242 1985.27   252.8  1992.4   284.1 1993.76   297.7 2000.75
   301.9 2001.83   319.8 2003.48   333.2 2007.11   342.1 2005.81     372 2005.77
#Mann= 3 , 0 , 0
       0      .1       0  227.21    .045       0  239.66     .04       0
#XS Ineff= 2 , 0
             216  1986.7     247          1986.9
Permanent Ineff=
       F       F
Bank Sta=227.21,239.66
XS Rating Curve= 0 ,0
Exp/Cntr=0.5,0.3

Type RM Length L Ch R = 1 ,24280   ,187.6,187.6,181.4
XS GIS Cut Line= 2
     1980718.367         251359.     1980446.014      251055.181
#Sta/Elev= 30
       0 2039.11    14.2 2034.19      41 2027.36    54.2 2021.99    65.5  2020.5
    72.5    2018    98.3 2006.86   102.7 2004.22   111.5 1997.39   114.3 1996.75
   130.5 1996.57   135.2 1995.91   137.9 1994.96   146.7 1988.18   149.1 1987.16
   171.4 1981.81   197.9 1981.95   207.2 1982.66   214.2 1981.67   219.11979.812
   228.1 1978.09   232.8 1978.57   237.11980.029   246.7 1985.89   252.5 1987.62
     314 1990.82   369.8 1992.31   382.8 1991.97   393.5 1994.72     408 1999.98
#Mann= 5 ,-1 , 0
       0      .1       0   111.5     .04       0   219.1    .045       0
   237.1     .04       0   239.1     .04       0
#XS Ineff= 2 , 0
          207.89 1983.37
Permanent Ineff=
       F       F
#Block Obstruct= 2 ,-1
   320.1   356.6 2011.92  362.79  376.32 2012.13
Bank Sta=219.1,237.1
XS Rating Curve= 0 ,0
Exp/Cntr=0.3,0.1

Type RM Length L Ch R = 1 ,24093   ,190,186.9,179.9
XS GIS Cut Line= 3
     1980833.384        251191.9     1980681.474      251070.372
     1980467.715      250928.228
#Sta/Elev= 30
       0 2020.95    12.3 2015.86    21.7 2012.58    38.7 2007.47    54.5 2003.77
    66.1 2000.22    73.1 1996.93    82.4 1989.31    84.8 1988.13   101.1  1986.9
   104.8 1984.86   117.4 1976.05   125.11972.485     130 1971.47   142.6 1970.76
   149.21972.655   159.5 1973.12   182.8 1972.73     193 1971.98   203.9  1974.5
   214.3 1974.02   246.5  1976.9   277.3 1978.15   295.5 1979.91   343.5 1986.43
   356.5 1987.66   381.4  1992.1   403.9 1997.95   412.2 2000.61   451.2 2015.06
#Mann= 5 ,-1 , 0
       0      .1       0      50     .04       0   125.1    .045       0
   149.2     .04       0   295.5      .1       0
#XS Ineff= 2 , 0
                          185.07          1975.2
Permanent Ineff=
       F       F
#Block Obstruct= 2 ,-1
  319.07  350.98 2006.89  356.94  392.15  2014.9
Bank Sta=125.1,149.2
XS Rating Curve= 0 ,0
Exp/Cntr=0.3,0.1

Type RM Length L Ch R = 1 ,23906   ,192.8,194.8,197.7
XS GIS Cut Line= 3
     1980909.339      251071.457     1980720.537      250911.952
     1980587.073      250816.466
#Sta/Elev= 30
       0  2003.4    13.3 1997.85    29.7 1992.37    36.7 1988.42      44 1982.04
    47.6 1980.26    64.6 1980.36    69.3  1979.8    80.9  1974.8    94.9 1970.25
   125.4 1971.51   130.4 1971.28   167.9  1965.5   206.5 1964.57   210.8 1963.48
   212.91962.247   215.9 1960.61   220.6 1960.08     228  1960.8   230.91962.262
   236.9 1965.85     265 1965.79   273.6 1967.89   277.6 1969.72   289.7 1978.61
   302.6 1986.37   320.7 1993.52   343.3 1997.41   382.5  2002.2   411.3 2007.75
#Mann= 5 ,-1 , 0
       0      .1       0      30     .04       0   209.8     .04       0
   212.9    .045       0   230.9      .1       0
#XS Ineff= 2 , 0
          204.23 1965.84  427.32         1982.55
Permanent Ineff=
       F       F
#Block Obstruct= 1 ,-1
   135.2  168.23 1990.53
Bank Sta=212.9,230.9
XS Rating Curve= 0 ,0
Exp/Cntr=0.3,0.1

Type RM Length L Ch R = 1 ,23711   ,184.5,184.4,181.3
XS GIS Cut Line= 3
      1981005.91      250971.631      1980849.66      250752.447
     1980754.174      250618.983
#Sta/Elev= 30
       0 1985.29       5 1982.68    21.1 1971.71    25.1 1970.72    46.5 1970.35
    62.9 1962.98   101.7 1960.57   121.7 1957.39   178.2 1956.28   184.91954.199
   194.3 1951.34     197 1951.92     200 1954.18   202.4 1956.46   206.4 1957.84
     237 1958.11   246.4 1959.72   266.9 1960.58   274.3 1961.89     283 1961.38
   295.1 1962.81   303.2 1962.27   326.4 1964.22   336.3 1963.87   347.6 1965.57
   353.2 1967.88   378.1 1981.58   392.2 1990.96   409.6 1996.97   433.3 2012.64
#Mann= 5 ,-1 , 0
       0     .06       0      20     .04       0   184.9    .045       0
     200      .1       0   204.3      .1       0
#XS Ineff= 2 , 0
           169.3 1958.97
Permanent Ineff=
       F       F
Bank Sta=184.9,200
XS Rating Curve= 0 ,0
Exp/Cntr=0.3,0.1

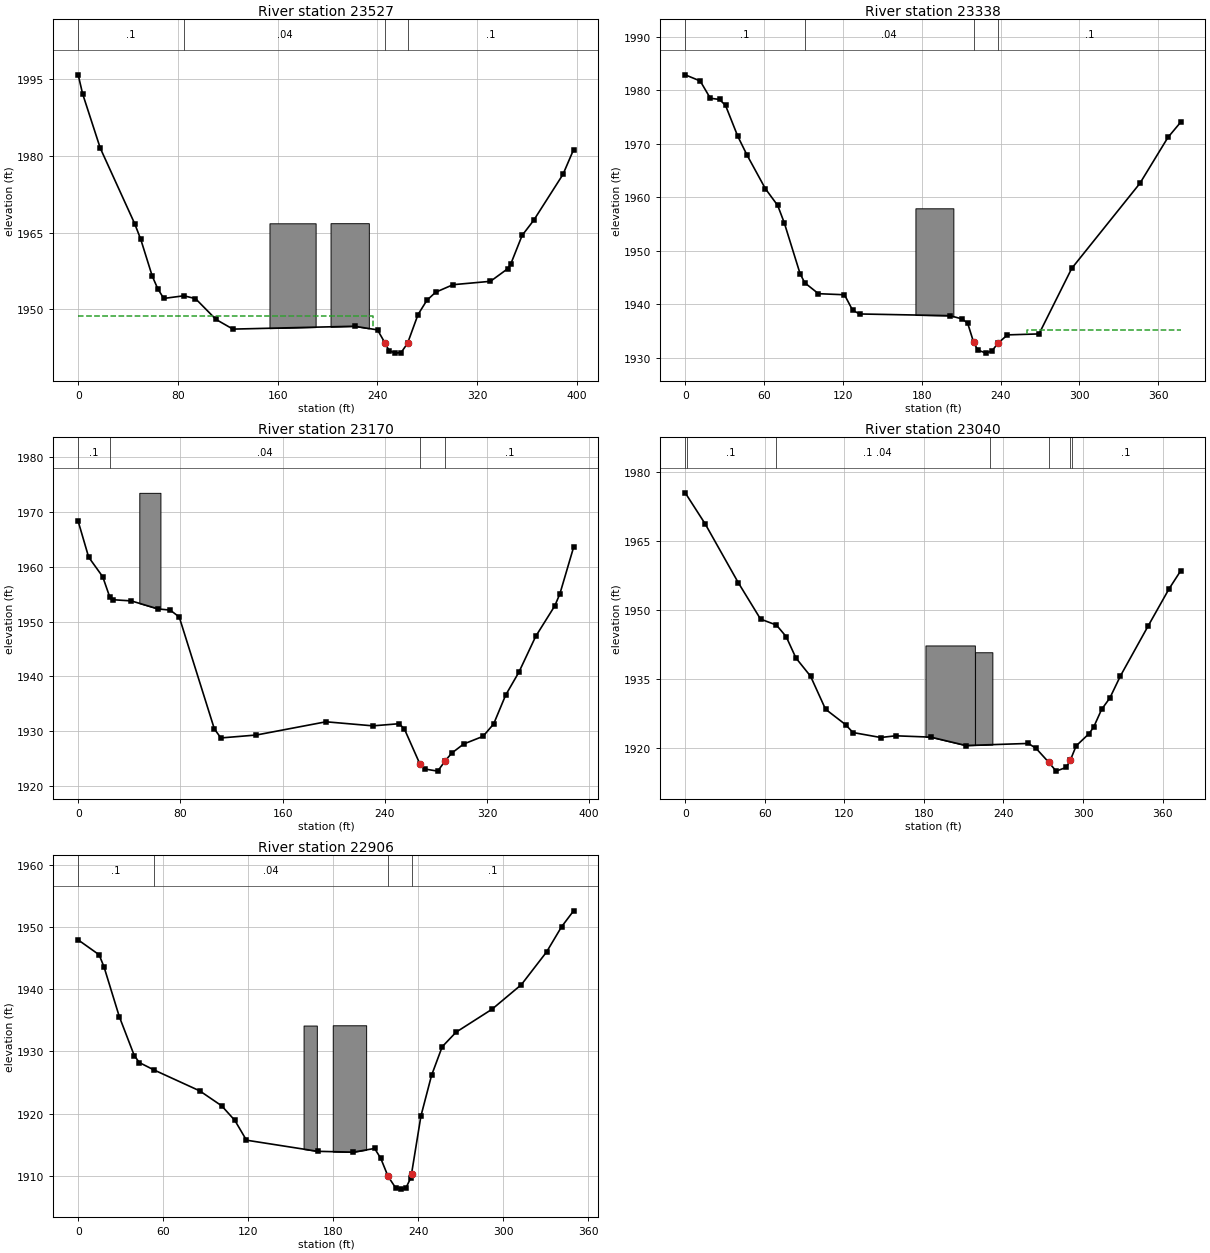
Type RM Length L Ch R = 1 ,23527   ,186.6,188.2,186.8
XS GIS Cut Line= 2
     1981187.117      250868.549     1980906.084      250587.516
#Sta/Elev= 30
       0 1995.86     3.5 1992.19    17.7 1981.52    45.3 1966.75    50.2 1963.66
    59.4 1956.48    63.8 1954.03    68.6 1952.11    84.8 1952.63    94.1 1952.07
   110.5 1948.01   124.1 1946.11   221.7 1946.67   240.1 1945.96     2461943.438
   249.4  1941.9   254.1 1941.41     259 1941.51   264.21943.333   272.6 1948.96
   279.7 1951.74   286.7 1953.32   300.7  1954.8   330.7 1955.46   344.7 1957.95
   346.9 1958.79   356.1 1964.44   365.4  1967.4   388.9 1976.39   397.4 1981.23
#Mann= 4 ,-1 , 0
       0      .1       0    84.8     .04       0     246    .045       0
   264.2      .1       0
#XS Ineff= 2 , 0
          236.62 1948.59
Permanent Ineff=
       F       F
#Block Obstruct= 2 ,-1
  153.43  190.46 1966.81  202.42  233.14 1966.83
Bank Sta=246,264.2
XS Rating Curve= 0 ,0
Exp/Cntr=0.3,0.1

Type RM Length L Ch R = 1 ,23338   ,166.2,167.9,167.3
XS GIS Cut Line= 3
     1981304.304      250779.573     1981150.224      250589.686
     1981065.589       250487.69
#Sta/Elev= 30
       0 1982.84    11.4 1981.69    19.1 1978.46    26.1 1978.24    30.7 1977.11
      40 1971.35      47 1967.86      61 1961.56    70.4 1958.42    75.4 1955.17
    87.4 1945.69      91 1943.96   101.4 1941.93   121.2 1941.73   127.4 1938.85
   132.7 1938.14   201.5 1937.82   210.8 1937.21     215  1936.4   219.51932.871
   222.6 1931.41   228.9 1930.82   233.6 1931.26     2381932.666   245.3 1934.23
   269.3 1934.41   294.2 1946.66   346.1 1962.56   367.4 1971.13   377.1 1973.98
#Mann= 4 ,-1 , 0
       0      .1       0      91     .04       0   219.5    .045       0
     238      .1       0
#XS Ineff= 2 , 0
                          260.28          1935.2
Permanent Ineff=
       F       F
#Block Obstruct= 1 ,-1
  175.22   204.1 1957.89
Bank Sta=219.5,238
XS Rating Curve= 0 ,0
Exp/Cntr=0.3,0.1

Type RM Length L Ch R = 1 ,23170   ,129.7,130.9,132.3
XS GIS Cut Line= 3
     1981429.087      250692.768       1981239.2      250439.947
     1981197.967      250381.353
#Sta/Elev= 30
       0 1968.23     8.2 1961.71    19.2 1958.15    24.6 1954.53    27.5 1953.96
    41.6 1953.75    62.7 1952.28      72 1952.08    79.1 1950.82   106.6 1930.44
   111.7 1928.81   139.4 1929.34     194 1931.75   230.7 1931.01   251.3  1931.4
   255.4 1930.41   267.51924.058   271.2 1923.16   281.4 1922.77   287.51924.694
   292.3 1926.03   301.7  1927.7   316.9  1929.1   325.2 1931.35   334.6  1936.6
     345 1940.79   358.1 1947.28   373.1 1952.86   377.1 1955.07   387.8 1963.52
#Mann= 4 ,-1 , 0
       0      .1       0    24.6     .04       0   267.5    .045       0
   287.5      .1       0
#Block Obstruct= 1 ,-1
   47.84   64.38 1973.42
Bank Sta=267.5,287.5
XS Rating Curve= 0 ,0
Exp/Cntr=0.3,0.1

Type RM Length L Ch R = 1 ,23040   ,132.6,133.6,135.2
XS GIS Cut Line= 3
     1981511.552      250655.875     1981357.473      250386.778
      1981322.75       250333.61
#Sta/Elev= 30
       0 1975.51    15.1 1968.73      40 1955.98    56.8 1948.06    68.8 1946.76
    76.1 1944.26    83.5  1939.6    94.5 1935.65   105.8 1928.47   120.9 1925.12
   126.5  1923.4   147.4 1922.32   158.7 1922.69   185.2  1922.4   211.7 1920.58
   258.8 1921.03   264.6 1919.95   274.21916.909   279.7 1915.01   287.3 1915.82
   290.51917.443   294.8  1920.5   304.4 1923.12     308 1924.57     314 1928.43
   320.2  1930.9   328.2 1935.71   349.1 1946.57   364.8 1954.61   373.6 1958.54
#Mann= 7 ,-1 , 0
       0      .1       0    68.8     .04       0     230      .1       0
     1.3      .1       0   274.2    .045       0   290.5      .1       0
   291.3      .1       0
#Block Obstruct= 2 ,-1
  181.16  218.42 1942.33  218.59  231.62 1940.85
Bank Sta=274.2,290.5
XS Rating Curve= 0 ,0
Exp/Cntr=0.3,0.1

Type RM Length L Ch R = 1 ,22906   ,142.9,143.1,143.8
XS GIS Cut Line= 2
     1981585.337      250581.005     1981451.874      250257.655
#Sta/Elev= 30
       0 1947.91    14.8 1945.52    18.3 1943.53      29 1935.61    39.6 1929.34
    43.2 1928.21    53.5 1927.03    85.8 1923.67   101.3 1921.27   110.6 1918.93
   118.8 1915.75   169.1 1913.96   194.2 1913.83   209.3 1914.42   213.6 1912.85
   218.8 1909.93   224.2 1908.08   227.8 1907.89   231.3 1908.03   234.9 1909.73
   235.41910.385     242 1919.63   249.5 1926.16     257 1930.75   266.8 1933.09
   292.2 1936.78   312.9 1940.72   330.7 1945.97   341.3 1950.02   349.8 1952.58
#Mann= 4 ,-1 , 0
       0      .1       0    53.5     .04       0   218.8    .045       0
   235.4      .1       0
#Block Obstruct= 2 ,-1
  159.13  168.49 1934.16  179.73  203.33  1934.2
Bank Sta=218.8,235.4
XS Rating Curve= 0 ,0
Exp/Cntr=0.3,0.1