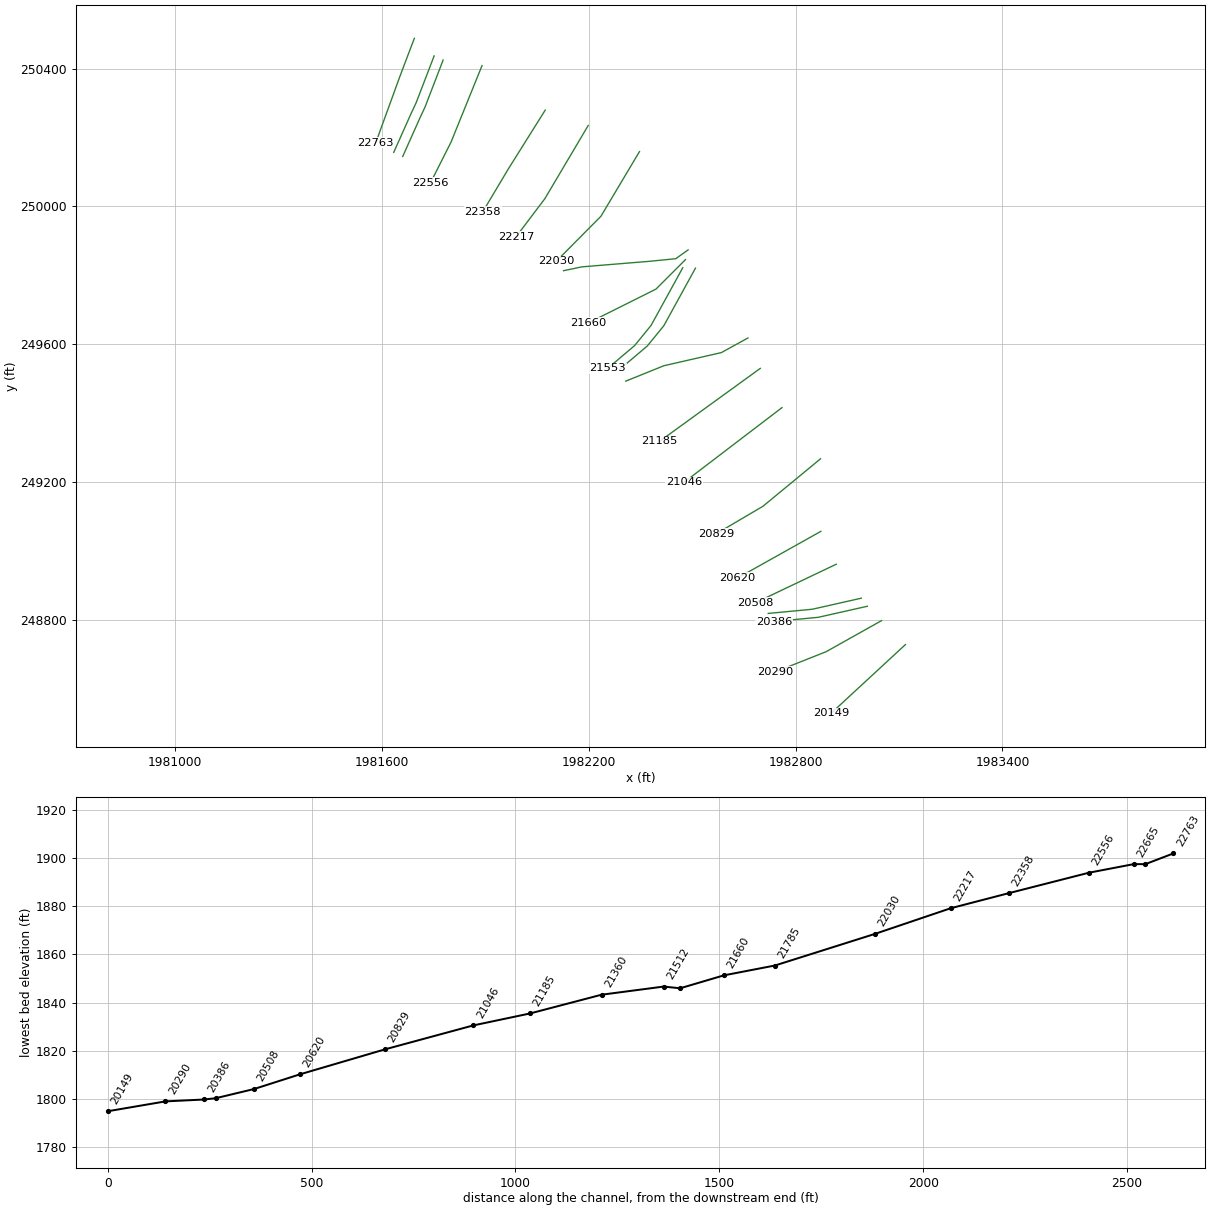
HEC-RAS study MADAMCK.prj: MADAMCK

--- MADAMCK.g01 (geometry) --- (continued)

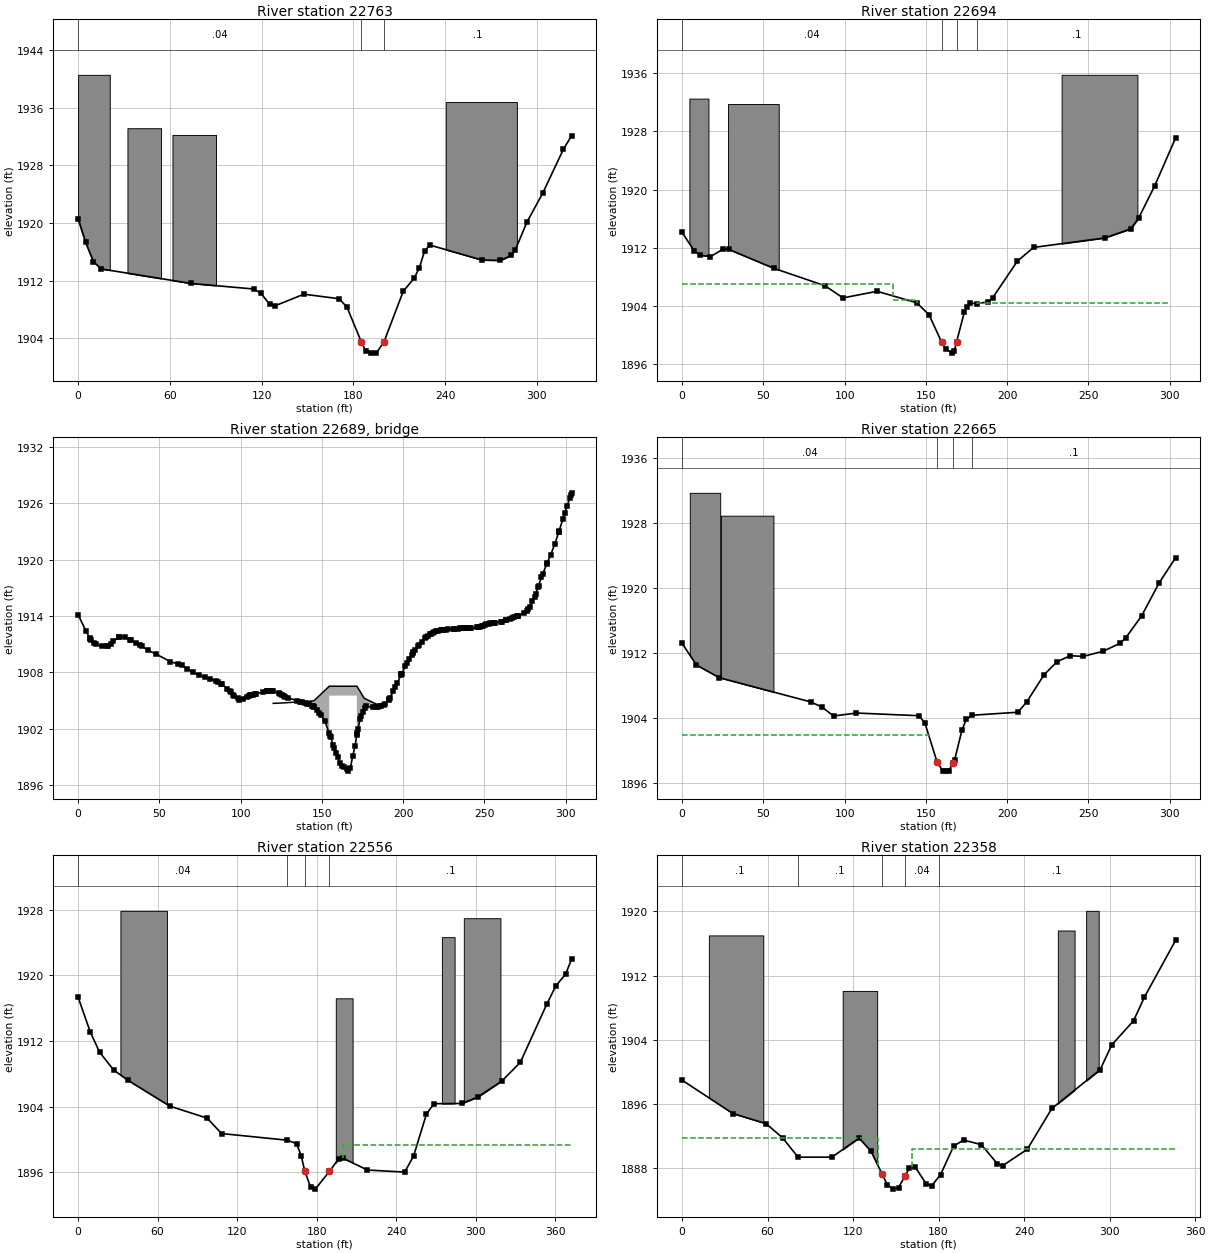
Type RM Length L Ch R = 1 ,22763   ,69.6,68.9,68.3
XS GIS Cut Line= 3
     1981693.844       250487.69     1981651.526      250375.927
     1981582.082      250184.955
#Sta/Elev= 30
       0 1920.58     4.9 1917.32      10 1914.65    15.1 1913.64    73.6 1911.63
   114.8 1910.85   119.4 1910.29   125.3 1908.71   128.8 1908.52   147.6 1910.13
   170.7  1909.5   175.8 1908.34   185.11903.553   188.1 1902.23   191.6 1901.95
   195.1    1902     2001903.513   212.6 1910.53   219.6 1912.32   223.1 1913.76
   226.5 1916.09     230 1916.95   264.1 1914.87   276.1 1914.82   283.3 1915.52
   285.9 1916.29   293.5 1920.15   303.8 1924.15   317.3 1930.24   322.7 1932.13
#Mann= 3 , 0 , 0
       0     .04       0   185.1    .045       0     200      .1       0
#Block Obstruct= 4 ,-1
       0   20.72 1940.58   32.27   54.26 1933.17   61.69    90.2 1932.24
   240.4  286.91  1936.8
Bank Sta=185.1,200
XS Rating Curve= 0 ,0
Exp/Cntr=0.5,0.3

Type RM Length L Ch R = 1 ,22694   ,28.8,28.7,28.8
XS GIS Cut Line= 4
     1981751.304      250436.605     1981699.221      250300.971
      1981684.03      250268.419     1981634.116      250156.657
#Sta/Elev= 30
       0 1914.13     7.3 1911.61    11.1 1910.97    17.5 1910.78    25.1 1911.78
    28.7 1911.77    56.8 1909.14    88.1 1906.75      99 1905.09     120    1906
   144.4 1904.42   151.9 1902.78  159.77 1898.98  162.29 1898.04   166.31897.492
  167.52 1897.83  168.93 1899.09   173.6 1903.09   175.1  1903.8   177.2 1904.39
   181.5 1904.28     188 1904.55     191 1905.07   206.3 1910.16   216.3 1912.04
   259.9 1913.34   275.9 1914.58   280.8 1916.04   290.8 1920.53   303.6  1927.1
#Mann= 4 ,-1 , 0
       0     .04       0  159.77    .045       0  168.93     .04       0
   181.5      .1       0
#XS Ineff= 3 ,-1
       0     130    1907     130   144.5 1904.87   181.5     300 1904.41
Permanent Ineff=
       F       F       F
#Block Obstruct= 3 ,-1
    4.52   16.26 1932.52   28.25   59.48 1931.77   233.5  280.13 1935.79
Bank Sta=159.77,168.93
XS Rating Curve= 0 ,0
Exp/Cntr=0.5,0.3

Type RM Length L Ch R = 3 ,22689   ,,,
BEGIN DESCRIPTION:
Unnamed Road
Survey ID: MAC260
END DESCRIPTION:
Bridge Culvert--1,0,-1,-1, 0
Deck Dist Width WeirC Skew NumUp NumDn MinLoCord MaxHiCord MaxSubmerge Is_Ogee
10,11,2.6,0, 10, 10, , , 0.98, 0, 0,0,,
     120     127     145   154.5   154.5     162   171.5   171.5     176     185
  1904.71904.7561904.9651906.5251906.5251906.5251906.5251906.5251905.244  1904.5
                                1905.5251905.5251905.525
     120     127     145   154.5   154.5     162   171.5   171.5     176     185
  1904.71904.7561904.9651906.5251906.5251906.5251906.5251906.5251905.244  1904.5
                                1905.5251905.5251905.525
BR Coef=-1 , 1 , 0 ,, 0 ,,,0.8,0,1.2,0,
WSPro=,,,, 1 ,,,, 0 ,,,, 0 ,,,,-1 ,-1 ,-1 , 0 , 0 , 0 , 0 , 0
BR U #Sta/Elev= 198
       0 1914.13     4.8 1912.42     7.3 1911.61     7.6 1911.54     8.2 1911.44
     9.8 1911.13    11.1 1910.97    14.9 1910.77    17.5 1910.78    18.1 1910.81
      20 1911.05    21.6 1911.32    24.9 1911.76    25.1 1911.78    28.7 1911.77
    32.2 1911.46    32.7 1911.39    35.7 1911.15    37.8 1910.95    39.2 1910.79
    42.9 1910.36    47.9 1909.95    56.8 1909.14    61.5 1908.88    63.8 1908.73
    67.3 1908.35    70.9 1907.99    74.4  1907.7    77.9 1907.48    81.4 1907.33
    84.9 1907.05      86 1906.94    88.1 1906.75    88.4 1906.72    91.9 1906.28
    93.6 1905.97    93.8 1905.95    95.4 1905.62    96.2 1905.51    98.1 1905.22
      99 1905.09   101.3 1905.18   103.8 1905.37   105.2  1905.5     106 1905.57
   106.3 1905.58   107.3 1905.63   108.9 1905.71   109.5 1905.74     114 1905.91
   116.4 1905.97   116.5 1905.97   116.6 1905.97     119    1906     120    1906
   123.6 1905.76   124.1  1905.7   125.6 1905.56   126.7 1905.46   127.1 1905.42
   129.2 1905.29   134.7 1904.99   136.8 1904.89   137.6 1904.83   139.4 1904.74
   141.1 1904.64   141.9 1904.59   143.9 1904.46   144.4 1904.42   144.6 1904.39
   145.1  1904.3   145.3 1904.27   146.9    1904   148.2 1903.72   149.4 1903.45
   151.9 1902.78   154.3 1901.58   155.11901.247   155.5 1901.08   156.8 1900.31
  157.71  1899.9  158.87 1899.43  159.77 1898.98  160.98 1898.35  162.29 1898.04
  163.55 1897.97  165.16 1897.72   166.31897.492  167.52 1897.83  168.93 1899.09
  170.39 1900.17   171.41901.386   171.6 1901.55   172.2 1902.02   173.6 1903.09
   174.1 1903.38   175.1  1903.8   176.5 1904.25   177.2 1904.39   181.5 1904.28
     183  1904.3   184.4 1904.34   185.6 1904.41   186.5 1904.44     188 1904.55
   188.9 1904.67     191 1905.07   191.4 1905.17   191.6 1905.22   193.9 1905.99
   195.2 1906.46   196.4 1906.89   198.6  1907.7   198.8 1907.78   198.9 1907.81
     199 1907.87   201.4 1908.65   202.4 1908.98   203.8 1909.43   205.1  1909.8
     206 1910.07   206.3 1910.16   207.1 1910.35   208.8 1910.77   209.6 1910.93
   211.3 1911.27   213.2 1911.61   213.8 1911.71   215.1  1911.9   216.3 1912.04
   216.8 1912.09   218.1  1912.2   218.7 1912.25   220.4 1912.36   221.2 1912.39
   223.2 1912.46   223.7 1912.48   223.9 1912.49   224.6  1912.5   226.2 1912.55
   227.5 1912.57   231.1 1912.59   231.2 1912.59   233.6 1912.66   234.7 1912.68
   236.1  1912.7   237.5 1912.71   238.3 1912.71   238.6 1912.71   239.3 1912.69
   241.1 1912.67   241.9 1912.68   245.5 1912.78   246.1 1912.81   247.3 1912.86
   248.5 1912.94   249.1 1912.97   250.5 1913.06     251  1913.1   252.7 1913.19
   253.5 1913.22   255.4 1913.27     256 1913.28   256.3 1913.28   259.9 1913.34
     261 1913.39   263.5 1913.56   263.5 1913.57   265.9 1913.69   267.1 1913.78
   268.4 1913.86     270 1913.97   270.7 1914.02   270.9 1914.04   274.2 1914.28
   275.9 1914.58   276.5  1914.7   277.8 1914.96   279.5 1915.56   280.8 1916.04
   281.4 1916.29     283 1917.07   283.3 1917.23     285 1918.11   285.8 1918.45
   288.3 1919.52   288.6 1919.66   290.8 1920.53   293.3 1921.68   295.6 1922.88
   295.7 1922.96   295.8 1922.99   298.2 1924.31   299.4 1924.95   300.7 1925.65
   302.5 1926.57     303 1926.84   303.6  1927.1
BR U #Mann= 4
       0     .04  159.77     .04  168.93     .04   181.5      .1
BR D #Sta/Elev= 170
       0 1913.21     1.8 1912.59     5.5 1911.48     8.1 1910.75     8.8 1910.54
    10.6 1910.25    12.4 1909.99    15.9 1909.79    19.4 1909.44    20.8 1909.27
    22.9 1908.98    24.3 1908.85    25.8 1908.82    26.4 1908.77    28.4 1908.69
    29.9 1908.58    33.4 1908.41      36 1908.33      37 1908.27    40.5  1908.1
    42.6 1907.97    46.2 1907.73      51 1907.43    53.8 1907.24    65.1 1906.68
    71.6 1906.31    76.6 1906.14    79.3 1905.99    82.7 1905.74    86.2 1905.35
    89.3 1904.86    89.7  1904.8    90.5 1904.67    91.9 1904.45    93.2 1904.27
    94.4 1904.25    96.7 1904.27    99.5 1904.43   100.2 1904.47   101.9 1904.52
     102 1904.52   103.7 1904.57   107.3 1904.63   107.6 1904.63   110.8  1904.6
   115.9 1904.48   117.8 1904.41   119.8 1904.38   121.3 1904.36   128.3 1904.41
   132.5 1904.38   134.2 1904.39   138.9 1904.44   142.4 1904.45   142.7 1904.44
   143.3 1904.42   145.2 1904.34   145.3 1904.34   145.9  1904.3   147.7 1903.91
   149.5 1903.35   150.1 1903.01   151.4 1902.16   152.6 1901.34   153.2 1900.91
  153.85 1900.47   154.7 1899.89   155.1 1899.67   156.8 1898.66   157.5 1898.38
     160  1897.6   160.4 1897.51   161.5  1897.5   162.5 1897.49     164 1897.51
   164.9 1897.77   166.9 1898.53   167.4 1898.82   167.7 1898.89   168.21899.311
  169.49 1900.39   171.3 1901.92   172.3  1902.6   174.6 1903.75   174.8 1903.83
   174.9 1903.86   175.1 1903.89   177.3 1904.26   178.5 1904.36   181.9 1904.45
   182.1 1904.46   182.5 1904.47   184.7  1904.5   187.2 1904.52   190.5 1904.57
   192.2 1904.58   196.5 1904.57   201.3  1904.6   202.1  1904.6   203.7 1904.62
   204.6 1904.64   206.6 1904.73   207.1 1904.78   207.3 1904.82   207.8 1904.95
   209.5 1905.31     212 1905.98   214.3 1906.71   214.5 1906.77   219.5 1908.39
   221.7 1909.06     222 1909.15   222.7 1909.34   224.5 1909.75   225.2 1909.92
   226.9 1910.27   227.3 1910.34   228.8 1910.64   230.7 1910.94   231.9  1911.1
   232.4 1911.16   233.8 1911.31   234.4 1911.37     236 1911.53   236.9 1911.59
   238.8 1911.68   239.4  1911.7   239.6  1911.7   240.3 1911.68   241.8 1911.66
   243.2 1911.63   244.3  1911.6   246.8 1911.59     254    1912   259.2 1912.24
   259.8 1912.28   261.2 1912.36   264.2 1912.64   266.3 1912.86   266.7  1912.9
   268.4 1913.07   269.2 1913.18     271 1913.46   271.6 1913.57   272.8 1913.83
   274.1 1914.16   275.5 1914.54   276.6 1914.84     279  1915.5   279.1 1915.53
   279.1 1915.54   282.7 1916.57   284.1 1917.03   285.8 1917.64   286.3 1917.84
   286.5 1917.93     289 1918.99   289.9 1919.36   291.5 1919.94   293.5 1920.63
     294 1920.77   295.1 1921.07   296.5 1921.44   297.1 1921.61   298.7 1922.06
     299 1922.12   300.7 1922.64   301.5  1922.9   303.1 1923.54   303.6 1923.72
BR D #Mann= 4
       0     .04   156.8     .04   166.9     .04   178.5      .1
BC Design=,, 0 ,, 0 ,,,,,,
BC Use User HTab Curves=0
BC User HTab FreeFlow(D)= 0

Type RM Length L Ch R = 1 ,22665   ,109.5,109.7,109.6
XS GIS Cut Line= 4
     1981777.345      250424.669     1981725.262      250289.035
     1981710.071      250256.483     1981660.158      250144.721
#Sta/Elev= 30
       0 1913.21     8.8 1910.54    22.9 1908.98    79.3 1905.99    86.2 1905.35
    93.2 1904.27   107.3 1904.63   145.9  1904.3   149.5 1903.35   156.8 1898.66
   160.4 1897.51   162.5 1897.49     164 1897.51   166.9 1898.53   167.7 1898.89
   172.3  1902.6   174.9 1903.86   178.5 1904.36   206.6 1904.73     212 1905.98
   222.7 1909.34   230.7 1910.94   238.8 1911.68   246.8 1911.59   259.2 1912.24
   269.2 1913.18   272.8 1913.83   282.7 1916.57   293.5 1920.63   303.6 1923.72
#Mann= 4 ,-1 , 0
       0     .04       0   156.8    .045       0   166.9     .04       0
   178.5      .1       0
#XS Ineff= 2 , 0
        152.1667 1901.95173.8333         1901.95
Permanent Ineff=
       F       F
#Block Obstruct= 2 ,-1
    4.76   23.48  1931.7   23.91   56.23 1928.89
Bank Sta=156.8,166.9
XS Rating Curve= 0 ,0
Exp/Cntr=0.5,0.3

Type RM Length L Ch R = 1 ,22556   ,198.8,197.2,194.6
XS GIS Cut Line= 3
     1981890.242       250408.48     1981800.181       250186.04
     1981740.502      250067.768
#Sta/Elev= 30
       0 1917.35     9.1 1913.14    16.2 1910.64    26.8 1908.47    37.5 1907.22
    69.3 1904.05    97.4 1902.59   108.3 1900.71   157.8  1899.9   164.9 1899.48
   168.4    1898     171 1896.18   175.5 1894.14     179 1893.93   189.7 1896.09
   196.7 1897.63   200.3 1897.68   218.3 1896.26   246.5 1896.01   253.2 1897.96
   262.9 1903.08   268.6 1904.35   289.8 1904.38   301.7 1905.17     320 1907.14
   333.8  1909.4   353.7 1916.48   360.6 1918.72     368 1920.17   372.5    1922
#Mann= 4 ,-1 , 0
       0     .04       0   157.8      .1       0     171    .045       0
   189.7      .1       0
#XS Ineff= 2 , 0
                          200.11          1899.3
Permanent Ineff=
       F       F
#Block Obstruct= 4 ,-1
   31.94   67.05 1927.88   194.5   207.2 1917.21  274.59  284.17 1924.67
  291.12  318.78 1926.98
Bank Sta=171,189.7
XS Rating Curve= 0 ,0
Exp/Cntr=0.3,0.1

Type RM Length L Ch R = 1 ,22358   ,137.5,141.9,142.2
XS GIS Cut Line= 3
     1982073.618      250279.356     1981966.196      250107.915
     1981892.412      249984.217
#Sta/Elev= 30
       0 1898.98    35.7 1894.82      59 1893.56    70.6 1891.79    81.4 1889.39
   105.2 1889.39   124.2 1891.77   132.5 1890.15   140.3 1887.32   144.1 1885.94
     148 1885.41   151.9 1885.61   156.61887.075   159.6 1888.07   163.5 1888.19
   171.2  1886.1   175.1  1885.8   181.4 1887.22   190.6 1890.77   197.5 1891.52
     210 1890.95   221.3 1888.56   225.1 1888.35   242.2 1890.36   259.5 1895.45
   293.4 1900.29   301.5 1903.36   316.8 1906.37   324.4  1909.3   346.3 1916.38
#Mann= 5 ,-1 , 0
       0      .1       0    81.4      .1       0   140.3    .045       0
   156.6     .04       0     180      .1       0
#XS Ineff= 2 , 0
          137.24 1891.78   161.3         1890.43
Permanent Ineff=
       F       F
#Block Obstruct= 4 ,-1
   18.82   57.01    1917  112.72  136.91 1910.09  263.69  275.44 1917.61
  283.54  292.37 1920.06
Bank Sta=140.3,156.6
XS Rating Curve= 0 ,0
Exp/Cntr=0.3,0.1

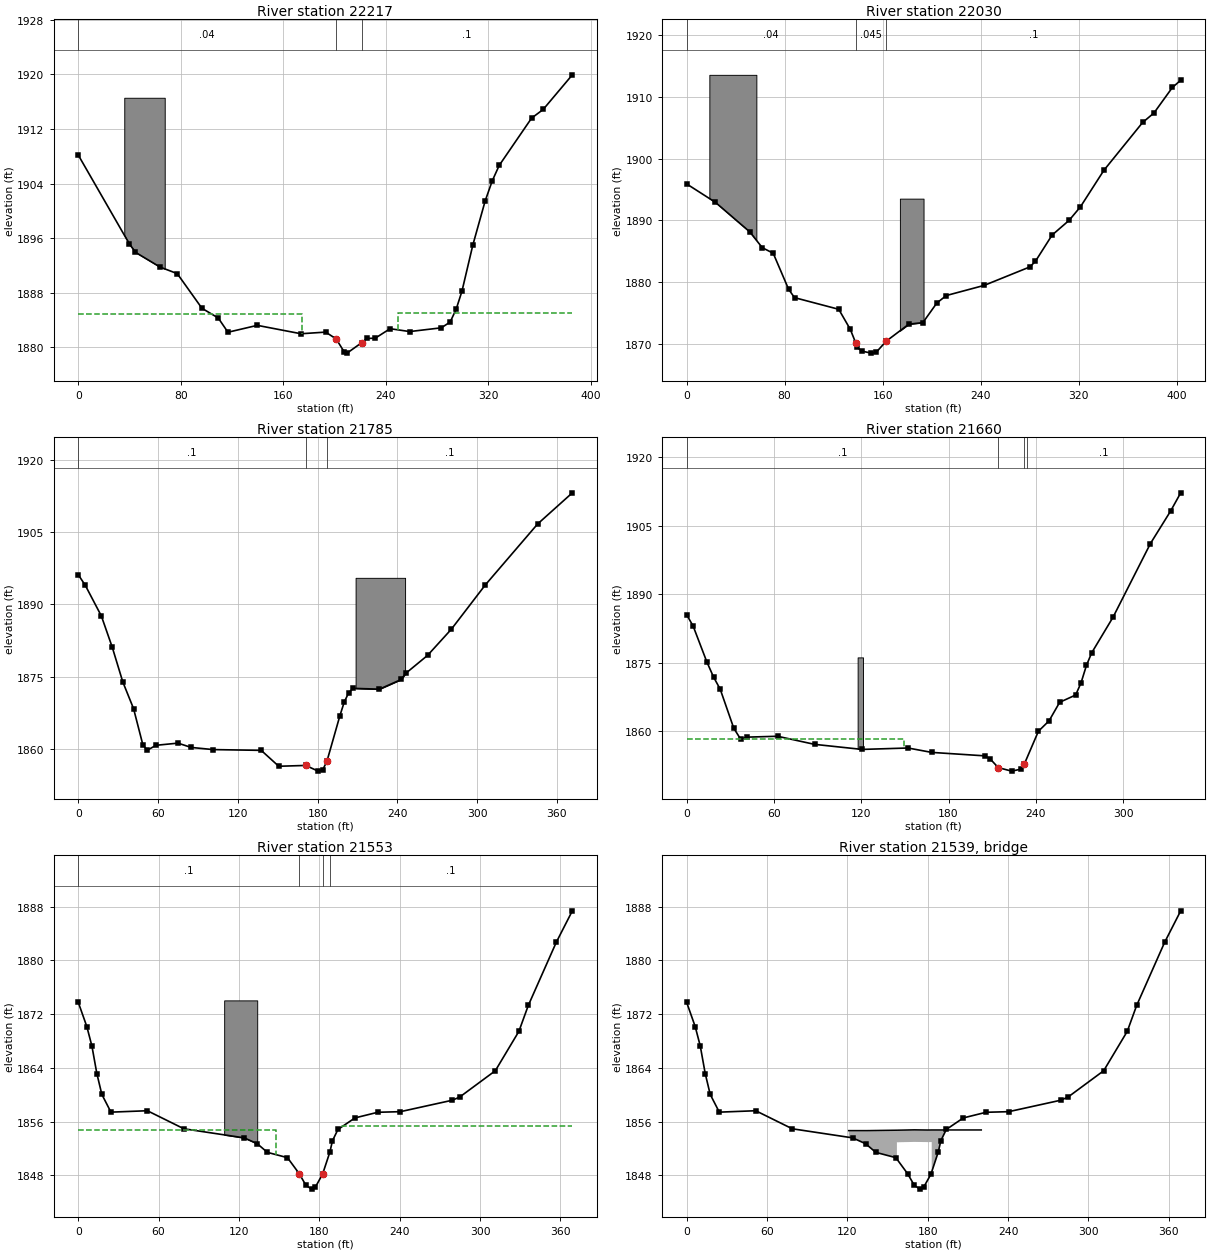
Type RM Length L Ch R = 1 ,22217   ,181.5,186.4,182.9
XS GIS Cut Line= 3
     1982198.401      250234.868     1982072.533      250022.195
     1981988.983      249911.518
#Sta/Elev= 30
       0  1908.2    39.9 1895.18    44.7 1893.94    63.9 1891.78    77.3 1890.82
    96.6 1885.74   109.3 1884.32   116.9 1882.23   139.8 1883.24   173.9 1882.01
   193.2 1882.25   201.41881.249   207.6 1879.37   209.9 1879.17   221.41880.712
   225.4 1881.32   231.9 1881.36   243.5 1882.75   258.8 1882.33   283.5 1882.88
   290.4 1883.73   295.1 1885.61   299.6 1888.24   308.1 1895.01   317.7 1901.45
   323.2 1904.39   328.7 1906.68     354 1913.61     363 1914.87   385.8 1919.95
#Mann= 3 ,-1 , 0
       0     .04       0   201.4    .045       0   221.4      .1       0
#XS Ineff= 2 , 0
             175 1884.95     250         1885.01
Permanent Ineff=
       F       F
#Block Obstruct= 1 ,-1
   35.93   67.52 1916.59
Bank Sta=201.4,221.4
XS Rating Curve= 0 ,0
Exp/Cntr=0.3,0.1

Type RM Length L Ch R = 1 ,22030   ,256.6,244.8,225.2
XS GIS Cut Line= 3
     1982347.056      250158.913     1982235.294      249971.197
     1982105.085      249839.903
#Sta/Elev= 30
       0 1895.93    23.5 1892.94    51.6 1888.14    61.8 1885.58    70.7 1884.68
    83.3 1878.83    88.1 1877.48   124.2 1875.59   133.6 1872.35   138.11870.122
   139.4  1869.4   143.1  1868.8   150.9 1868.48   154.7  1868.6     1631870.422
   181.4 1873.18   192.9 1873.43   204.3 1876.61     212 1877.82     243 1879.47
   280.2 1882.46   284.7 1883.35   298.4 1887.63   312.3 1890.02   321.5  1892.2
   340.7 1898.14   372.3 1905.89   381.6 1907.44   396.6 1911.57   403.4 1912.74
#Mann= 3 ,-1 , 0
       0     .04       0   138.1    .045       0     163      .1       0
#Block Obstruct= 2 ,-1
   18.56   56.95 1913.62  174.13  193.44 1893.54
Bank Sta=138.1,163
XS Rating Curve= 0 ,0
Exp/Cntr=0.3,0.1

Type RM Length L Ch R = 1 ,21785   ,109.3,125,127.1
XS GIS Cut Line= 5
     1982488.115       249873.541982452.34280783249847.946104917
1982374.34795995249840.2564720271982180.00503821 249824.29793035
1982126.92118984249813.179569527
#Sta/Elev= 30
       0 1896.15     5.3 1893.94    17.4 1887.57    25.6 1881.07    33.5  1873.9
    41.6 1868.35    48.6 1860.84    51.9 1859.72    58.5 1860.74      75 1861.19
    84.9  1860.3   101.4 1859.85   137.6 1859.69   150.8 1856.39   171.1 1856.56
   180.4 1855.38   183.7 1855.57     187  1857.4   196.8  1866.9   200.1 1869.76
   203.4 1871.64   206.7 1872.56   226.5 1872.39   242.9  1874.4   246.2 1875.65
   262.7  1879.4   280.6 1884.83   306.1 1894.01   345.5 1906.68   371.6 1913.14
#Mann= 3 , 0 , 0
       0      .1       0   171.1    .045       0     187      .1       0
#Block Obstruct= 1 ,-1
  208.59  245.81  1895.5
Bank Sta=171.1,187
XS Rating Curve= 0 ,0
Exp/Cntr=0.3,0.1

Type RM Length L Ch R = 1 ,21660   ,85.3,107.3,112.2
Node Name=G
XS GIS Cut Line= 3
      1982480.52      249845.328     1982394.799      249759.608
     1982199.486      249661.952
#Sta/Elev= 30
       0 1885.54     4.5 1883.03    13.9  1875.2    18.5  1871.9    23.1 1869.22
    32.4  1860.7    37.1 1858.31    41.7 1858.74    62.5 1858.93    87.9 1857.16
   120.6 1856.05   152.2 1856.36   168.4  1855.4   205.1 1854.64   208.7 1853.95
   214.21852.069   223.4  1851.3   229.9 1851.74     2321852.763   241.8 1860.03
   249.1  1862.3   256.4 1866.36   267.4 1867.96   271.1 1870.63   274.8 1874.43
   278.4 1877.18   293.1 1884.99   318.8 1901.11   332.6 1908.18   339.6  1912.2
#Mann= 4 ,-1 , 0
       0      .1       0   214.2    .045       0     232      .1       0
   234.2      .1       0
#XS Ineff= 2 , 0
          149.46 1858.35
Permanent Ineff=
       F       F
#Block Obstruct= 1 ,-1
  117.54  121.23 1876.19
Bank Sta=214.2,232
XS Rating Curve= 0 ,0
Exp/Cntr=0.5,0.3

Type RM Length L Ch R = 1 ,21553   ,35.6,40.7,39.3
XS GIS Cut Line= 4
     1982472.604      249821.641     1982380.644      249654.269
     1982332.901      249595.676     1982254.776      249529.487
#Sta/Elev= 30
       0 1873.77     6.4 1870.15    10.2 1867.25    13.9 1863.14    17.6 1860.05
    24.4  1857.4    51.6 1857.61    78.9 1854.92   123.9 1853.57   133.7 1852.69
   141.2 1851.41   156.2 1850.62     165 1848.23  169.96 1846.51   174.21845.932
  176.93  1846.2   182.4 1848.15   187.9 1851.47   189.8 1853.14   193.9 1854.82
   206.6 1856.54   223.6 1857.38   240.5 1857.47   279.4 1859.18   284.8 1859.65
   311.4 1863.57     329 1869.44     336 1873.29   356.9  1882.7   368.9 1887.39
#Mann= 4 ,-1 , 0
       0      .1       0     165    .045       0   182.4      .1       0
   187.9      .1       0
#XS Ineff= 2 , 0
             148 1854.67     197         1855.39
Permanent Ineff=
       F       F
#Block Obstruct= 1 ,-1
  108.95  133.62 1874.05
Bank Sta=165,182.4
XS Rating Curve= 0 ,0
Exp/Cntr=0.5,0.3

Type RM Length L Ch R = 3 ,21539   ,,,
BEGIN DESCRIPTION:
Unnamed Road
Survey ID: MAC250
END DESCRIPTION:
Bridge Culvert--1,0,-1,-1, 0
Deck Dist Width WeirC Skew NumUp NumDn MinLoCord MaxHiCord MaxSubmerge Is_Ogee
14,12,2.6,0, 10, 10, , , 0.98, 0, 0,0,,
     121     135     146     157     157     170     180     183     183     220
1854.6511854.6511854.682 1854.71 1854.711854.7661854.7381854.7471854.7471854.747
                                 1852.911852.9661852.9381852.947
     121     135     146     159     159     170     180     185     185     220
1854.6511854.6511854.682 1854.71 1854.711854.7661854.7381854.7471854.7471854.747
                                 1852.911852.9661852.9381852.947
BR Coef=-1 , 1 , 0 ,, 0 ,,,0.8,0,1.2,0,
WSPro=,,,, 1 ,,,, 0 ,,,, 0 ,,,,-1 ,-1 ,-1 , 0 , 0 , 0 , 0 , 0
BR U #Sta/Elev= 30
       0 1873.77     6.4 1870.15    10.2 1867.25    13.9 1863.14    17.6 1860.05
    24.4  1857.4    51.6 1857.61    78.9 1854.92   123.9 1853.57   133.7 1852.69
   141.2 1851.41   156.2 1850.62     165 1848.23  169.96 1846.51   174.21845.932
  176.93  1846.2   182.4 1848.15   187.9 1851.47   189.8 1853.14   193.9 1854.82
   206.6 1856.54   223.6 1857.38   240.5 1857.47   279.4 1859.18   284.8 1859.65
   311.4 1863.57     329 1869.44     336 1873.29   356.9  1882.7   368.9 1887.39
BR U #Mann= 4
       0      .1     165     .04   182.4      .1   187.9      .1
BR D #Sta/Elev= 30
       0 1897.47     5.2 1895.91    20.2  1890.3    24.7 1888.19    29.5 1885.33
    39.6 1878.63    46.4 1874.73    51.2 1870.58    60.1 1861.17    66.9 1856.32
    70.6 1855.83    87.5 1855.91   109.2 1854.75     125 1854.54   154.9 1853.06
   158.7 1851.08   162.4 1847.45   162.4 1847.42   166.1 1846.72   169.1 1846.63
   173.6 1846.91   175.9 1847.44   184.9  1850.1   200.3 1852.77   236.6 1855.58
   294.5 1857.41   323.5  1857.5   349.3 1864.87   356.7 1867.43   368.9    1871
BR D #Mann= 4
       0      .1   162.4     .04   175.9     .04   184.9     .04
BC Design=,, 0 ,, 0 ,,,,,,
BC Use User HTab Curves=0
BC User HTab FreeFlow(D)= 0

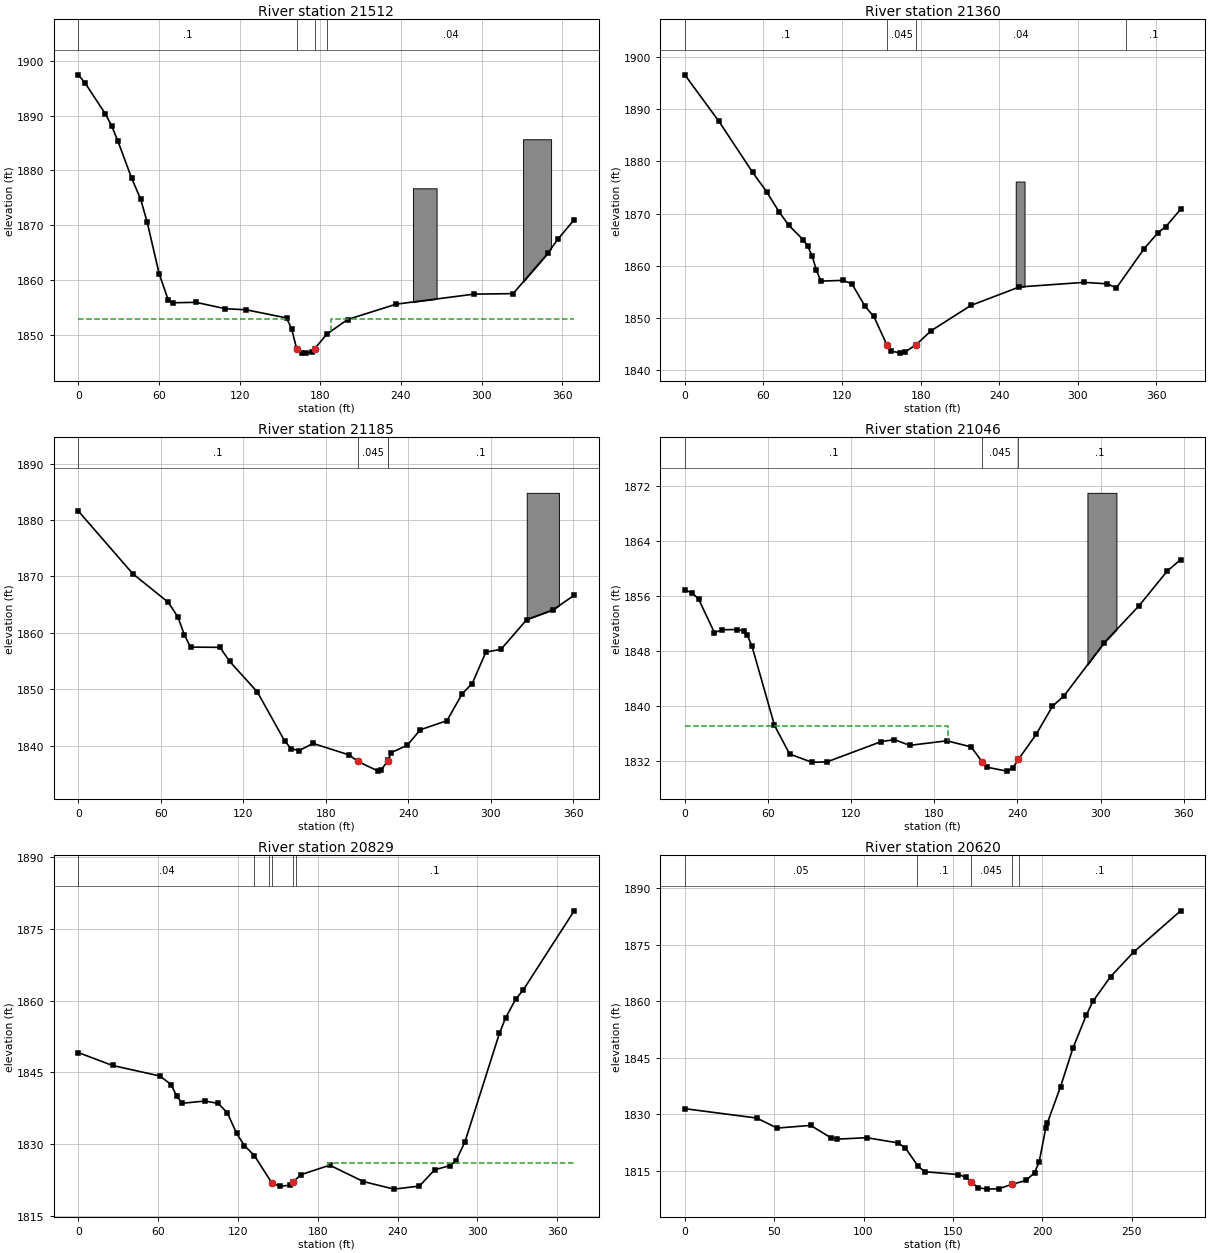
Type RM Length L Ch R = 1 ,21512   ,163.6,152.2,139.5
XS GIS Cut Line= 4
     1982509.496      249820.557     1982417.536      249653.184
     1982369.793      249594.591     1982291.668      249528.402
#Sta/Elev= 30
       0 1897.47     5.2 1895.91    20.2  1890.3    24.7 1888.19    29.5 1885.33
    39.6 1878.63    46.4 1874.73    51.2 1870.58    60.1 1861.17    66.9 1856.32
    70.6 1855.83    87.5 1855.91   109.2 1854.75     125 1854.54   154.9 1853.06
   158.7 1851.08   162.4 1847.45   162.4 1847.42   166.1 1846.72   169.1 1846.63
   173.6 1846.91   175.9 1847.44   184.9  1850.1   200.3 1852.77   236.6 1855.58
   294.5 1857.41   323.5  1857.5   349.3 1864.87   356.7 1867.43   368.9    1871
#Mann= 4 ,-1 , 0
       0      .1       0   162.4    .045       0   175.9     .04       0
   184.9     .04       0
#XS Ineff= 2 , 0
        155.6667 1852.94188.3333         1852.94
Permanent Ineff=
       F       F
#Block Obstruct= 2 ,-1
  248.98  266.55 1876.74   330.9  351.74  1885.7
Bank Sta=162.4,175.9
XS Rating Curve= 0 ,0
Exp/Cntr=0.5,0.3

Type RM Length L Ch R = 1 ,21360   ,166.7,175.2,179.7
XS GIS Cut Line= 4
     1982661.726249617.8589149211982584.69725598249575.439570174
1982417.62172424249537.1640847211982307.12626306249492.501032842
#Sta/Elev= 30
       0 1896.58    26.1 1887.65    51.7 1877.92    62.4 1874.21      72 1870.31
    79.5 1867.71    90.4 1864.97    93.8 1863.76    97.2 1861.89   100.5  1859.1
   103.9 1857.05   120.7 1857.19   127.5 1856.55   137.6 1852.22   144.3 1850.27
   154.4 1844.77   157.7 1843.65   164.5 1843.25   167.8 1843.41   176.7 1844.89
     188 1847.53   218.3 1852.38   255.4 1855.93   304.7 1856.81   322.4 1856.53
   329.5 1855.75   350.7 1863.28   361.3 1866.36   367.3 1867.51   378.5 1870.82
#Mann= 4 ,-1 , 0
       0      .1       0   154.4    .045       0   176.7     .04       0
   336.8      .1       0
#Block Obstruct= 1 ,-1
  252.62  259.34 1876.13
Bank Sta=154.4,176.7
XS Rating Curve= 0 ,0
Exp/Cntr=0.3,0.1

Type RM Length L Ch R = 1 ,21185   ,138.3,139.3,140.4
XS GIS Cut Line= 2
     1982697.533      249529.573      1982405.65      249317.985
#Sta/Elev= 30
       0  1881.6    39.5  1870.5    65.4 1865.41    72.4  1862.8    77.1 1859.64
    81.6 1857.47     103 1857.42     110 1854.94   130.2 1849.49   149.9 1840.87
   154.6 1839.48   160.4  1839.1   170.7 1840.38   196.9 1838.34   203.21837.192
   218.1 1835.47   220.4 1835.72   224.81837.275   225.1 1837.43   227.5 1838.75
   239.2 1840.07   248.6  1842.8     268 1844.42   279.1 1849.19   286.4 1851.01
   296.3 1856.58   307.3 1857.07   326.1 1862.36     345 1864.06   360.5 1866.65
#Mann= 4 ,-1 , 0
       0      .1       0   203.2    .045       0   224.8      .1       0
   225.1      .1       0
#XS Ineff= 2 , 0
          170.14 1839.72
Permanent Ineff=
       F       F
#Block Obstruct= 1 ,-1
  326.03   349.4 1884.83
Bank Sta=203.2,224.8
XS Rating Curve= 0 ,0
Exp/Cntr=0.3,0.1

Type RM Length L Ch R = 1 ,21046   ,207.4,216.2,218.1
XS GIS Cut Line= 2
     1982760.467      249415.641     1982476.179      249198.627
#Sta/Elev= 30
       0 1856.83     5.2 1856.46      10 1855.51    21.4 1850.64    26.8 1851.07
    37.7  1851.1    42.8 1850.87    45.1 1850.29    48.5 1848.65    64.7 1837.16
    75.6 1832.99    91.7 1831.79   102.5 1831.84   141.6 1834.79   151.2 1835.08
   162.3 1834.25   189.1 1834.91   206.6 1834.02   214.61831.834   218.3 1831.06
   232.3  1830.5   236.6 1830.92   240.61832.197   253.5 1835.85   265.2 1839.92
   273.7 1841.48   302.6 1849.19   327.4 1854.49     348  1859.6   357.7 1861.28
#Mann= 3 ,-1 , 0
       0      .1       0   214.6    .045       0   240.6      .1       0
#XS Ineff= 2 , 0
             190    1837
Permanent Ineff=
       F       F
#Block Obstruct= 1 ,-1
  290.47  311.38 1870.99
Bank Sta=214.6,240.6
XS Rating Curve= 0 ,0
Exp/Cntr=0.3,0.1

Type RM Length L Ch R = 1 ,20829   ,203.4,209.8,204.6
XS GIS Cut Line= 3
     1982872.229      249266.986     1982705.129      249129.183
      1982570.58      249049.973
#Sta/Elev= 30
       0 1849.15    25.7 1846.45    61.2 1844.26    69.7 1842.47    73.9 1840.03
    78.2 1838.55    95.2 1839.01     105 1838.53     112 1836.57   118.9 1832.27
   124.9 1829.67   132.3 1827.61   145.51821.843   151.6 1821.17     159  1821.4
   161.61822.161   167.5 1823.62     189 1825.59   214.2 1822.17   237.3 1820.58
   256.4 1821.22   267.8 1824.62   279.2 1825.49   283.9 1826.52   290.6 1830.46
   316.5 1853.15   321.1 1856.38   328.7 1860.31   334.3  1862.2   372.7 1878.81
#Mann= 6 ,-1 , 0
       0     .04       0   132.3      .1       0   143.4      .1       0
   145.5    .045       0   161.6      .1       0   163.4      .1       0
#XS Ineff= 2 , 0
                          187.49         1826.03
Permanent Ineff=
       F       F
Bank Sta=145.5,161.6
XS Rating Curve= 0 ,0
Exp/Cntr=0.3,0.1

Type RM Length L Ch R = 1 ,20620   ,106.5,111.5,109.5
XS GIS Cut Line= 2
     1982873.315      249056.483     1982631.344      248920.849
#Sta/Elev= 30
       0  1831.5    40.3 1829.01    51.6 1826.35    70.4 1827.06    81.7 1823.79
    85.4 1823.41   101.7  1823.8   119.3 1822.41   123.4 1821.07   130.6 1816.19
   134.3 1814.76   153.1    1814   157.2 1813.32   159.91812.072   164.3 1810.51
   169.2 1810.14   175.7 1810.24   182.8 1811.39   190.9 1812.44   195.7 1814.52
   198.3 1817.44     202 1826.49   202.9 1827.77   210.2 1837.32   217.1  1847.5
   224.6 1856.33   228.3 1859.98   238.2 1866.56   251.1 1873.07   277.4 1884.03
#Mann= 5 ,-1 , 0
       0     .05       0     130      .1       0   159.9    .045       0
   182.8      .1       0   187.1      .1       0
Bank Sta=159.9,182.8
XS Rating Curve= 0 ,0
Exp/Cntr=0.3,0.1

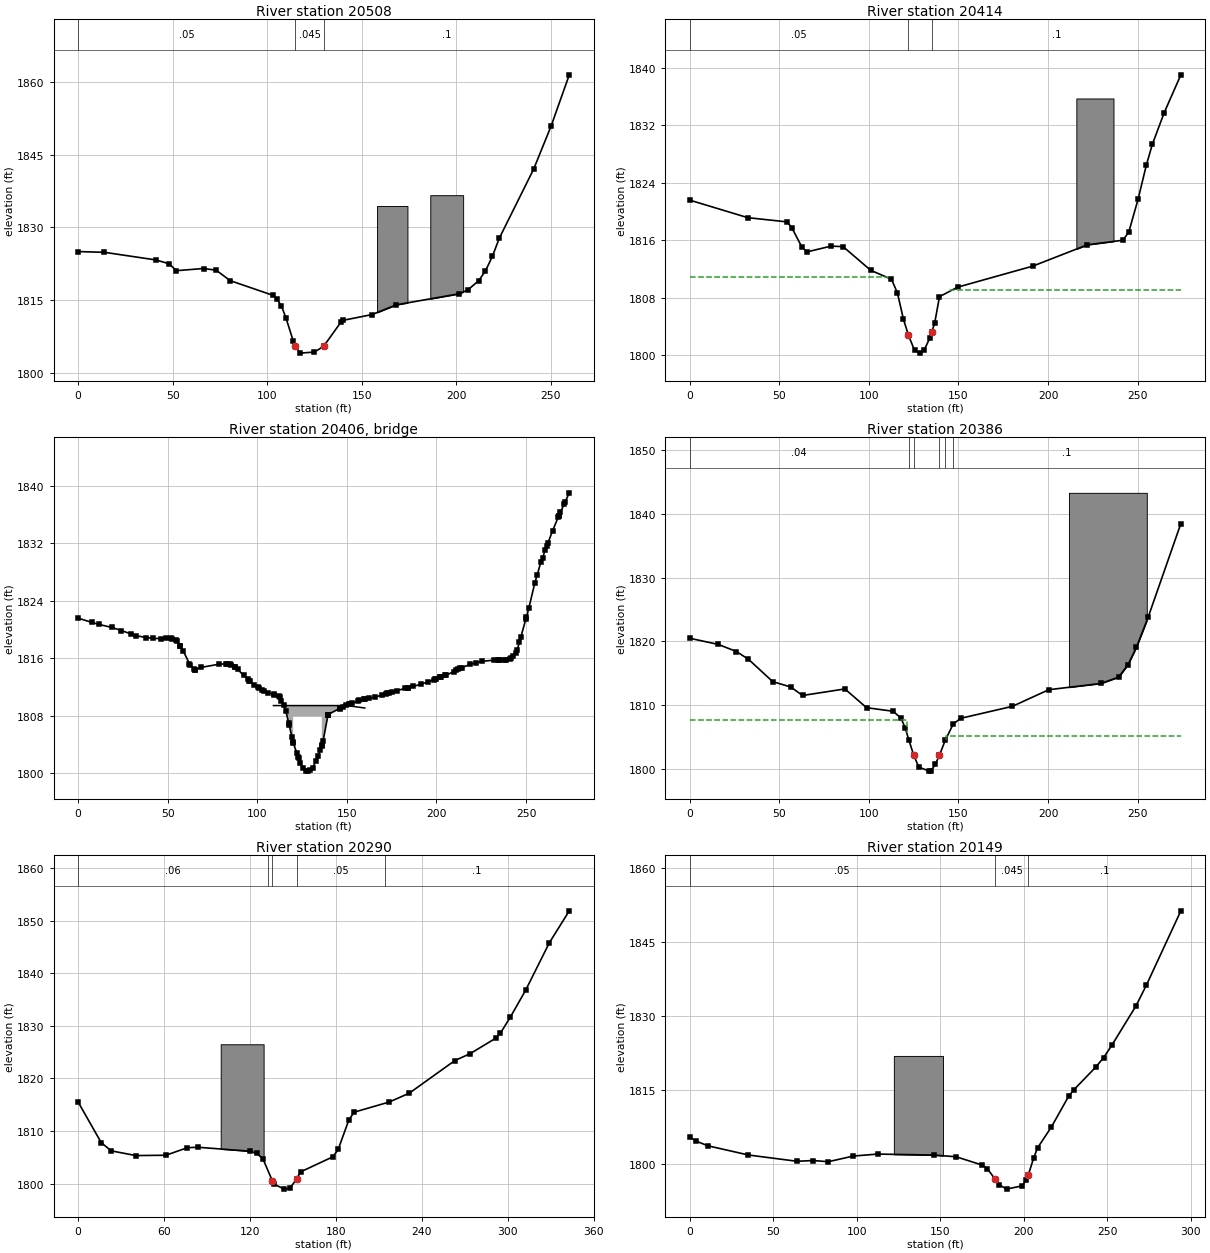
Type RM Length L Ch R = 1 ,20508   ,96.9,93.7,91
XS GIS Cut Line= 2
     1982917.802      248960.997     1982683.427      248849.235
#Sta/Elev= 30
       0 1825.03    13.9 1824.88    41.1 1823.31    48.2 1822.51    51.9 1821.09
    66.4 1821.54      73 1821.19    80.4 1819.04   102.8 1816.04     105  1815.3
   107.5 1813.83   109.9 1811.36   113.7 1806.66   114.91805.588   117.3 1804.09
   124.9 1804.31   129.81805.478   139.1 1810.55   140.2 1810.86   155.4 1812.04
   168.2 1814.05   201.2 1816.31   205.9 1817.07   211.8 1819.02   215.4 1821.05
   219.1 1824.09   222.7 1827.79   240.9 1842.06   250.2 1851.02   259.7 1861.48
#Mann= 3 , 0 , 0
       0     .05       0   114.9    .045       0   129.8      .1       0
#Block Obstruct= 2 ,-1
  158.07  174.14 1834.44  186.21  203.59 1836.66
Bank Sta=114.9,129.8
XS Rating Curve= 0 ,0
Exp/Cntr=0.5,0.3

Type RM Length L Ch R = 1 ,20414   ,27.8,28.6,28
XS GIS Cut Line= 3
     1982990.616       248862.44     1982848.255      248830.322
     1982720.651      248818.169
#Sta/Elev= 30
       0 1821.57    32.4 1819.13    54.4 1818.54      57 1817.73    62.6 1815.04
    65.5 1814.37    78.9 1815.17    85.6  1815.1     101 1811.81   112.6 1810.56
   115.9 1808.68   119.3 1804.99   122.1 1802.75  125.53 1800.65   128.51800.284
  130.83  1800.7     134 1802.38   135.1 1803.26   136.7 1804.44   139.4 1808.14
   149.5 1809.46   191.5 1812.39     222 1815.36   241.8 1815.99   245.1 1817.18
   250.2 1821.67   254.9  1826.5   258.2 1829.34   264.8 1833.73   274.1    1839
#Mann= 3 , 0 , 0
       0     .05       0   122.1    .045       0   135.1      .1       0
#XS Ineff= 2 , 0
           110.5 1810.84   145.5         1809.05
Permanent Ineff=
       F       F
#Block Obstruct= 1 ,-1
  215.78  236.51 1835.71
Bank Sta=122.1,135.1
XS Rating Curve= 0 ,0
Exp/Cntr=0.5,0.3

Type RM Length L Ch R = 3 ,20406   ,,,
BEGIN DESCRIPTION:
Unnamed Road
Survey ID: MAC2540
END DESCRIPTION:
Bridge Culvert--1,0,-1,-1, 0
Deck Dist Width WeirC Skew NumUp NumDn MinLoCord MaxHiCord MaxSubmerge Is_Ogee
8,12,2.6,0, 7, 7, , , 0.98, 0, 0,0,,
     109     120     120     136     136     150     160
1809.4041809.4041809.4041809.4041809.4041809.4041809.066
                1807.9041807.904
     109     124     124     140     140     150     160
1809.4041809.4041809.4041809.4041809.4041809.4041809.066
                1807.9041807.904
BR Coef=-1 , 1 , 0 ,, 0 ,,,0.8,0,1.2,0,
WSPro=,,,, 1 ,,,, 0 ,,,, 0 ,,,,-1 ,-1 ,-1 , 0 , 0 , 0 , 0 , 0
BR U #Sta/Elev= 144
       0 1821.57     7.7 1820.97    11.7 1820.69    18.7 1820.28    24.2 1819.84
    29.7 1819.35    32.4 1819.13    37.9 1818.87    41.9 1818.76    46.1 1818.72
    48.9 1818.77      52 1818.77    52.6 1818.68    54.4 1818.54    55.4 1818.33
      57 1817.73    57.1 1817.68    58.7 1816.99    62.1 1815.25    62.6 1815.04
    64.8 1814.48    65.4 1814.38    65.5 1814.37    68.8 1814.72    78.9 1815.17
    82.3  1815.2      83 1815.17    84.6 1815.16    85.6  1815.1    87.3  1814.8
    87.4 1814.79      89 1814.46    92.4 1813.59    94.7 1813.09    95.5 1812.89
    95.7 1812.85    98.3 1812.33   100.4 1811.94     101 1811.81   102.5 1811.58
   103.8 1811.43   105.8 1811.22   109.3 1810.97   109.6 1810.94     112 1810.67
   112.6 1810.56   113.4 1810.05   114.7 1809.47   115.9 1808.68   117.5 1806.96
   117.8 1806.65   119.3 1804.99     1201804.321   120.2 1804.13   122.1 1802.75
   122.6  1802.3     123 1802.16  123.93 1801.43  125.53 1800.65  127.33 1800.35
   128.51800.284  129.64 1800.41  130.83  1800.7  132.67 1801.67     134 1802.38
   135.1 1803.26   136.1 1803.84   136.2 1803.94   136.7 1804.44   139.4 1808.06
   139.4 1808.14   139.5 1808.16   145.9 1808.98   146.2 1809.01   147.8 1809.24
   149.5 1809.46   150.9 1809.57   151.5  1809.6   152.8  1809.7   156.1 1810.05
   156.9 1810.11   159.4 1810.26   159.9 1810.28   162.4 1810.42   165.9 1810.59
   169.7 1810.88   171.9 1811.07   172.5 1811.12   173.3 1811.17   174.9 1811.26
   177.9 1811.46   182.4 1811.81     184 1811.89   184.2 1811.91     187 1812.07
   191.5 1812.39   195.2  1812.7   198.8 1813.02     199 1813.04   199.9 1813.13
     202 1813.33   202.2 1813.35   202.4 1813.37     205  1813.6   205.5 1813.64
   209.7 1814.14     211 1814.32   212.1 1814.46   213.4  1814.6     214 1814.67
   218.7 1815.12     222 1815.36   225.3 1815.55   231.9 1815.72   234.5 1815.69
   235.1 1815.69   235.2 1815.69   238.5 1815.73   238.9 1815.78   241.1 1815.92
   241.8 1815.99   242.5 1816.31   244.1 1816.78   245.1 1817.18   246.2 1818.18
   247.1 1818.96   249.8 1821.38   250.2 1821.67   251.6 1823.02   254.9  1826.5
   256.2 1827.57   258.2 1829.34   259.2 1829.98   260.7 1831.07   261.5 1831.61
   262.2 1832.03   264.8 1833.73     268 1835.66   268.1 1835.72   268.2 1835.77
   269.1 1836.27   271.2 1837.44   271.7 1837.68   274.1    1839
BR U #Mann= 3
       0     .05   122.1     .04   135.1      .1
BR D #Sta/Elev= 168
       0 1820.51     5.4 1820.25     9.3 1820.03      16 1819.54    22.7 1818.87
    26.1 1818.43    27.3 1818.23    28.5    1818    29.5 1817.82    30.1 1817.72
    32.8 1817.22    36.2 1816.21    37.1 1815.95    38.3  1815.6    39.5 1815.27
    42.9 1814.53    43.8 1814.33    46.3 1813.73    46.5  1813.7    47.8 1813.59
    50.2 1813.43      52 1813.31      53 1813.24    54.8 1813.04    56.4 1812.88
    57.5 1812.69    58.9 1812.43    59.7 1812.28    60.3 1812.15    62.7 1811.61
      63 1811.56    63.1 1811.55    65.8 1811.44    66.4 1811.48    67.5 1811.63
    68.5 1811.78    69.8 1811.94    71.2 1812.04    76.2 1812.34    76.5 1812.36
    76.7 1812.37    77.6 1812.41    79.9 1812.53    83.3 1812.64    84.9 1812.62
      85 1812.62    86.6 1812.58    87.7 1812.41    89.3 1812.06      90 1811.92
    90.5  1811.8    92.5 1811.15    93.2 1810.93    93.4 1810.88    95.9 1810.17
    96.7 1809.99    97.9 1809.81    98.7 1809.65   101.4 1809.38   102.3 1809.37
   103.4  1809.3   106.8 1809.29   106.9 1809.28   107.4 1809.28   109.7 1809.24
   113.5 1809.09   115.2 1808.84   115.3  1808.8   116.9 1808.52   117.9 1808.02
   119.7 1806.81   120.3 1806.47   120.6 1806.12   122.3  1804.6   123.4 1803.61
   123.6 1803.42     124 1803.13   124.91802.324   126.1 1801.25     127 1800.67
  127.82 1800.36  128.94 1800.03  130.39 1799.85   133.71799.728  134.72 1799.78
     137  1800.8   137.1 1800.81   137.1 1800.82   139.41802.235   140.4 1802.85
   141.4 1803.57   142.6 1804.54   143.8 1805.46   145.3 1806.28   145.9 1806.54
   147.1 1807.11   148.3 1807.43   149.4 1807.63   150.4 1807.91   151.3 1807.99
     153 1808.12   154.3 1808.23     157 1808.44   160.3 1808.62   166.3 1808.93
   166.9 1808.96   167.6 1809.01   169.4 1809.11   170.2 1809.17   171.3 1809.23
   172.4 1809.28   173.5 1809.36   176.8 1809.58   178.4 1809.71   178.5 1809.73
   180.1 1809.86   187.4 1810.69     190 1811.04   193.1 1811.58   193.3 1811.61
   196.4 1812.05   199.9 1812.42   200.4 1812.46   202.5  1812.6   203.2 1812.65
   206.5 1812.76   209.8 1812.81   214.5 1813.02   219.6 1813.18   220.5 1813.19
   222.2 1813.19   222.9 1813.19   223.5 1813.21   226.2  1813.3   226.5 1813.31
   229.5 1813.44   232.5 1813.62   232.8 1813.64   236.1 1813.89   236.8 1814.02
   239.4 1814.43   240.5 1814.79   241.6 1815.12   242.7 1815.53   244.1 1816.18
   244.6 1816.38     246 1817.07   247.6 1818.03   247.7 1818.14   249.3  1819.1
   250.6    1820   251.4 1820.57   252.6 1821.43   255.9 1823.84   259.2 1826.42
   259.6 1826.78   262.5 1829.12   262.6 1829.25   264.1 1830.42   265.6 1831.61
   265.8 1831.72     266 1831.86   268.7 1834.18   269.1 1834.54   271.7 1836.59
   272.4 1837.15   273.2 1837.78   274.1 1838.44
BR D #Mann= 6
       0     .04   122.3     .04   124.9     .04   139.4     .04   142.6     .04
   147.1      .1
BC Design=,, 0 ,, 0 ,,,,,,
BC Use User HTab Curves=0
BC User HTab FreeFlow(D)= 0

Type RM Length L Ch R = 1 ,20386   ,92,95.3,99.3
XS GIS Cut Line= 3
     1983007.977      248839.002     1982865.616      248806.884
     1982738.012      248794.731
#Sta/Elev= 30
       0 1820.51      16 1819.54    26.1 1818.43    32.8 1817.22    46.3 1813.73
    56.4 1812.88      63 1811.56    86.6 1812.58    98.7 1809.65   113.5 1809.09
   117.9 1808.02   120.3 1806.47   122.3  1804.6   124.91802.324  127.82 1800.36
   133.71799.728  134.72 1799.78   137.1 1800.81   139.41802.235   142.6 1804.54
   147.1 1807.11   151.3 1807.99   180.1 1809.86   200.4 1812.46   229.5 1813.44
   239.4 1814.43   244.6 1816.38   249.3  1819.1   255.9 1823.84   274.1 1838.44
#Mann= 6 ,-1 , 0
       0     .04       0   122.3     .04       0   124.9    .045       0
   139.4     .04       0   142.6     .04       0   147.1      .1       0
#XS Ineff= 2 , 0
        121.1667 1807.67142.8333          1805.2
Permanent Ineff=
       F       F
#Block Obstruct= 1 ,-1
  211.64  255.09 1843.25
Bank Sta=124.9,139.4
XS Rating Curve= 0 ,0
Exp/Cntr=0.5,0.3

Type RM Length L Ch R = 1 ,20290   ,137.8,141.5,145.1
XS GIS Cut Line= 3
     1983049.096      248797.151     1982888.506      248707.091
     1982740.936      248648.497
#Sta/Elev= 30
       0 1815.51    16.1  1807.8    23.1 1806.22    40.3 1805.32    61.3 1805.38
    76.3 1806.82    83.7  1806.9   119.9 1806.15   124.7 1805.75     129 1804.72
   135.71800.471   136.7 1799.89     144 1798.94   147.8  1799.1   152.61800.863
   155.3 1802.22   177.9 1805.09   181.6  1806.5   188.9 1812.01   192.6 1813.56
   217.1 1815.49   231.2 1817.18     263 1823.38   273.6 1824.68   291.5 1827.62
   294.8 1828.58   301.8 1831.66   312.4 1836.73     329 1845.78   342.9 1851.85
#Mann= 5 ,-1 , 0
       0     .06       0   132.6     .06       0   135.7    .045       0
   152.6     .05       0  214.12      .1       0
#Block Obstruct= 1 ,-1
   99.56  129.52 1826.48
Bank Sta=135.7,152.6
XS Rating Curve= 0 ,0
Exp/Cntr=0.3,0.1

Type RM Length L Ch R = 1 ,20149   ,129,131.7,134
XS GIS Cut Line= 2
      1983118.54      248727.707     1982902.612      248528.054
#Sta/Elev= 30
       0 1805.34       4 1804.57      11 1803.63    35.2 1801.77    64.2  1800.5
    73.9 1800.65      83 1800.41      98 1801.56   112.5 1801.96   146.3 1801.76
   159.6 1801.41   175.3 1799.71   178.2    1799   182.71796.953   185.2 1795.78
   189.7 1794.85   199.1 1795.52   201.4 1796.65   202.71797.667     206 1801.19
   208.3 1803.22   216.5 1807.41   226.9 1813.68   229.9 1814.96     243 1819.55
   247.8 1821.49   252.7 1823.99   267.2    1832   273.4 1836.18   294.1  1851.3
#Mann= 3 ,-1 , 0
       0     .05       0   182.7    .045       0   202.7      .1       0
#Block Obstruct= 1 ,-1
  122.25  151.65 1821.87
Bank Sta=182.7,202.7
XS Rating Curve= 0 ,0
Exp/Cntr=0.3,0.1