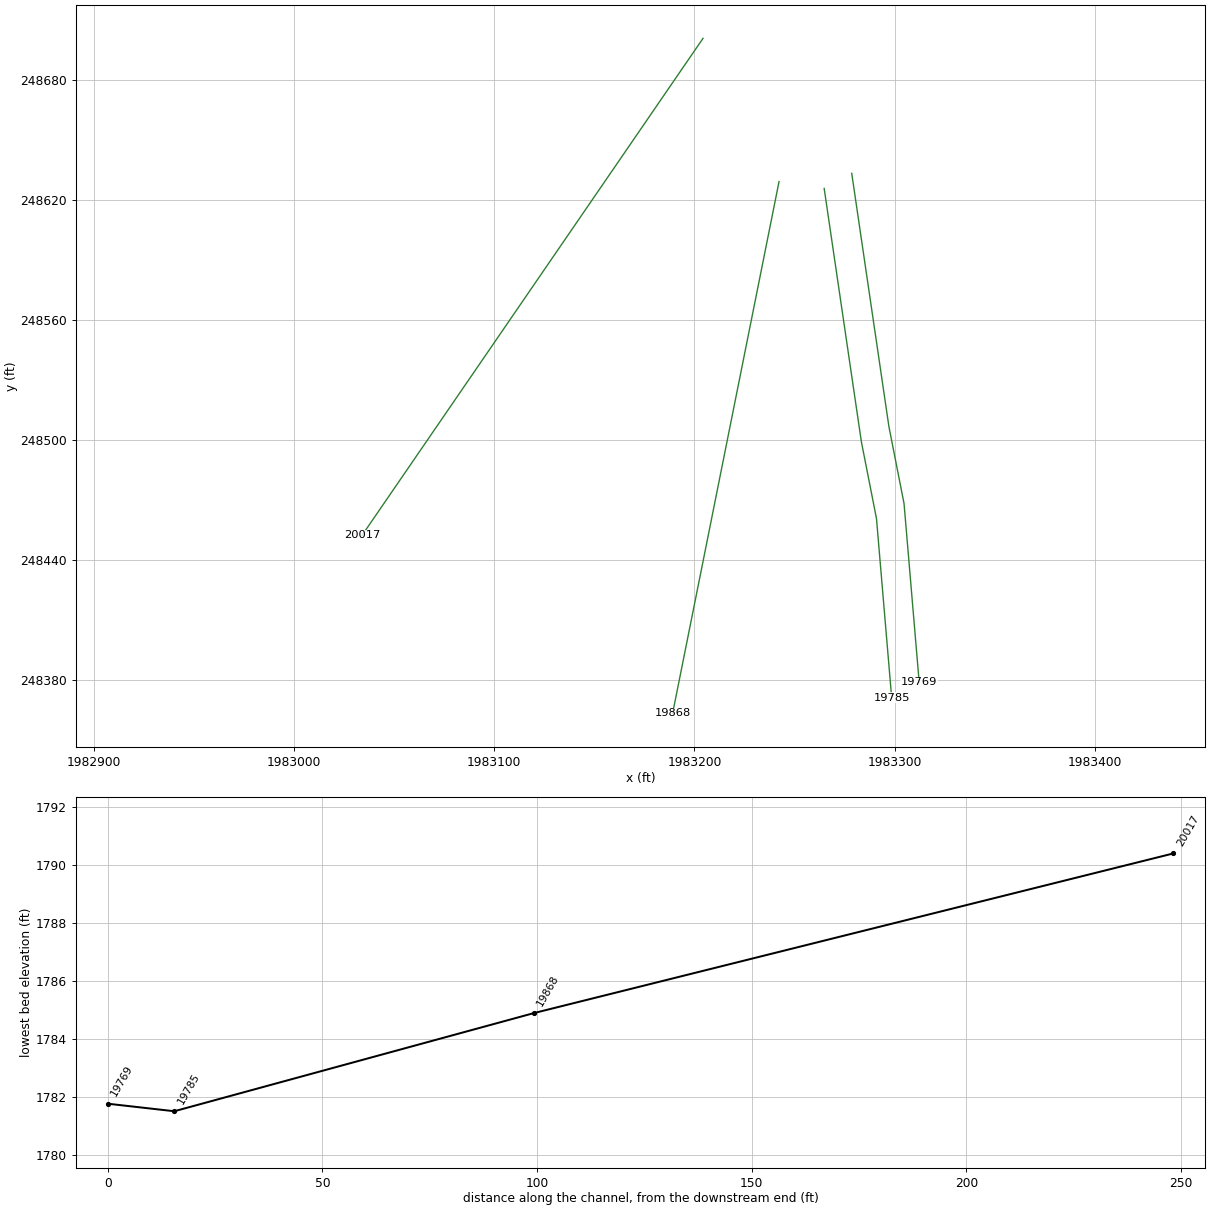
HEC-RAS study MADAMCK.prj: MADAMCK

--- MADAMCK.g01 (geometry) --- (continued)

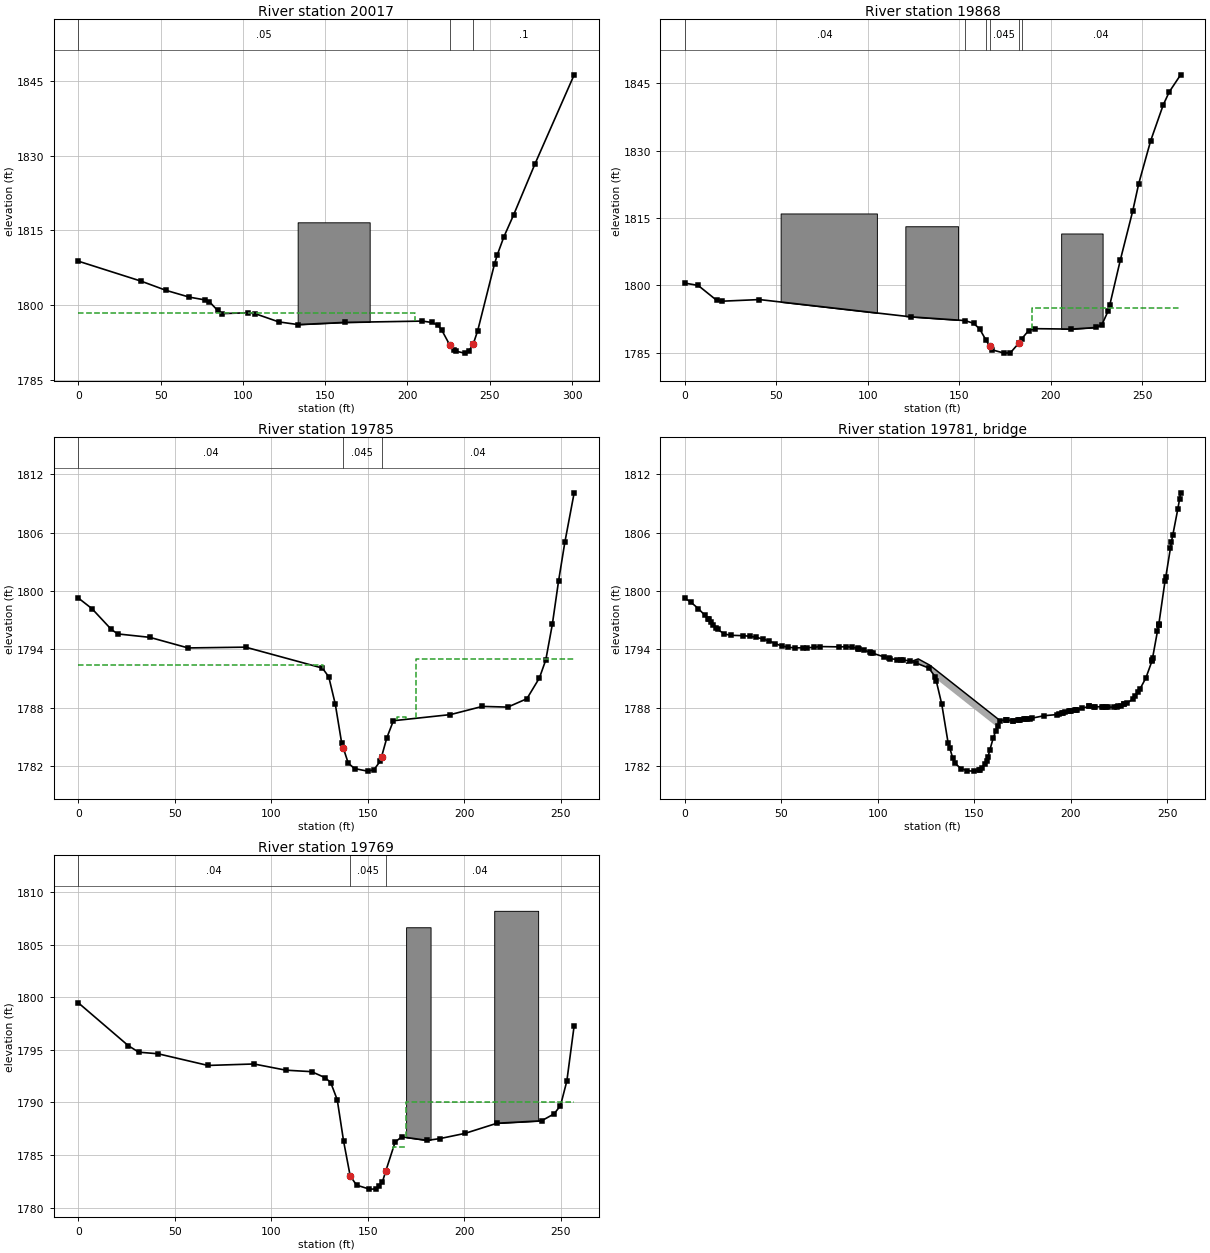
Type RM Length L Ch R = 1 ,20017   ,144.2,149,152.1
XS GIS Cut Line= 2
     1983204.261       248700.58     1983033.905      248452.099
#Sta/Elev= 30
       0 1808.84    38.2 1804.83    53.3 1802.99    67.5 1801.63    76.9 1801.08
    79.6 1800.73    84.6 1798.98    87.6 1798.33   102.9  1798.5   107.5 1798.31
   121.8 1796.67   133.6 1796.13   161.9 1796.57   209.1 1796.83   214.9 1796.55
   218.5 1796.01   220.9 1794.99   225.6  1792.1     228  1791.1   229.7 1790.78
   234.7 1790.41   237.4 1790.87     2401792.252   242.7 1794.93   252.9 1808.28
   254.6 1810.12   258.6 1813.72   264.5 1818.11   277.5 1828.34   301.3 1846.19
#Mann= 3 , 0 , 0
       0     .05       0   225.6    .045       0     240      .1       0
#XS Ineff= 2 , 0
          204.87 1798.37
Permanent Ineff=
       F       F
#Block Obstruct= 1 ,-1
  133.28  177.04 1816.63
Bank Sta=225.6,240
XS Rating Curve= 0 ,0
Exp/Cntr=0.3,0.1

Type RM Length L Ch R = 1 ,19868   ,79.1,83.7,86.8
XS GIS Cut Line= 2
     1983242.238      248628.966      1983189.07      248363.124
#Sta/Elev= 30
       0 1800.49     7.3 1799.97    17.4 1796.66    20.5 1796.46    40.8 1796.82
   123.6 1792.97   153.2 1792.14   157.9 1791.54   161.2 1790.28   164.6 1787.85
   166.61786.511   167.9 1785.64   174.6 1784.89     178 1784.96   182.91787.236
   184.1 1788.02     188 1789.92   191.3 1790.34   211.4 1790.24   224.8  1790.6
   228.1 1791.26   231.5 1794.31   232.4 1795.67   238.2 1805.74   244.9 1816.53
   248.2 1822.66   254.7 1832.17   261.6 1840.19   264.9 1843.09   271.1 1846.88
#Mann= 6 ,-1 , 0
       0     .04       0   153.2      .1       0   164.6      .1       0
   166.6    .045       0   182.9     .04       0   184.1     .04       0
#XS Ineff= 2 , 0
                             190            1795
Permanent Ineff=
       F       F
#Block Obstruct= 3 ,-1
    52.4  105.03    1816  120.59  149.41 1813.15  205.78  228.44 1811.54
Bank Sta=166.6,182.9
XS Rating Curve= 0 ,0
Exp/Cntr=0.5,0.3

Type RM Length L Ch R = 1 ,19785   ,15,15.5,15.4
XS GIS Cut Line= 4
1983264.78295942248625.5507347021983283.35809883248498.964599495
1983290.92574822248460.438384432 1983298.4933976248371.002528037
#Sta/Elev= 30
       0 1799.29     7.1 1798.19    17.1 1796.06    20.4  1795.6      37 1795.25
    56.9 1794.16    86.7 1794.24   126.5 1792.09   129.8 1791.19   133.2 1788.37
   136.5 1784.38   137.3  1783.9   139.9 1782.32   143.2 1781.76   149.9  1781.5
   153.2 1781.64   156.6 1782.55   157.21782.998   159.9 1784.92   163.3 1786.68
   192.9 1787.31   209.4 1788.15   222.6 1788.08   232.5 1788.94     239 1791.08
   242.3 1792.93   245.7  1796.6   248.9 1801.02   252.2 1805.05     257  1810.1
#Mann= 3 ,-1 , 0
       0     .04       0   137.3    .045       0   157.2     .04       0
#XS Ineff= 3 ,-1
       0     127 1792.39     165     170 1787.07     175     275    1793
Permanent Ineff=
       F       F       F
Bank Sta=137.3,157.2
XS Rating Curve= 0 ,0
Exp/Cntr(USF)=0,0
Exp/Cntr=0.5,0.3

Type RM Length L Ch R = 3 ,19781   ,,,
BEGIN DESCRIPTION:
Pedestrian Walkway
Survey ID: MAC230
END DESCRIPTION:
Bridge Culvert--1,0,-1,-1, 0
Deck Dist Width WeirC Skew NumUp NumDn MinLoCord MaxHiCord MaxSubmerge Is_Ogee
4,4,2.6,0, 8, 8, , , 0.98, 0, 0,0,,
     115     121     127     131     131     161     161     164
  1792.61793.0331792.386 1791.76 1791.76 1787.07 1787.07  1786.6
                                 1790.86 1786.17
     115     121     127     131     131     161     161     164
  1792.61793.0331792.386 1791.76 1791.76 1787.07 1787.07  1786.6
                                 1790.86 1786.17
BR Coef=-1 , 1 , 0 ,, 0 ,,,0.8,0,1.2,0,
WSPro=,,,, 1 ,,,, 0 ,,,, 0 ,,,,-1 ,-1 ,-1 , 0 , 0 , 0 , 0 , 0
BR U #Sta/Elev= 126
       0 1799.29     3.2 1798.85     7.1 1798.19    10.4 1797.51    11.9 1797.17
    12.3 1797.09    13.7 1796.79    14.8 1796.53    16.2 1796.26    17.1 1796.06
    20.4  1795.6    23.7 1795.46    30.3 1795.42    33.6 1795.36      37 1795.25
    40.3 1795.09    43.6 1794.88    46.9 1794.61    50.2 1794.36    53.5 1794.24
    56.9 1794.16    61.1 1794.18    63.5 1794.18    66.8 1794.22    70.1  1794.3
    80.1 1794.27    83.4 1794.28    86.7 1794.24    89.7 1794.11      90 1794.09
    90.1 1794.09    92.9 1793.93    95.8 1793.73    96.6 1793.67    97.8 1793.59
   103.3 1793.24   105.6 1793.11   106.6 1793.05   110.2 1792.97   112.3 1792.95
   113.1 1792.94   116.5 1792.81   119.9 1792.61   126.5 1792.09   129.8 1791.19
   130.4 1790.72   133.2 1788.37   136.5 1784.38   137.3  1783.9   138.8 1782.89
   139.9 1782.32   143.2 1781.76   146.5 1781.53   149.9  1781.5   152.7 1781.61
   153.2 1781.64     154 1781.85   155.5 1782.22   156.6 1782.55   157.21782.998
   158.1 1783.67   159.9 1784.92   161.1 1785.59   162.3 1786.16   163.3 1786.68
   166.6 1786.78   166.7 1786.78   167.2 1786.76   169.9 1786.68   170.1 1786.69
   172.7 1786.73   173.2 1786.74   173.7 1786.76   175.8 1786.81   176.5 1786.84
   177.3 1786.86   178.8  1786.9   179.8 1786.94   186.4  1787.2   192.9 1787.31
     194 1787.36   195.3 1787.43   196.2 1787.48     197 1787.53   198.9 1787.68
   199.5 1787.72     200 1787.73   202.5 1787.79   202.8 1787.79   203.1 1787.81
   206.1 1787.97   209.4 1788.15   209.7 1788.15   212.2 1788.12   212.7 1788.11
     216 1788.11   216.9  1788.1   218.3 1788.09   219.3 1788.08   222.6 1788.08
   224.1 1788.14   224.3 1788.16   225.9 1788.22   227.4 1788.35   227.7 1788.37
   229.2 1788.49   232.5 1788.94   233.4 1789.19   234.9 1789.67   235.8 1789.89
     239 1791.08   242.1 1792.79   242.3 1792.93   242.5 1793.17     245 1795.89
   245.6 1796.48   245.6 1796.53   245.7  1796.6   248.9 1801.02   249.3 1801.44
   251.7 1804.39   252.2 1805.05   252.9 1805.72   255.5 1808.39   256.5 1809.51
     257  1810.1
BR U #Mann= 3
       0     .04   137.3     .04   157.2     .04
BR D #Sta/Elev= 120
       0 1799.46     8.1 1798.32    11.4  1797.8    14.8 1797.25    17.5 1796.73
    18.1 1796.64    21.4 1796.23    22.1 1796.08    23.8  1795.8    24.7 1795.57
    25.9 1795.39    26.7  1795.3      28 1795.09    31.3 1794.77    34.7 1794.67
    41.3 1794.62    44.6  1794.5    51.2 1794.27    54.6 1794.13    57.9 1793.94
    61.2 1793.68    64.5 1793.58    67.2 1793.51    71.1  1793.5    74.5 1793.53
    77.8 1793.59    81.1 1793.63    81.6 1793.64    84.2 1793.69    84.4  1793.7
      91 1793.65    97.7  1793.5   104.3 1793.16   107.6 1793.06   114.2 1792.98
   120.9 1792.92   122.1 1792.87   124.2 1792.78   127.9 1792.35   129.9 1792.05
   130.8 1791.89   131.1 1791.76   133.5 1790.67   134.2 1790.25   137.5 1786.31
   140.9 1783.02   141.9 1782.73   143.6 1782.32   144.2 1782.14   144.7  1782.1
   146.9 1781.94   147.5 1781.91   147.6  1781.9   150.2 1781.77   150.9 1781.76
   154.3 1781.77   155.8 1782.07   157.6 1782.44   158.6 1783.02   159.31783.445
   161.4 1784.72   164.2 1786.23   164.3 1786.26   164.4 1786.27     167 1786.67
   167.2 1786.69   167.6 1786.73   168.4  1786.7     170 1786.64   170.9  1786.6
   173.1 1786.54   174.2 1786.51   175.5 1786.47   176.1 1786.46   177.5 1786.42
   179.1 1786.41   180.8 1786.39   187.4 1786.56   188.2 1786.59   189.9 1786.65
   190.7 1786.67     194 1786.85   197.1 1786.96   200.4 1787.06   200.5 1787.06
   200.7 1787.08   203.4 1787.33   203.8 1787.37   207.1 1787.59   207.9 1787.62
   209.5 1787.63   210.4 1787.66   211.5  1787.7   212.5 1787.74   213.7 1787.77
   215.6 1787.92     217 1788.02   226.9 1788.01   227.7 1788.01   229.5 1788.03
   233.1 1788.06   233.8 1788.07   236.8 1788.16   237.5 1788.18   239.9 1788.25
   240.1 1788.25   240.3 1788.28   242.9 1788.57   243.3 1788.62   243.9 1788.66
   245.9 1788.85   246.6 1788.91   249.9 1789.69   251.1 1790.49     252 1791.17
   253.2 1792.02   254.7 1794.04     255 1794.56   256.5  1796.6     257 1797.29
BR D #Mann= 3
       0     .04   140.9     .04   159.3     .04
BC Design=,, 0 ,, 0 ,,,,,,
BC Use User HTab Curves=0
BC User HTab FreeFlow(D)= 0

Type RM Length L Ch R = 1 ,19769   ,80.6,81.1,82.1
XS GIS Cut Line= 4
1983278.54232195248633.1183840891983297.11746135248506.532248883
1983304.68511074 248468.006033821983312.25276013248378.570177424
#Sta/Elev= 30
       0 1799.46    25.9 1795.39    31.3 1794.77    41.3 1794.62    67.2 1793.51
      91 1793.65   107.6 1793.06   120.9 1792.92   127.9 1792.35   130.8 1791.89
   134.2 1790.25   137.5 1786.31   140.9 1783.02   144.2 1782.14   150.9 1781.76
   154.3 1781.77   155.8 1782.07   157.6 1782.44   159.31783.445   164.2 1786.23
   167.6 1786.73   180.8 1786.39   187.4 1786.56   200.5 1787.06     217 1788.02
   240.1 1788.25   246.6 1788.91   249.9 1789.69   253.2 1792.02     257 1797.29
#Mann= 3 ,-1 , 0
       0     .04       0   140.9    .045       0   159.3     .04       0
#XS Ineff= 3 ,-1
       0     129 1790.86     163     170  1785.8     170     275    1790
Permanent Ineff=
       F       F       F
#Block Obstruct= 2 ,-1
  169.89  182.57 1806.64  215.57  238.33  1808.2
Bank Sta=140.9,159.3
XS Rating Curve= 0 ,0
Exp/Cntr(USF)=0,0
Exp/Cntr=0.5,0.3