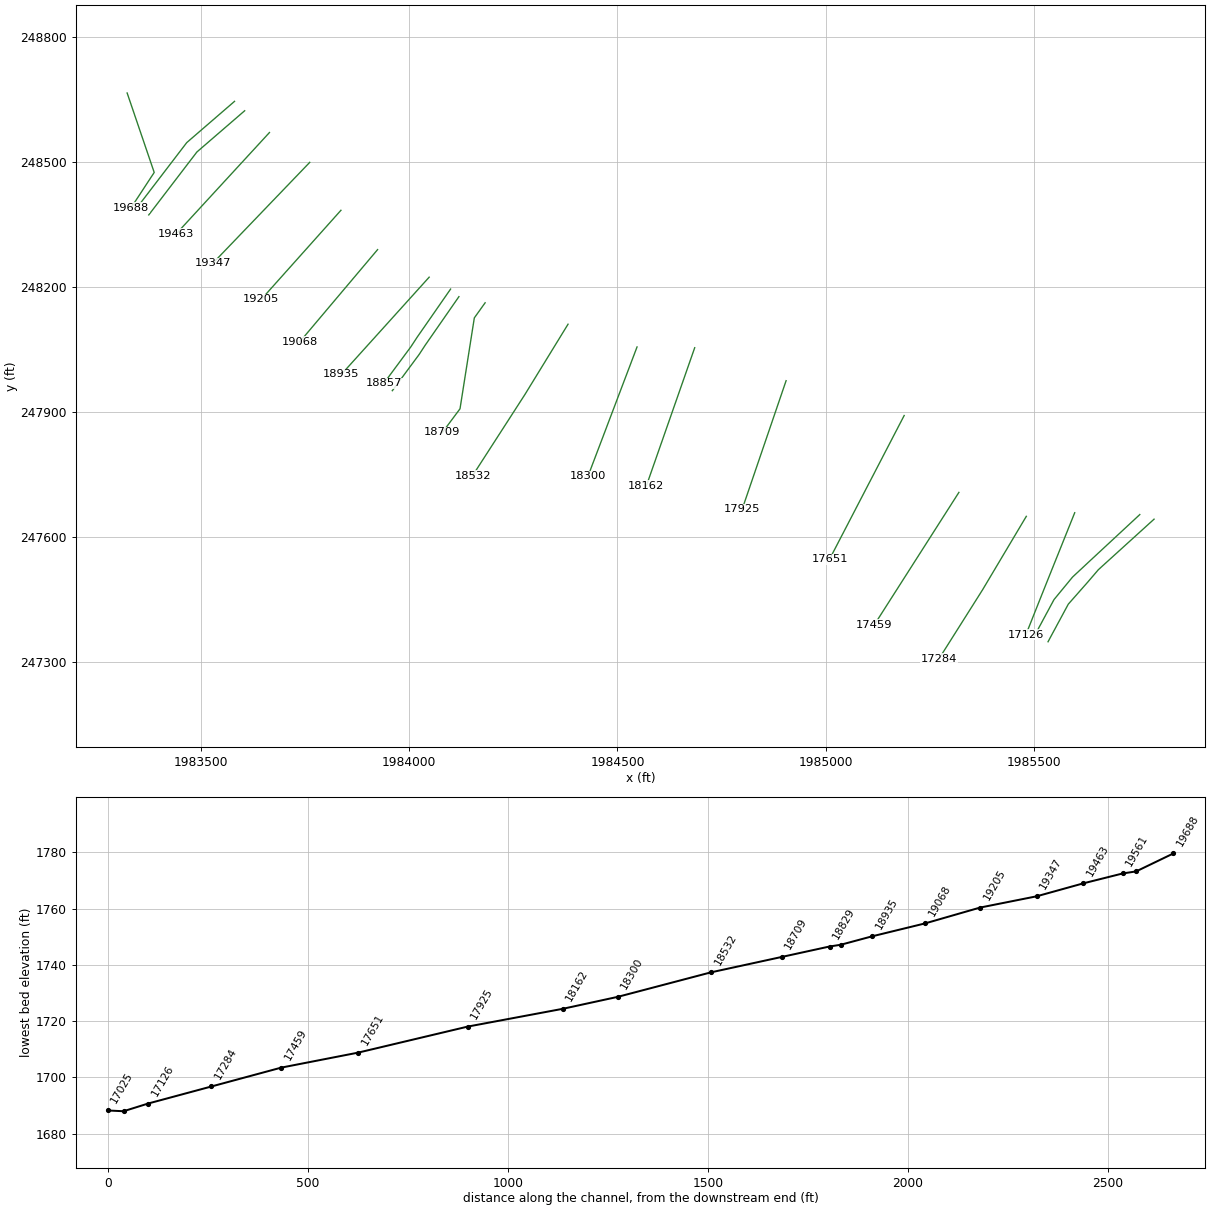
HEC-RAS study MADAMCK.prj: MADAMCK

--- MADAMCK.g01 (geometry) --- (continued)

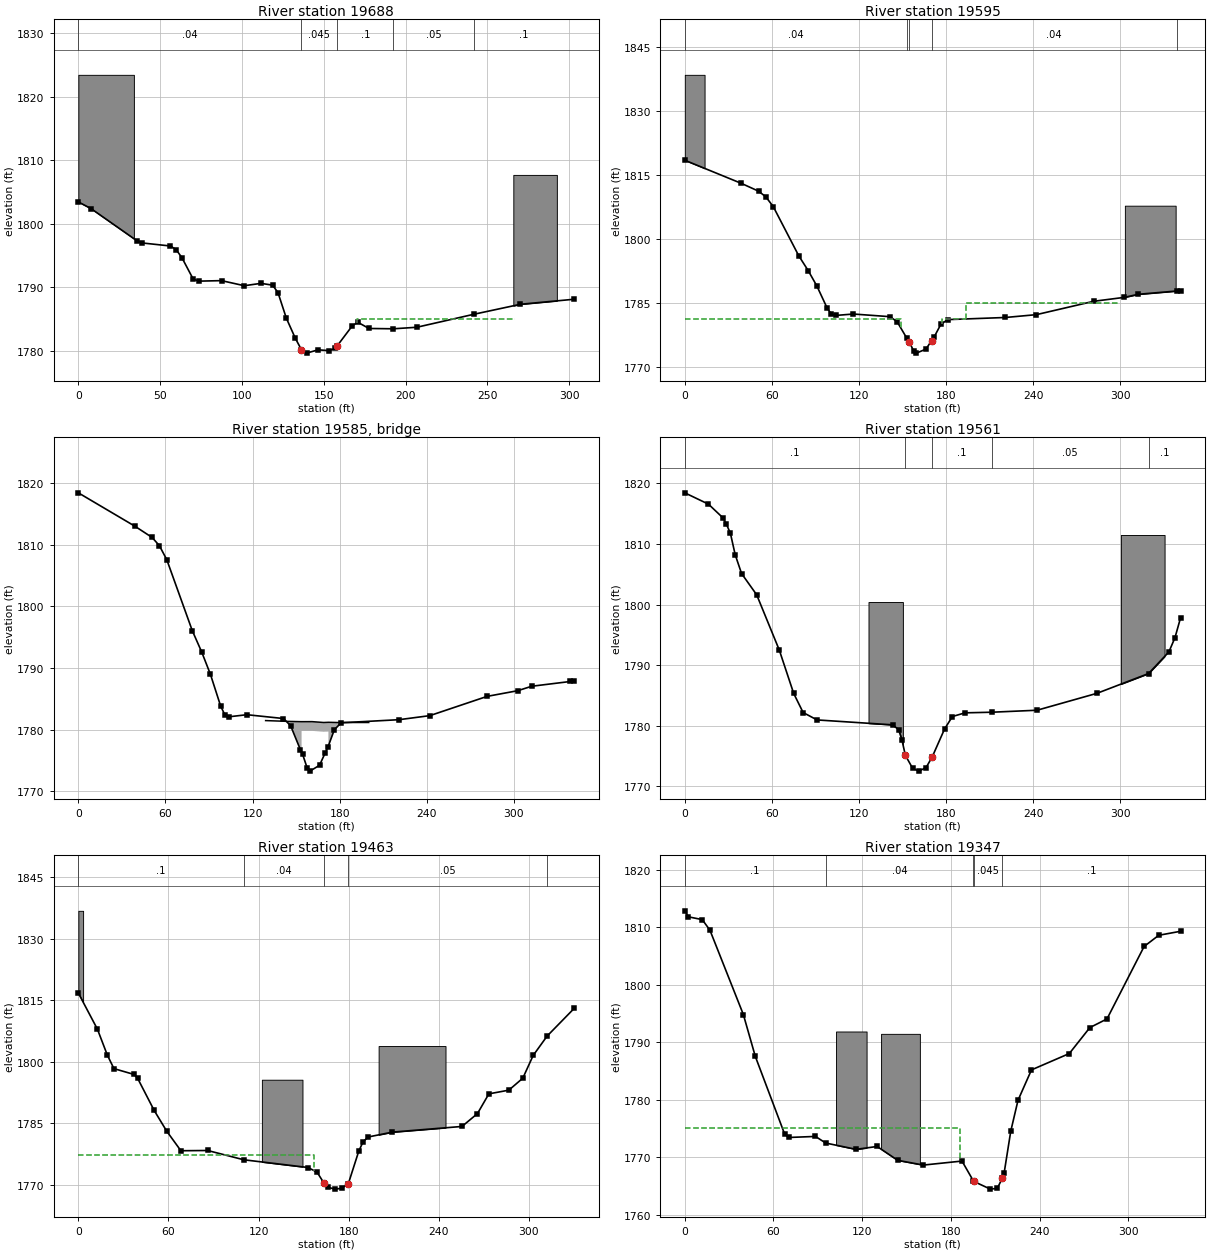
Type RM Length L Ch R = 1 ,19688   ,104.4,93.2,80.1
XS GIS Cut Line= 3
1983324.03415591248665.2954455331983388.95965101248474.530523486
1983333.34289107248389.581155907
#Sta/Elev= 30
       0 1803.46     7.8  1802.4    35.6 1797.38      39    1797    56.3 1796.52
    59.8 1795.94    63.3 1794.68    70.2 1791.31    73.7 1790.99    87.5 1791.07
   101.4 1790.27   111.6 1790.64   118.7 1790.36     122 1789.19   127.1 1785.17
   132.6    1782   136.31780.219   139.5 1779.66   146.5 1780.18   153.4 1780.05
   156.9 1780.41   158.2 1780.81   167.3 1783.92   170.7 1784.53   177.6 1783.54
   192.5 1783.49   206.8 1783.73   241.8 1785.78   270.2 1787.35     303 1788.14
#Mann= 5 ,-1 , 0
       0     .04       0   136.3    .045       0   158.2      .1       0
   192.5     .05       0   241.8      .1       0
#XS Ineff= 1 ,-1
     170   266.7    1785
Permanent Ineff=
       F
#Block Obstruct= 2 ,-1
       0   33.95 1823.46  265.82  292.43 1807.71
Bank Sta=136.3,158.2
XS Rating Curve= 0 ,0
Exp/Cntr=0.5,0.3

Type RM Length L Ch R = 1 ,19595   ,33.6,33.7,33.1
XS GIS Cut Line= 4
     1983581.628      248645.171     1983467.044      248546.213
     1983444.475      248516.699     1983351.593      248395.171
#Sta/Elev= 30
       0 1818.43    38.9 1813.02    50.8 1811.19    55.8 1809.86    60.9 1807.59
    78.5 1796.05      85 1792.58      91 1788.96      98 1783.84     101 1782.35
     104 1782.09   116.1 1782.42   141.3  1781.8   146.2 1780.64   152.9 1776.77
   154.51775.977  157.58 1773.79   159.51773.264  166.11 1774.21     1701776.209
   171.9 1777.15   176.3 1779.97     181 1781.11   220.8 1781.61   242.1 1782.27
   281.6  1785.4   302.7 1786.32   312.3 1787.04   338.8 1787.81   341.5 1787.91
#Mann= 5 ,-1 , 0
       0     .04       0   152.9     .04       0   154.5    .045       0
     170     .04       0   338.8      .1       0
#XS Ineff= 3 ,-1
       0  148.75 1781.33  177.25  193.88 1781.16  193.88     300    1785
Permanent Ineff=
       F       F       F
#Block Obstruct= 2 ,-1
       0   13.62 1838.43   303.1  338.07 1807.79
Bank Sta=154.5,170
XS Rating Curve= 0 ,0
Exp/Cntr=0.5,0.3

Type RM Length L Ch R = 3 ,19585   ,,,
BEGIN DESCRIPTION:
Via Bennett Dr
Survey ID: MAC220
END DESCRIPTION:
Bridge Culvert--1,0,-1,-1, 0
Deck Dist Width WeirC Skew NumUp NumDn MinLoCord MaxHiCord MaxSubmerge Is_Ogee
12,14,2.6,0, 10, 10, , , 0.98, 0, 0,0,,
     129     145  153.75  153.75     161     169  172.25  172.25     178     200
1781.4651781.334 1781.29 1781.291781.2971781.156 1781.19 1781.191781.1561781.156
                         1779.791779.7971779.656 1779.69
     129     145  153.75  153.75     161     169  172.25  172.25     178     200
1781.4651781.334 1781.29 1781.291781.2971781.156 1781.19 1781.191781.1561781.156
                         1779.791779.7971779.656 1779.69
BR Coef=-1 , 1 , 0 ,, 0 ,,,0.8,0,1.2,0,
WSPro=,,,, 1 ,,,, 0 ,,,, 0 ,,,,-1 ,-1 ,-1 , 0 , 0 , 0 , 0 , 0
BR U #Sta/Elev= 30
       0 1818.43    38.9 1813.02    50.8 1811.19    55.8 1809.86    60.9 1807.59
    78.5 1796.05      85 1792.58      91 1788.96      98 1783.84     101 1782.35
     104 1782.09   116.1 1782.42   141.3  1781.8   146.2 1780.64   152.9 1776.77
   154.51775.977  157.58 1773.79   159.51773.264  166.11 1774.21     1701776.209
   171.9 1777.15   176.3 1779.97     181 1781.11   220.8 1781.61   242.1 1782.27
   281.6  1785.4   302.7 1786.32   312.3 1787.04   338.8 1787.81   341.5 1787.91
BR U #Mann= 5
       0     .04   152.9     .04   154.5     .04     170     .04   338.8      .1
BR D #Sta/Elev= 30
       0 1818.42    16.3 1816.55    26.3 1814.29    28.5 1813.32    31.4 1811.76
    34.7 1808.22    39.1 1805.11    49.5 1801.61    65.1 1792.48      75 1785.34
    81.5 1782.19    91.1 1780.97   143.1 1780.16   147.2 1779.39   149.5 1777.73
   151.8 1775.19  156.92 1772.99   161.21772.528   166.2 1773.12   170.5 1774.92
   178.9 1779.47   184.3 1781.53     193 1782.14   211.3 1782.24   242.6 1782.57
   283.9 1785.36   319.4 1788.62   333.4 1792.18   337.6 1794.53   341.5 1797.85
BR D #Mann= 5
       0      .1   151.8     .04   170.5      .1   211.3     .05   319.4      .1
BC Design=,, 0 ,, 0 ,,,,,,
BC Use User HTab Curves=0
BC User HTab FreeFlow(D)= 0

Type RM Length L Ch R = 1 ,19561   ,97.8,97.9,96.8
XS GIS Cut Line= 4
     1983605.933      248622.602      1983491.35      248523.643
      1983468.78      248494.129     1983375.899      248372.602
#Sta/Elev= 30
       0 1818.42    16.3 1816.55    26.3 1814.29    28.5 1813.32    31.4 1811.76
    34.7 1808.22    39.1 1805.11    49.5 1801.61    65.1 1792.48      75 1785.34
    81.5 1782.19    91.1 1780.97   143.1 1780.16   147.2 1779.39   149.5 1777.73
   151.9 1775.14  156.92 1772.99   161.21772.528   166.2 1773.12   170.5 1774.92
   178.9 1779.47   184.3 1781.53     193 1782.14   211.3 1782.24   242.6 1782.57
   283.9 1785.36   319.4 1788.62   333.4 1792.18   337.6 1794.53   341.5 1797.85
#Mann= 5 ,-1 , 0
       0      .1       0   151.9    .045       0   170.5      .1       0
   211.3     .05       0   319.4      .1       0
#XS Ineff= 2 , 0
          148.75  1777.5  177.25          1777.5
Permanent Ineff=
       F       F
#Block Obstruct= 2 ,-1
  126.52  150.21 1800.41  300.36  330.45 1811.47
Bank Sta=151.9,170.5
XS Rating Curve= 0 ,0
Exp/Cntr=0.5,0.3

Type RM Length L Ch R = 1 ,19463   ,117.5,116.7,117.9
XS GIS Cut Line= 2
     1983665.415      248570.372     1983441.891      248327.316
#Sta/Elev= 30
       0 1816.74    12.7 1807.95    19.3 1801.65    23.7 1798.35    37.1 1796.93
    39.5 1795.98    50.5 1788.18    58.9 1783.11    68.3 1778.37    86.1 1778.43
   110.2 1776.17     153 1774.29     159 1773.14   163.51770.542     166 1769.51
   170.8 1769.03   175.3 1769.22   179.8 1770.34   186.8 1778.32   189.7 1780.59
   193.1 1781.72   209.1  1782.9   255.5 1784.28   265.8 1787.41   273.4 1792.21
   286.7 1793.11     296 1796.02   302.9 1801.55   312.2 1806.27   330.2    1813
#Mann= 5 ,-1 , 0
       0      .1       0   110.2     .04       0   163.5    .045       0
   179.8     .05       0   312.2      .1       0
#XS Ineff= 2 , 0
          157.14 1777.44
Permanent Ineff=
       F       F
#Block Obstruct= 3 ,-1
       0    3.18 1836.74  122.24  149.27 1795.65  199.98  244.53 1803.84
Bank Sta=163.5,179.8
XS Rating Curve= 0 ,0
Exp/Cntr=0.3,0.1

Type RM Length L Ch R = 1 ,19347   ,141.4,141.8,141.8
XS GIS Cut Line= 2
     1983761.986      248498.757     1983529.782      248256.787
#Sta/Elev= 30
       0  1812.9     2.5 1811.85    11.8 1811.37      17 1809.53    39.6 1794.84
    47.7 1787.54    67.5 1774.03    70.5 1773.42    88.4  1773.6    95.3 1772.45
   115.9 1771.35   130.1 1771.85     144 1769.44   161.4 1768.61   187.5 1769.31
   195.1  1765.9   195.41765.775   206.7 1764.42   211.4 1764.56   214.91766.387
     216 1767.21   220.5 1774.52   225.4  1779.9   234.5 1785.19   260.1 1788.04
     274 1792.56   285.6 1794.07   310.7 1806.69   320.6 1808.64   335.4 1809.34
#Mann= 5 ,-1 , 0
       0      .1       0    95.3     .04       0   195.1     .04       0
   195.4    .045       0   214.9      .1       0
#XS Ineff= 2 , 0
             186    1775
Permanent Ineff=
       F       F
#Block Obstruct= 2 ,-1
   102.3  122.97 1791.88  132.77  159.01 1791.47
Bank Sta=195.4,214.9
XS Rating Curve= 0 ,0
Exp/Cntr=0.3,0.1

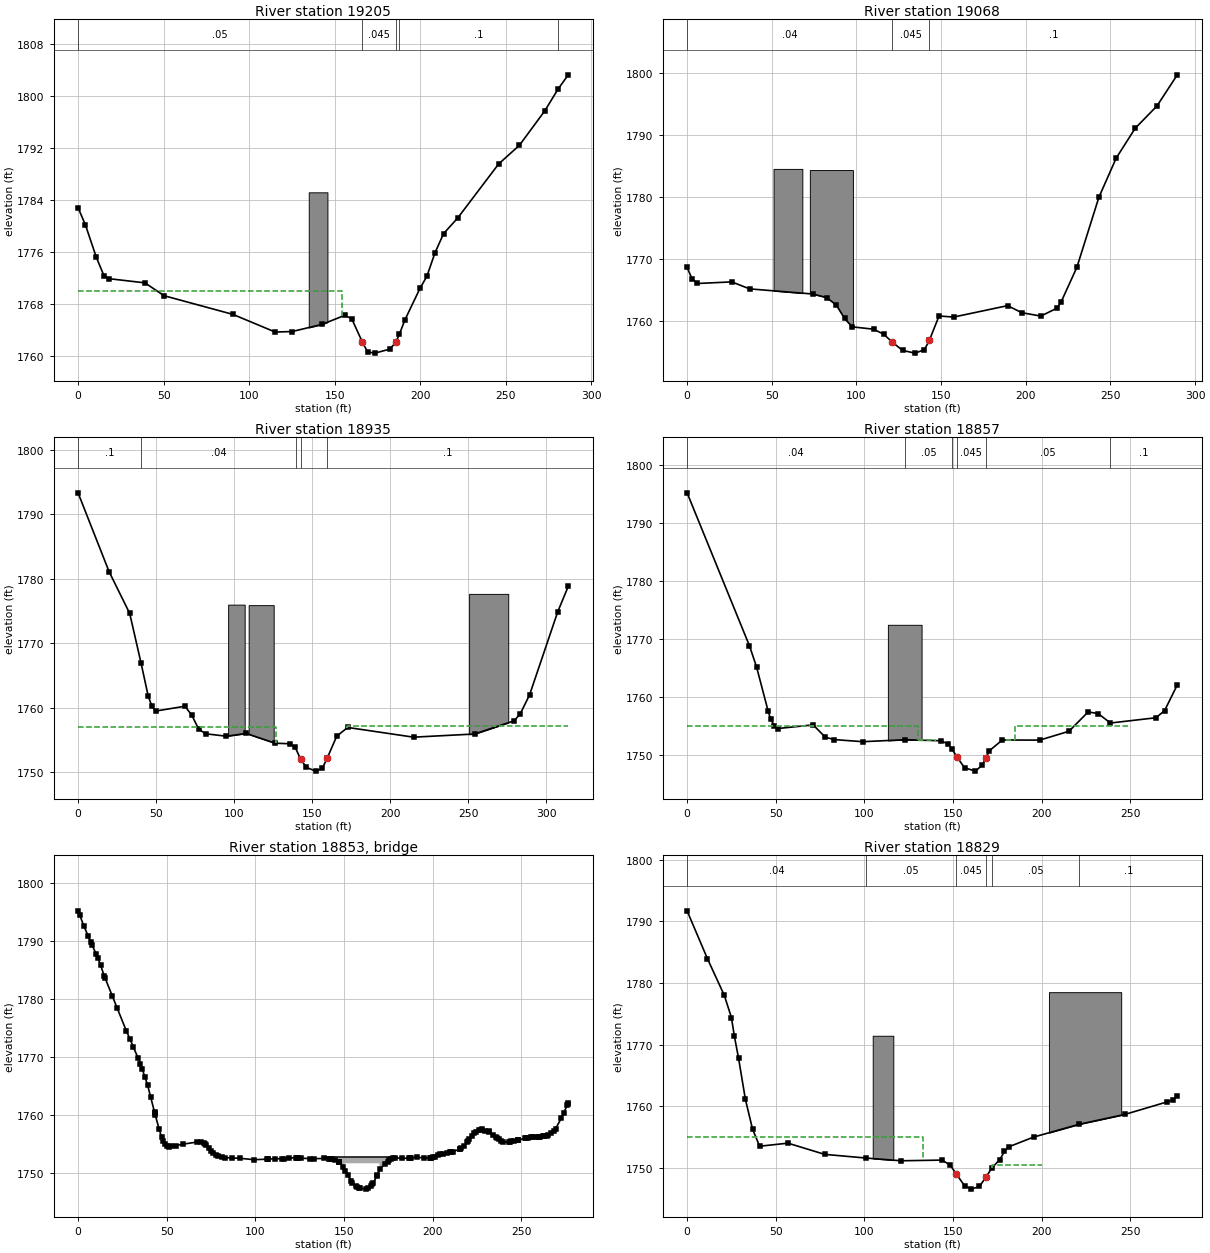
Type RM Length L Ch R = 1 ,19205   ,136.8,137.2,136.6
XS GIS Cut Line= 2
     1983836.856       248383.74     1983645.884      248169.981
#Sta/Elev= 30
       0  1782.8     4.3 1780.15    10.7 1775.14    15.1 1772.35    18.2 1771.86
    39.1 1771.22    50.3 1769.24    90.6 1766.36   115.2 1763.65   125.1 1763.72
   142.7 1764.83   155.9 1766.22     160 1765.69   166.11762.167   169.3 1760.57
   173.5  1760.4   182.3 1761.02   185.71762.048   187.8 1763.27   191.1 1765.52
   199.9 1770.37   203.9 1772.21   208.7 1775.87   213.7  1778.8   221.9 1781.19
   245.9 1789.53     258 1792.39   272.8 1797.68   280.8 1801.12   286.6 1803.25
#Mann= 5 ,-1 , 0
       0     .05       0   166.1    .045       0   185.7      .1       0
   187.8      .1       0   280.8     .05       0
#XS Ineff= 2 , 0
          154.48    1770
Permanent Ineff=
       F       F
#Block Obstruct= 1 ,-1
  134.87   145.8 1785.16
Bank Sta=166.1,185.7
XS Rating Curve= 0 ,0
Exp/Cntr=0.3,0.1

Type RM Length L Ch R = 1 ,19068   ,132.8,132.8,132.4
XS GIS Cut Line= 2
     1983924.747      248289.339     1983738.115      248067.985
#Sta/Elev= 30
       0 1768.63     2.9 1766.82     6.1 1766.04    26.4  1766.3    36.9 1765.17
    74.2 1764.34    82.4 1763.77    88.1 1762.56      93 1760.39    97.5 1759.03
   110.1 1758.65   116.1 1757.84   121.21756.552   127.3 1755.21   134.7 1754.78
   140.2 1755.35   143.11756.874   148.8 1760.79   157.4 1760.61   189.3 1762.46
   197.6 1761.32   208.9 1760.77   218.5 1762.06   220.9 1763.07   230.2 1768.66
   243.2 1779.99   253.4 1786.31   264.6 1791.13   277.5 1794.75   289.5 1799.78
#Mann= 3 ,-1 , 0
       0     .04       0   121.2    .045       0   143.1      .1       0
#Block Obstruct= 2 ,-1
   51.05   68.06 1784.57   72.49   97.92 1784.38
Bank Sta=121.2,143.1
XS Rating Curve= 0 ,0
Exp/Cntr=0.3,0.1

Type RM Length L Ch R = 1 ,18935   ,76.8,78.1,80.1
XS GIS Cut Line= 2
     1984048.445       248223.15     1983837.941       247989.86
#Sta/Elev= 30
       0 1793.36    19.9 1781.12    33.1 1774.65    40.4 1766.92      45 1761.77
    47.4 1760.21    49.7 1759.49    68.5 1760.24    72.9 1758.85    77.3 1756.69
    81.7 1755.97      95 1755.59   107.8 1756.02   126.3  1754.5   135.6 1754.42
   139.2 1753.86   142.6 1752.04   146.4 1750.74   152.4 1750.17   156.5 1750.58
   159.8 1752.25   165.8 1755.59   172.8 1756.95     215 1755.44   254.1 1755.93
   279.6 1757.99   283.5 1759.11   289.4 1762.01   307.5 1774.94   314.2 1778.85
#Mann= 5 ,-1 , 0
       0      .1       0    40.4     .04       0   139.8     .04       0
   142.6    .045       0   159.8      .1       0
#XS Ineff= 2 , 0
          126.79 1756.97  172.54         1757.22
Permanent Ineff=
       F       F
#Block Obstruct= 3 ,-1
   96.19   106.8 1776.01  109.34  125.39 1775.93  250.64  275.72 1777.68
Bank Sta=142.6,159.8
XS Rating Curve= 0 ,0
Exp/Cntr=0.5,0.3

Type RM Length L Ch R = 1 ,18857   ,26.9,28,27
XS GIS Cut Line= 4
     1984099.857       248194.65     1984019.128      248078.331
     1984004.371      248055.761     1983940.135      247968.956
#Sta/Elev= 30
       0  1795.2    35.2 1768.79    39.2 1765.14    45.7 1757.55    47.2 1756.09
    49.3 1755.01    51.1 1754.53    71.1 1755.16      78 1753.02    83.1 1752.62
    99.1 1752.26     123  1752.6     143 1752.42   147.1 1751.89   149.4 1751.01
   152.11749.671   156.5 1747.76   162.6 1747.18   166.5 1748.22   168.6  1749.5
   170.5  1750.7   177.8 1752.55   198.9 1752.53   215.4 1754.06   226.2 1757.39
   231.8 1757.12   238.8 1755.48   264.4 1756.39   269.3  1757.6   276.5 1762.07
#Mann= 6 ,-1 , 0
       0     .04       0     123     .05       0   149.4     .05       0
   152.1    .045       0   168.6     .05       0   238.8      .1       0
#XS Ineff= 4 ,-1
       0     130    1755     130     140 1752.47     180     185 1752.57
     185     250    1755
Permanent Ineff=
       F       F       F       F
#Block Obstruct= 1 ,-1
  113.25  132.26 1772.43
Bank Sta=152.1,168.6
XS Rating Curve= 0 ,0
Exp/Cntr=0.5,0.3

Type RM Length L Ch R = 3 ,18853   ,,,
BEGIN DESCRIPTION:
Unnamed Road
Survey ID: MAC200
END DESCRIPTION:
Bridge Culvert--1,0,-1,-1, 0
Deck Dist Width WeirC Skew NumUp NumDn MinLoCord MaxHiCord MaxSubmerge Is_Ogee
10,14,2.6,0, 6, 7, , , 0.98, 0, 0,0,,
     140     150     150     170     170     180
1752.6421752.6421752.6421752.6421752.6421752.642
                1751.6421751.642
     110     140     150     150     170     170     180
1752.4791752.6421752.6421752.6421752.6421752.6421752.642
                        1751.6421751.642
BR Coef=-1 , 1 , 0 ,, 0 ,,,0.8,0,1.2,0,
WSPro=,,,, 1 ,,,, 0 ,,,, 0 ,,,,-1 ,-1 ,-1 , 0 , 0 , 0 , 0 , 0
BR U #Sta/Elev= 161
       0  1795.2      .9 1794.53     3.2 1792.62     5.6 1790.94     7.2 1789.74
     7.9 1789.28    10.3 1787.71    11.2 1787.04    12.7 1785.84    14.7 1784.02
    15.2 1783.64    19.2 1780.58    22.1 1778.43    27.2 1774.51    29.2 1773.14
    31.2 1771.68    33.9 1769.78    35.2 1768.79    36.2 1767.86    37.8 1766.46
    39.2 1765.14    40.9 1763.13    43.2 1760.48    43.3  1760.3    43.5 1760.04
    45.7 1757.55    47.2 1756.09      48 1755.54    49.3 1755.01    50.4 1754.67
    51.1 1754.53    52.7 1754.58    55.1 1754.69    59.1 1754.94    67.1  1755.3
    69.2 1755.26    71.1 1755.16    71.6 1755.05    72.3 1754.84      74 1754.27
    75.1  1753.8    76.3 1753.41      78 1753.02    78.7 1752.89      81 1752.71
    83.1 1752.62    87.1 1752.55    91.1 1752.51    99.1 1752.26   106.8 1752.35
     107 1752.35   107.1 1752.35     111 1752.44     115  1752.4   116.4 1752.43
     119 1752.55     123  1752.6   123.5 1752.58   124.1 1752.57   125.8 1752.52
     131 1752.44   132.9 1752.43     139 1752.48   141.6 1752.46   142.3 1752.45
     143 1752.42   144.7 1752.26   146.9 1751.92   147.1 1751.89   147.3 1751.81
   149.4 1751.01   150.8 1750.39   152.11749.671   154.2 1748.51   154.7 1748.27
   156.5 1747.76   157.4 1747.61   158.6 1747.37   159.3  1747.3   162.6 1747.18
   163.7 1747.35   165.3  1747.8     166 1748.03   166.5 1748.22   168.6  1749.5
   168.8 1749.64   170.5  1750.7   173.1 1751.55   174.6 1751.93   175.4 1752.15
   176.6 1752.36   177.8 1752.55   178.6 1752.61   182.7 1752.49   186.8 1752.52
   187.2 1752.53   187.6 1752.54   190.9  1752.7     195 1752.56   198.7 1752.54
   198.9 1752.53   199.1 1752.54   200.2 1752.67   201.2 1752.78   203.1 1753.03
   204.2 1753.16   205.9 1753.28   208.3 1753.46   209.7 1753.57   210.6 1753.62
   211.3 1753.66   215.3 1754.05   215.4 1754.06   215.9  1754.2   217.7 1754.67
   219.5 1755.29     220 1755.51   220.7 1755.84   222.3 1756.43   223.5 1756.88
   224.7 1757.09   226.2 1757.39     227 1757.43   227.6 1757.48   229.4 1757.26
   231.7 1757.13   231.8 1757.12   234.1 1756.56   235.8 1756.17   236.4 1756.01
   237.3  1755.8   238.8 1755.48   239.9 1755.32   242.8 1755.33   243.5 1755.37
     244 1755.41   245.8 1755.53     248 1755.64   248.1 1755.65   248.3 1755.65
   252.1 1755.95   252.8 1755.99   253.8 1756.04   255.2 1756.09   256.2 1756.14
   257.5  1756.2   259.3 1756.25   259.9 1756.26   260.3 1756.26   262.2 1756.36
     263 1756.37   264.4 1756.39   264.8 1756.46   266.9 1756.87   268.4 1757.22
   269.3  1757.6   272.5 1759.37   273.9 1760.31   275.9 1761.67   276.3 1761.91
   276.5 1762.07
BR U #Mann= 6
       0     .04     123     .05   149.4     .05   152.1     .04   168.6     .05
   238.8      .1
BR D #Sta/Elev= 161
       0 1791.72       1 1791.11     2.1 1790.39       5 1788.43       9 1785.64
    11.5 1783.94      13 1783.01    15.2 1781.68    16.3 1781.03      17  1780.6
    18.6 1779.55      21    1778    23.3 1775.95      25 1774.41    25.7 1773.21
    26.7 1771.33      28 1769.21      29 1767.86    30.4 1765.19    32.5 1761.75
    32.8 1761.35    32.9 1761.11    35.1 1758.57    36.9 1756.32    37.5 1756.02
    38.3 1755.47    39.8 1754.26    40.9 1753.52    44.9 1753.83    48.9 1753.92
    52.9 1754.04      54 1754.04    56.9 1754.02    58.7 1753.94    61.1 1753.77
    64.9 1753.37      67 1753.11    68.9 1752.92    70.5 1752.77    72.8 1752.57
    75.2 1752.37    77.6  1752.2    82.3 1752.02    84.6 1751.98    84.9 1751.98
    89.3 1751.82      90 1751.81    91.7 1751.79    98.8 1751.62   101.1  1751.6
   104.8 1751.45   107.3 1751.36   110.6 1751.33   112.8 1751.27   113.1 1751.27
   116.8 1751.22   118.8  1751.2   120.8 1751.16   124.7 1751.13   130.3 1751.21
   131.8 1751.25   132.8 1751.28   136.8 1751.32   138.8 1751.33   140.8 1751.32
   143.6 1751.27   144.7  1751.2   145.9 1751.04   148.3 1750.51   148.6  1750.4
   150.7 1749.57   151.81749.026   152.5 1748.68   153.8 1748.03   155.4 1747.54
   156.5 1747.11   157.8 1746.95   160.2 1746.62   160.4 1746.56   164.3 1746.88
   164.9 1746.99   165.8 1747.28   167.3 1747.85   168.2 1748.33   168.61748.521
   169.6    1749   171.6 1749.82     172 1750.02   172.3 1750.14   174.3 1750.82
   174.4 1750.85   176.4 1751.36   177.1 1751.73     179 1752.67   180.5 1753.17
   181.4 1753.42   183.7 1753.69   184.5 1753.71   186.1 1753.89   188.1  1754.2
   188.4 1754.25   188.6 1754.26   190.7 1754.49   192.7 1754.65   193.1 1754.69
   193.6 1754.75   195.4    1755   197.8  1755.2   199.1 1755.28   200.1  1755.4
   200.9 1755.47   202.5 1755.65   204.6 1755.79   204.8 1755.81   204.9 1755.83
   205.8 1755.92   207.2 1756.06     209 1756.19   209.5  1756.2   210.2 1756.22
   211.9 1756.38   213.1 1756.46   214.2 1756.51   215.7 1756.57   216.5 1756.65
   221.2 1757.09   221.3  1757.1   221.5 1757.12   223.6 1757.33   225.9  1757.5
   226.7 1757.56   228.3 1757.68   229.4 1757.75   230.6  1757.8     233 1757.89
   233.5 1757.91   235.3 1757.97   237.2 1758.05   237.6 1758.06   237.7 1758.07
     240 1758.22   241.7 1758.35   242.3 1758.39   243.3 1758.44   244.7 1758.51
   245.8 1758.59     247 1758.69   254.1 1759.31   259.8 1759.77   262.1 1759.99
   265.3 1760.23   266.2 1760.32   268.2 1760.49   268.6 1760.53   270.3 1760.67
   270.5  1760.7   270.8 1760.72   274.3 1761.09   275.2 1761.37   276.3 1761.68
   276.5 1761.73
BR D #Mann= 6
       0     .04   101.1     .05   151.8     .04   168.6     .05     172     .05
   221.2      .1
BC Design=,, 0 ,, 0 ,,,,,,
BC Use User HTab Curves=0
BC User HTab FreeFlow(D)= 0

Type RM Length L Ch R = 1 ,18829   ,113.7,120,124
XS GIS Cut Line= 4
     1984119.822      248176.421     1984039.093      248060.102
     1984024.336      248037.533       1983960.1      247950.727
#Sta/Elev= 30
       0 1791.72    11.5 1783.94      21    1778      25 1774.41    26.7 1771.33
      29 1767.86    32.9 1761.11    36.9 1756.32    40.9 1753.52    56.9 1754.02
    77.6  1752.2   101.1  1751.6   120.8 1751.16   143.6 1751.27   148.3 1750.51
   151.81749.026   156.5 1747.11   160.4 1746.56   164.9 1746.99   168.61748.521
     172 1750.02   176.4 1751.36     179 1752.67   181.4 1753.42   195.4    1755
   221.2 1757.09     247 1758.69   270.8 1760.72   274.3 1761.09   276.5 1761.73
#Mann= 6 ,-1 , 0
       0     .04       0   101.1     .05       0   151.8    .045       0
   168.6     .05       0     172     .05       0   221.2      .1       0
#XS Ineff= 3 ,-1
       0     133    1755     133     148  1750.4     172     200  1750.4
Permanent Ineff=
       F       F       F
#Block Obstruct= 2 ,-1
   104.7  116.31 1771.45  204.09  244.85 1778.52
Bank Sta=151.8,168.6
XS Rating Curve= 0 ,0
Exp/Cntr=0.5,0.3

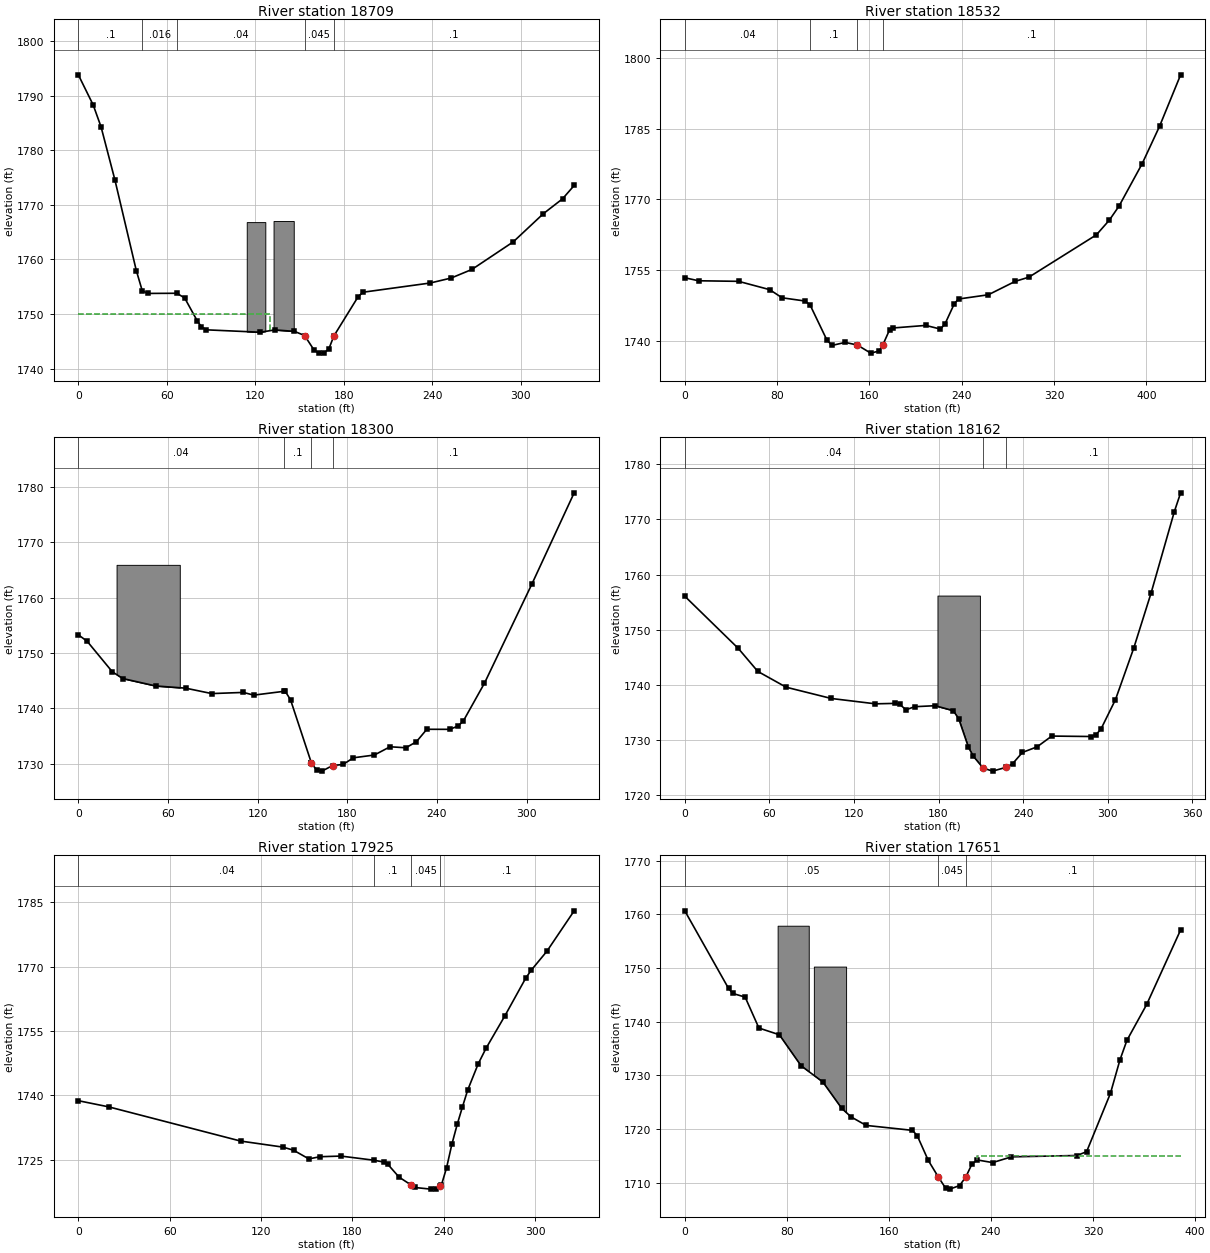
Type RM Length L Ch R = 1 ,18709   ,181.3,176.6,170.2
XS GIS Cut Line= 4
1984182.62749472248161.6608554031984156.76722173 248125.45647322
1984122.44358667247907.2898065571984080.12677633247850.397205983
#Sta/Elev= 30
       0 1793.83    10.1 1788.29    15.4  1784.3    24.8 1774.57    39.3 1757.97
    43.3  1754.3    46.9 1753.77    66.8  1753.8    72.1 1752.94    80.7 1748.71
    83.4 1747.67    86.7  1747.1   123.3 1746.66   133.2 1747.08   146.5 1746.82
   153.41746.059   159.8 1743.41   163.1 1742.83   166.4 1742.84   169.8 1743.57
   173.31745.984   189.7 1753.16     193 1753.99   238.6 1755.68   252.8 1756.59
   266.9 1758.17   294.9 1763.22   315.3 1768.38   328.3  1771.1   336.2 1773.55
#Mann= 5 ,-1 , 0
       0      .1       0    43.3    .016       0    66.8     .04       0
   153.4    .045       0   173.3      .1       0
#XS Ineff= 2 , 0
             130    1750
Permanent Ineff=
       F       F
#Block Obstruct= 2 ,-1
  114.19  126.79 1766.84  132.37  146.06 1767.04
Bank Sta=153.4,173.3
XS Rating Curve= 0 ,0
Exp/Cntr(USF)=0,0
Exp/Cntr=0.3,0.1

Type RM Length L Ch R = 1 ,18532   ,207.3,232.6,219.5
Node Name=F
XS GIS Cut Line= 3
     1984381.561      248110.302      1984278.48      247942.117
     1984152.611      247746.804
#Sta/Elev= 30
       0 1753.35    11.9 1752.71    46.6 1752.59    73.5 1750.83    84.3  1749.1
   104.3 1748.41   108.6 1747.55   122.9 1740.25   127.4 1738.98   138.9 1739.64
   149.5 1739.08   161.1 1737.36   168.3  1737.8   171.41739.005   177.4 1742.29
   180.2 1742.69   208.8 1743.24   221.5 1742.46   225.4 1743.53   233.6 1747.88
   237.2 1748.84     263 1749.74   286.4  1752.6   298.1 1753.47   356.6 1762.45
   367.8 1765.56   376.2 1768.54   396.3 1777.56   411.3 1785.46   429.6  1796.4
#Mann= 4 ,-1 , 0
       0     .04       0   108.6      .1       0   149.5    .045       0
   171.4      .1       0
#Block Obstruct= 2 , 0
           55.78 1773.35
Bank Sta=149.5,171.4
XS Rating Curve= 0 ,0
Exp/Cntr=0.3,0.1

Type RM Length L Ch R = 1 ,18300   ,136.9,137.4,137
XS GIS Cut Line= 2
1984547.07425396248055.7221447791984429.41780441 247745.48374546
#Sta/Elev= 30
       0 1753.29     5.9 1752.12    22.7 1746.62    29.7 1745.39    51.7 1744.05
    71.8 1743.65    89.3 1742.67   110.4 1742.88   117.4 1742.39   137.6 1743.08
   138.5 1743.06     142 1741.55     156 1730.11     156 1730.09   159.5 1728.85
     163 1728.66   170.21729.675   177.1 1729.86   184.1 1731.07   198.1 1731.57
   208.6 1733.06   219.2 1732.88   226.2 1733.96   233.2 1736.22   248.6 1736.21
   254.3 1736.83   257.7 1737.75   271.8 1744.56   303.6 1762.51   331.8 1778.94
#Mann= 4 ,-1 , 0
       0     .04       0   137.6      .1       0     156    .045       0
   170.2      .1       0
#Block Obstruct= 1 ,-1
   25.58   67.89 1765.93
Bank Sta=156,170.2
XS Rating Curve= 0 ,0
Exp/Cntr(USF)=0,0
Exp/Cntr=0.3,0.1

Type RM Length L Ch R = 1 ,18162   ,236.7,237.4,236.6
XS GIS Cut Line= 2
     1984685.381      248053.879     1984569.278      247721.847
#Sta/Elev= 30
       0 1756.09    37.9 1746.65    51.8 1742.47    71.9 1739.61   103.9 1737.57
   135.2  1736.6   149.1 1736.68   152.6 1736.48   156.9 1735.52     163 1736.08
   177.5 1736.26   190.4 1735.37   194.3 1733.89   201.2 1728.73   204.7 1727.09
   211.7 1724.95   218.4 1724.41     2281725.109   232.5 1725.75   239.5  1727.8
   249.9 1728.81   260.3 1730.76   288.1 1730.68   291.6 1731.01   295.1 1731.98
   305.5 1737.37   318.4 1746.66   330.7 1756.63   347.2 1771.38   351.7 1774.82
#Mann= 3 , 0 , 0
       0     .04       0   211.7    .045       0     228      .1       0
#Block Obstruct= 1 ,-1
  179.23  209.32 1756.21
Bank Sta=211.7,228
XS Rating Curve= 0 ,0
Exp/Cntr=0.3,0.1

Type RM Length L Ch R = 1 ,17925   ,274.3,274,270.7
XS GIS Cut Line= 2
     1984904.565      247974.669     1984799.313      247666.509
#Sta/Elev= 30
       0 1738.72      20 1737.28   106.6  1729.3   134.4 1727.89   141.3 1727.17
   151.4 1725.14   158.6 1725.65   172.5  1725.8   194.4 1724.82   200.5 1724.41
   203.1 1723.93   210.6  1720.9   218.21719.127     221 1718.47   231.4 1718.09
   234.9 1718.23   237.71718.837   238.4 1719.01   241.8 1723.05   245.3 1728.57
   248.8 1733.19   252.2 1737.23   255.7 1741.22   262.6 1747.33   267.7 1750.93
     280 1758.45   293.8 1767.32   297.3 1769.12   307.7 1773.59   325.6 1783.02
#Mann= 4 ,-1 , 0
       0     .04       0   194.4      .1       0   218.2    .045       0
   237.7      .1       0
Bank Sta=218.2,237.7
XS Rating Curve= 0 ,0
Exp/Cntr=0.3,0.1

Type RM Length L Ch R = 1 ,17651   ,193.6,192.1,190.9
XS GIS Cut Line= 2
     1985187.768      247891.118     1985008.731      247546.066
#Sta/Elev= 30
       0 1760.64    34.3 1746.19    37.6 1745.26    47.3 1744.58    58.1 1738.82
    74.1 1737.57    91.1 1731.81   108.2 1728.78     123 1723.87   130.4 1722.27
   142.2 1720.69   178.5 1719.77   182.2 1718.79   190.9 1714.16   198.8 1711.07
   204.4 1709.03   207.7 1708.83   215.4 1709.49   220.31711.093     225 1713.44
   229.1 1714.27   241.3 1713.77   256.1 1714.84   307.4 1715.09     315  1715.8
   333.7 1726.68   341.1 1732.86   346.6 1736.53   362.1 1743.21   388.7 1757.09
#Mann= 3 ,-1 , 0
       0     .05       0   198.8    .045       0   220.3      .1       0
#XS Ineff= 2 , 0
                          228.96         1714.95
Permanent Ineff=
       F       F
#Block Obstruct= 2 ,-1
   72.77   97.17 1757.87  101.17  126.45 1750.26
Bank Sta=198.8,220.3
XS Rating Curve= 0 ,0
Exp/Cntr=0.3,0.1

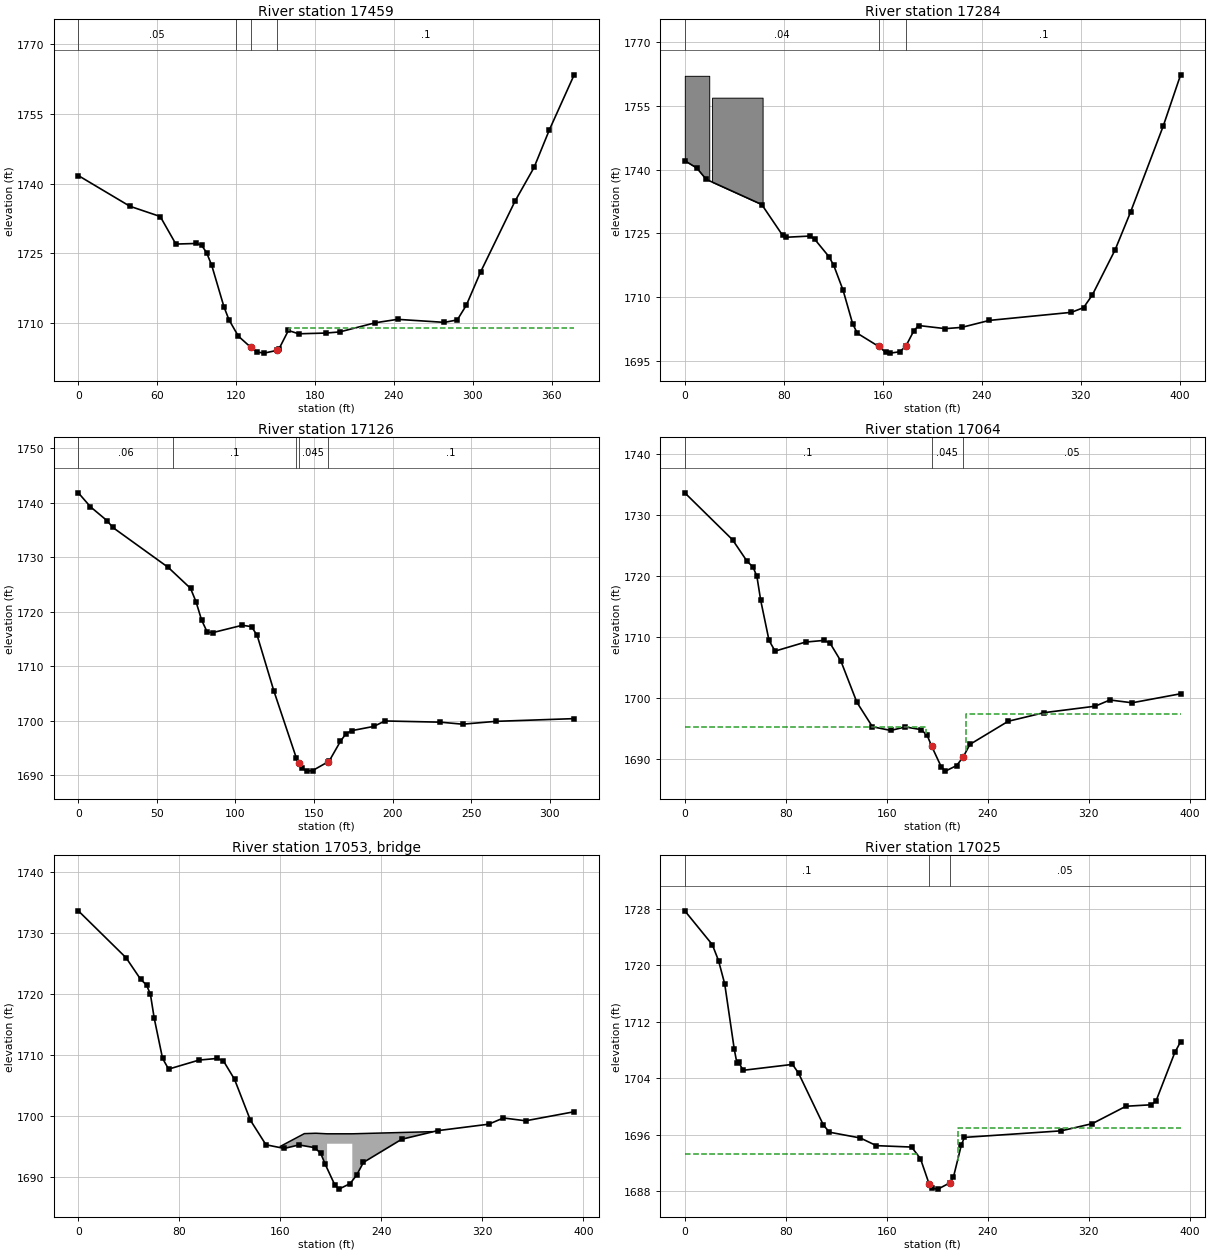
Type RM Length L Ch R = 1 ,17459   ,176.7,174.6,174.8
XS GIS Cut Line= 2
     1985319.061      247706.657     1985116.153      247388.731
#Sta/Elev= 30
       0 1741.71    39.2 1735.11    62.3  1732.9    74.2 1726.97    89.8  1727.1
    93.7 1726.75    97.6 1725.11   101.5 1722.37   110.8 1713.45   114.6 1710.68
   121.7 1707.16   131.2 1704.75     136 1703.74   141.3  1703.5   150.91704.081
   152.6 1704.38   159.8 1708.38   167.6 1707.66   188.3 1707.82   198.8 1708.06
     226 1710.04   242.9 1710.77   278.5 1710.12   288.3 1710.65   295.2 1713.83
     306 1720.95   332.3 1736.25   346.7 1743.46   358.3 1751.52   377.2 1763.39
#Mann= 4 ,-1 , 0
       0     .05       0     120      .1       0   131.2    .045       0
   150.9      .1       0
#XS Ineff= 2 , 0
                          160.45         1708.97
Permanent Ineff=
       F       F
Bank Sta=131.2,150.9
XS Rating Curve= 0 ,0
Exp/Cntr=0.3,0.1

Type RM Length L Ch R = 1 ,17284   ,146.1,157.8,156.8
XS GIS Cut Line= 3
     1985480.736      247649.148     1985375.485      247472.282
     1985271.318      247307.351
#Sta/Elev= 30
       0 1742.12     9.6 1740.42    17.3 1737.73    62.2  1731.8      79 1724.57
    82.2 1724.09   101.3 1724.37   105.1 1723.59   116.6  1719.5   120.4 1717.49
     128 1711.59   135.7 1703.73   139.5 1701.47   156.81698.358   162.4 1696.98
   166.2 1696.79   173.9 1697.12   178.81698.473   185.3 1702.11   189.1 1703.29
   210.6 1702.56   223.8 1702.85   246.3  1704.5   312.6  1706.4   322.4  1707.5
   329.5 1710.48   347.9  1721.1   360.4 1730.01   386.8 1750.25   400.9 1762.35
#Mann= 3 ,-1 , 0
       0     .04       0   156.8    .045       0   178.8      .1       0
#Block Obstruct= 2 ,-1
       0   19.76 1762.12   22.05    62.9 1756.97
Bank Sta=156.8,178.8
XS Rating Curve= 0 ,0
Exp/Cntr=0.3,0.1

Type RM Length L Ch R = 1 ,17126   ,67,61.8,52.3
XS GIS Cut Line= 3
     1985596.839      247657.829      1985530.65      247492.898
     1985479.651       247364.86
#Sta/Elev= 30
       0 1741.84     7.7 1739.28    18.3 1736.72    21.9 1735.49    57.2 1728.15
    71.4  1724.3    74.9 1721.83    78.4 1718.51      82 1716.27    85.5 1716.17
   104.3 1717.52   110.2 1717.27   113.8 1715.65   124.4 1705.48   138.8 1693.08
   140.21692.298   142.1 1691.31   145.6 1690.74   149.1 1690.85   158.81692.426
   159.7 1692.63   166.8 1696.22   170.3 1697.61   173.9 1698.17     188 1698.95
   195.1 1699.95   230.4 1699.73   244.5 1699.36   265.7 1699.88   315.5 1700.38
#Mann= 5 ,-1 , 0
       0     .06       0      60      .1       0   138.8      .1       0
   140.2    .045       0   158.8      .1       0
Bank Sta=140.2,158.8
XS Rating Curve= 0 ,0
Exp/Cntr=0.5,0.3

Type RM Length L Ch R = 1 ,17064   ,37.9,39.4,43.5
XS GIS Cut Line= 5
1985752.96001293247653.4155668111985630.56401293247539.699566811
1985591.50201293247503.2415668111985547.23101293247449.422566811
1985498.62001293247359.144566811
#Sta/Elev= 30
       0  1733.6    37.8 1725.91    49.4 1722.36      54 1721.45    57.1 1719.91
    60.1    1716    66.7 1709.42    71.5 1707.66    95.6 1709.14   110.1 1709.41
   114.9 1709.01   123.7 1705.99   136.3 1699.27   148.6 1695.26   163.1 1694.66
   174.7 1695.23   187.2 1694.79     192 1693.84   195.41692.123  203.11 1688.69
   206.4 1687.99  215.28  1688.9   220.51690.315   225.8 1692.37   256.1 1696.16
   284.5 1697.57     325 1698.63   336.7 1699.65   354.3 1699.19   392.7 1700.67
#Mann= 3 ,-1 , 0
       0      .1       0   195.4    .045       0   220.5     .05       0
#XS Ineff= 2 , 0
             191 1695.22     223         1697.41
Permanent Ineff=
       F       F
Bank Sta=195.4,220.5
XS Rating Curve= 0 ,0
Exp/Cntr=0.5,0.3

Type RM Length L Ch R = 3 ,17053   ,,,
BEGIN DESCRIPTION:
Unnamed Road
Survey ID: MAC200
END DESCRIPTION:
Bridge Culvert--1,0,-1,-1, 0
Deck Dist Width WeirC Skew NumUp NumDn MinLoCord MaxHiCord MaxSubmerge Is_Ogee
8,12,2.6,0, 10, 10, , , 0.98, 0, 0,0,,
     160     179     188     197     197     203     209     217     217     280
    16951697.0871697.1491697.0581697.0581697.0581697.0581697.0581697.0581697.406
                                1695.4311695.4311695.4311695.431
     160     179     191     191     208     211     211     214     221     280
    16951697.0871697.0581697.0581697.0581697.0581697.0581697.0581697.4061697.406
                        1695.4311695.4311695.431
BR Coef=-1 , 1 , 0 ,, 0 ,,,0.8,0,1.2,0,
WSPro=,,,, 1 ,,,, 0 ,,,, 0 ,,,,-1 ,-1 ,-1 , 0 , 0 , 0 , 0 , 0
BR U #Sta/Elev= 30
       0  1733.6    37.8 1725.91    49.4 1722.36      54 1721.45    57.1 1719.91
    60.1    1716    66.7 1709.42    71.5 1707.66    95.6 1709.14   110.1 1709.41
   114.9 1709.01   123.7 1705.99   136.3 1699.27   148.6 1695.26   163.1 1694.66
   174.7 1695.23   187.2 1694.79     192 1693.84   195.41692.123  203.11 1688.69
   206.4 1687.99  215.28  1688.9   220.51690.315   225.8 1692.37   256.1 1696.16
   284.5 1697.57     325 1698.63   336.7 1699.65   354.3 1699.19   392.7 1700.67
BR U #Mann= 3
       0      .1   195.4     .04   220.5     .05
BR D #Sta/Elev= 30
       0 1727.75    21.8 1722.95    26.7 1720.69    31.6 1717.39    39.2 1708.09
    41.3 1706.12    42.6 1706.28    46.2 1705.12    85.3 1705.96    90.1 1704.71
   109.7 1697.38   114.5 1696.34     139 1695.52   151.7 1694.43   179.6 1694.23
   186.6  1692.6   193.6 1688.95   195.5 1688.37   200.5 1688.26   209.8 1689.14
   212.8 1689.99   219.1 1694.58   221.5  1695.6   298.1 1696.53   322.7 1697.55
   349.4 1700.02   369.5 1700.23   373.2 1700.76   388.1 1707.65   392.7 1709.18
BR D #Mann= 3
       0      .1   193.6     .04   209.8     .05
BC Design=,, 0 ,, 0 ,,,,,,
BC Use User HTab Curves=0
BC User HTab FreeFlow(D)= 0

Type RM Length L Ch R = 1 ,17025   ,107.9,111.8,118.6
XS GIS Cut Line= 6
1985787.16677283247642.3611765161985664.10744513247530.636159631
1985653.59749826247521.0677426731985627.86458787247491.026353032
1985581.43777283247438.3681765161985532.82677283247348.090176516
#Sta/Elev= 30
       0 1727.75    21.8 1722.95    26.7 1720.69    31.6 1717.39    39.2 1708.09
    41.3 1706.12    42.6 1706.28    46.2 1705.12    85.3 1705.96    90.1 1704.71
   109.7 1697.38   114.5 1696.34     139 1695.52   151.7 1694.43   179.6 1694.23
   186.6  1692.6   193.6 1688.95   195.5 1688.37   200.5 1688.26   209.8 1689.14
   212.8 1689.99   219.1 1694.58   221.5  1695.6   298.1 1696.53   322.7 1697.55
   349.4 1700.02   369.5 1700.23   373.2 1700.76   388.1 1707.65   392.7 1709.18
#Mann= 3 , 0 , 0
       0      .1       0   193.6    .045       0   209.8     .05       0
#XS Ineff= 2 , 0
             185 1693.25     216            1697
Permanent Ineff=
       F       F
Bank Sta=193.6,209.8
XS Rating Curve= 0 ,0
Exp/Cntr=0.5,0.3