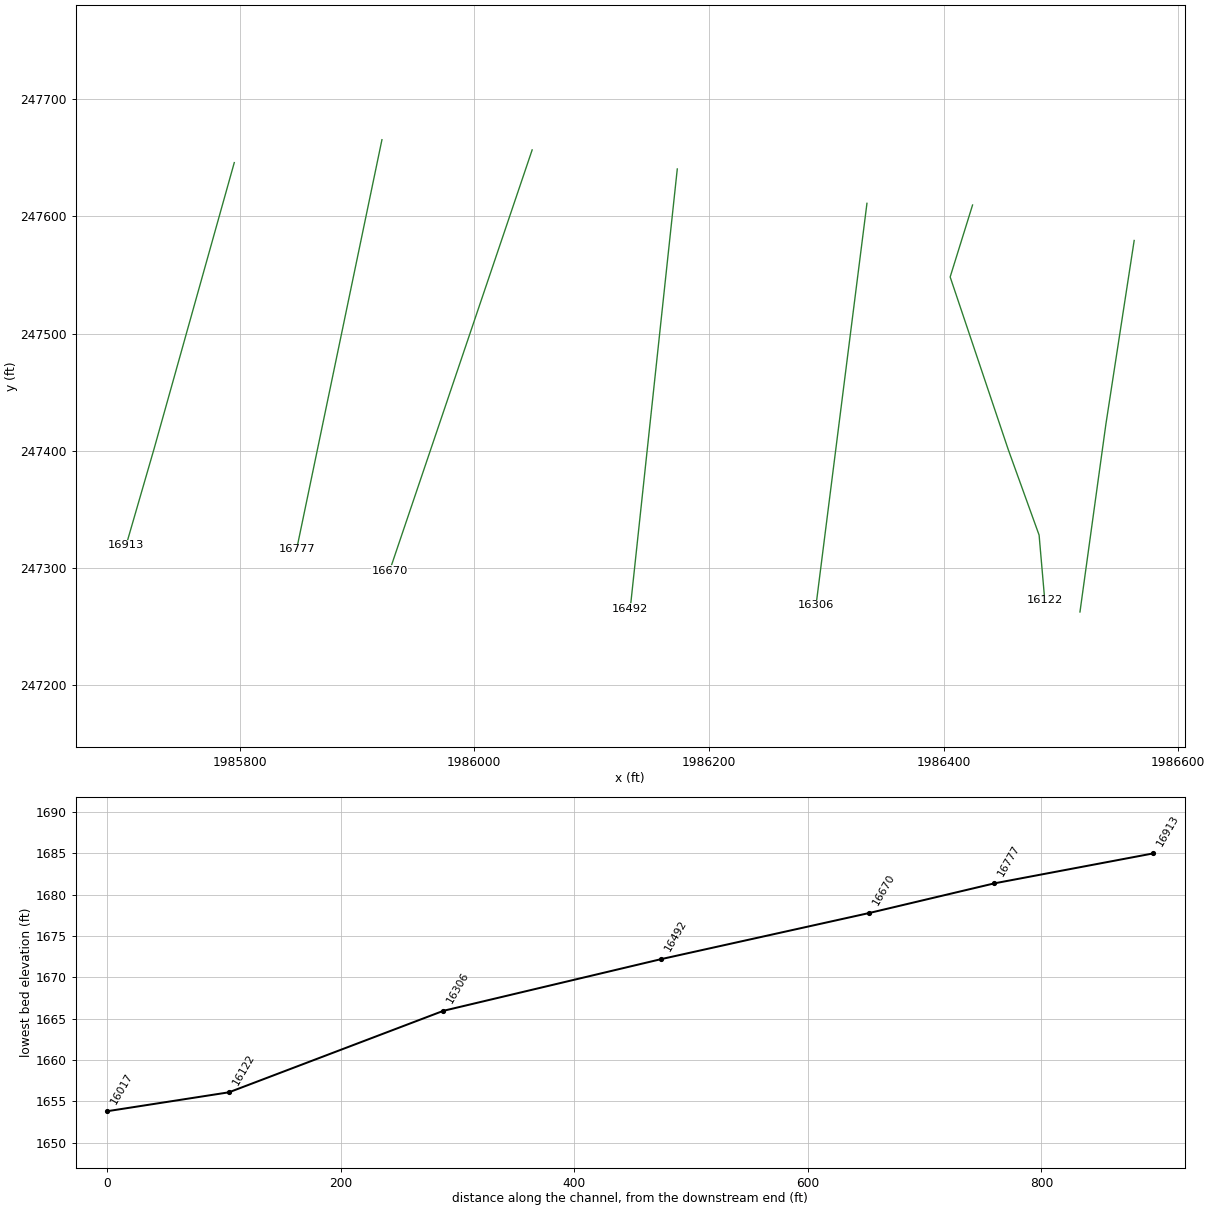
HEC-RAS study MADAMCK.prj: MADAMCK

--- MADAMCK.g01 (geometry) --- (continued)

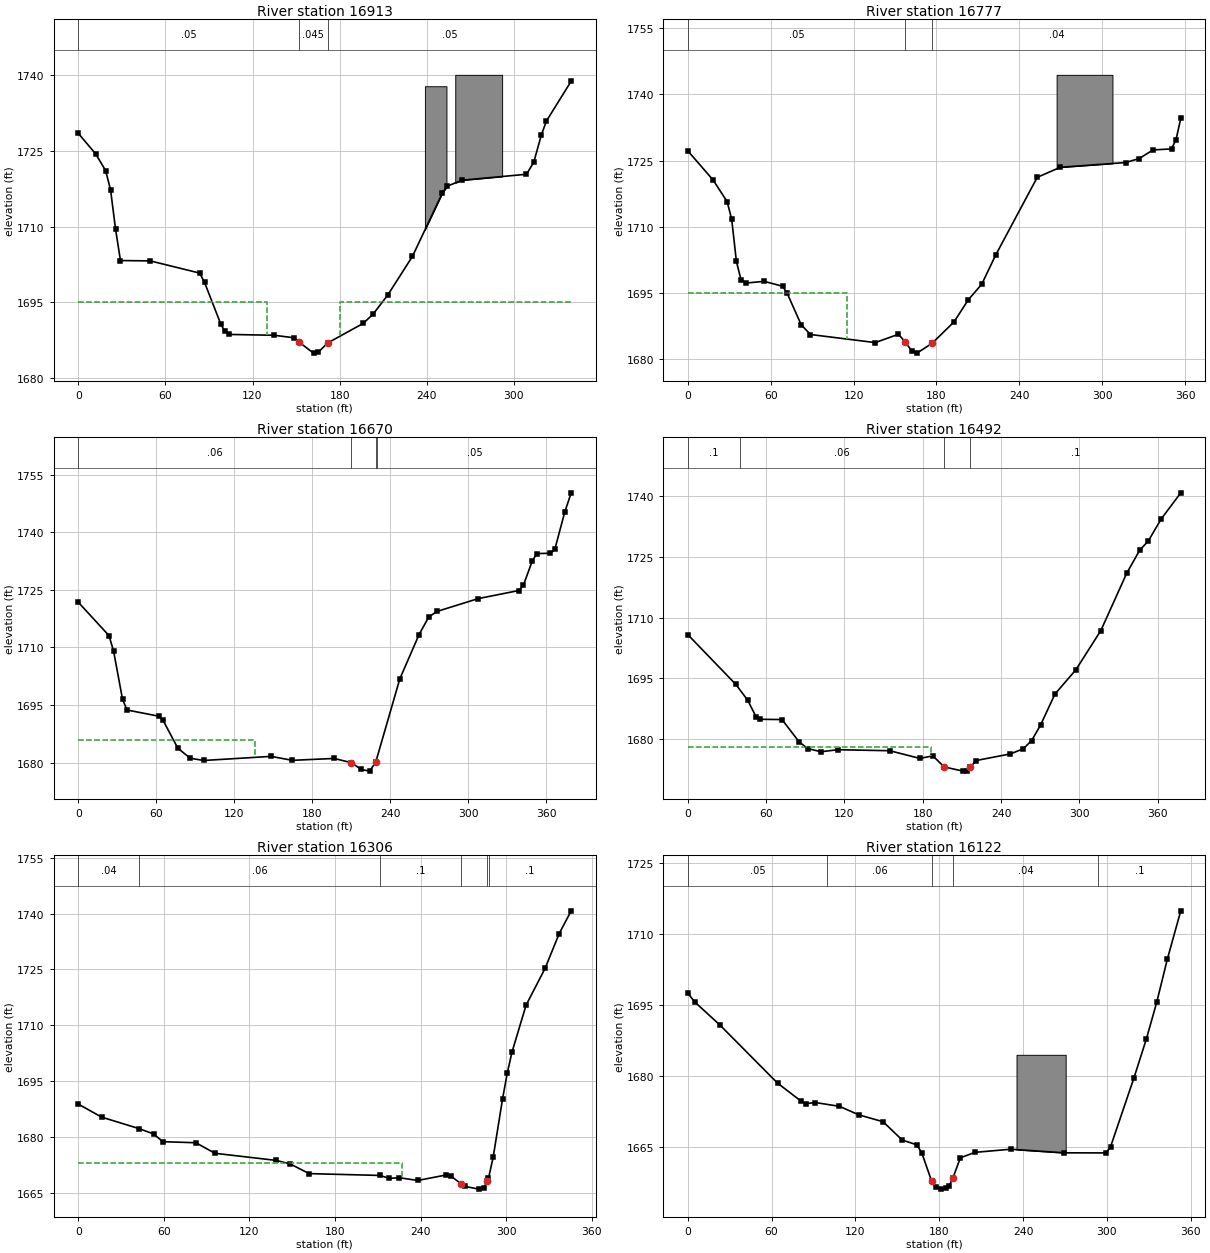
Type RM Length L Ch R = 1 ,16913   ,133.7,136,137.4
XS GIS Cut Line= 3
     1985795.407      247645.893     1985727.047      247401.752
     1985703.176      247319.287
#Sta/Elev= 30
       0 1728.53    12.1 1724.41    18.9 1721.12    22.3 1717.29    25.7 1709.57
    29.1 1703.31    49.6 1703.24    83.6 1700.83      87 1698.97    98.2 1690.69
   100.9 1689.32   104.1 1688.67   134.7 1688.51   148.4 1688.02   151.71687.233
     162 1684.97   165.4 1685.18   171.71686.977   196.1 1690.84   202.9 1692.65
   213.1 1696.47   230.1 1704.13   250.6 1716.62     254 1718.03   264.2 1719.22
   308.6  1720.4   313.6 1722.75   318.8 1728.13   322.3 1730.93   339.4 1738.84
#Mann= 3 ,-1 , 0
       0     .05       0   151.7    .045       0   171.7     .05       0
#XS Ineff= 2 , 0
             130    1695     180            1695
Permanent Ineff=
       F       F
#Block Obstruct= 2 ,-1
  238.69  253.53 1737.84  259.58  291.86  1740.1
Bank Sta=151.7,171.7
XS Rating Curve= 0 ,0
Exp/Cntr=0.3,0.1

Type RM Length L Ch R = 1 ,16777   ,107.5,107,105.2
XS GIS Cut Line= 2
     1985921.274      247665.424     1985848.575      247316.032
#Sta/Elev= 30
       0 1727.21    18.4 1720.56    28.5 1715.69    31.8 1711.69    35.2 1702.16
    38.5 1698.03    41.9 1697.22    55.3 1697.62    68.7  1696.5      72 1694.89
    82.1 1687.79    88.8 1685.57   135.7 1683.74   152.5 1685.62   157.21683.962
   162.5 1681.72   165.9 1681.35   176.81683.557   192.7 1688.41   203.1 1693.44
   212.8 1696.96   222.8 1703.51     253 1721.19   269.7 1723.47   316.9 1724.54
   326.7 1725.43   336.8  1727.4   350.2 1727.63   353.5 1729.76   356.9 1734.53
#Mann= 3 , 0 , 0
       0     .05       0   157.2    .045       0   176.8     .04       0
#XS Ineff= 2 , 0
             115    1695
Permanent Ineff=
       F       F
#Block Obstruct= 1 ,-1
  267.02  307.45 1744.42
Bank Sta=157.2,176.8
XS Rating Curve= 0 ,0
Exp/Cntr=0.3,0.1

Type RM Length L Ch R = 1 ,16670   ,168.3,178.3,178.3
XS GIS Cut Line= 2
     1986049.313      247656.744     1985927.785      247297.586
#Sta/Elev= 30
       0 1721.77    23.7 1713.05    27.2 1709.06    34.1 1696.48    37.6 1693.68
    61.8 1692.09    65.3 1690.98    76.6 1683.77    86.1 1681.13    96.5 1680.54
   148.4 1681.61   164.6 1680.58   196.9 1681.07   210.21679.957   217.7  1678.2
   224.1 1677.77   228.81680.047   247.4 1701.81   262.2 1713.34   269.6 1717.89
   275.9 1719.34   307.7 1722.69   338.9 1724.79   342.4 1726.14   349.3 1732.52
   352.8 1734.41   363.2  1734.5   366.6 1735.53   374.2 1745.17   379.2 1750.23
#Mann= 4 ,-1 , 0
       0     .06       0   210.2    .045       0   228.8     .05       0
   230.2     .05       0
#XS Ineff= 2 , 0
          136.11 1685.83
Permanent Ineff=
       F       F
Bank Sta=210.2,228.8
XS Rating Curve= 0 ,0
Exp/Cntr=0.3,0.1

Type RM Length L Ch R = 1 ,16492   ,181.4,186.5,178.9
XS GIS Cut Line= 2
     1986173.011      247640.467     1986132.863      247265.033
#Sta/Elev= 30
       0  1705.8    36.8 1693.54    45.8 1689.69    52.4 1685.52    55.7 1684.95
    72.2 1684.88    85.4 1679.34      92 1677.74   101.9 1676.96   115.1 1677.46
   154.7 1677.21   177.8 1675.32   187.7 1675.95   196.41673.227   210.8 1672.19
   214.1 1672.31   216.41673.098   220.7 1674.79   247.1 1676.43     257 1677.69
   263.4 1679.72   270.2 1683.52   281.2 1691.14   297.2 1697.11   316.4  1706.8
   336.2  1720.9   346.1 1726.55   352.7 1728.82   362.6 1734.25   377.6 1740.69
#Mann= 4 ,-1 , 0
       0      .1       0      40     .06       0   196.4    .045       0
   216.4      .1       0
#XS Ineff= 2 , 0
          186.59 1678.14
Permanent Ineff=
       F       F
Bank Sta=196.4,216.4
XS Rating Curve= 0 ,0
Exp/Cntr=0.3,0.1

Type RM Length L Ch R = 1 ,16306   ,162.1,183.6,189.1
XS GIS Cut Line= 2
     1986334.686      247611.171     1986291.283      247268.289
#Sta/Elev= 30
       0 1688.82    16.4  1685.3    42.9 1682.18    52.8 1680.78    59.4 1678.69
    82.5 1678.41    95.8 1675.58   138.8 1673.66   148.7  1672.7   161.9 1670.11
   211.5 1669.62   218.1 1668.83   225.2    1669     238 1668.27   257.8 1669.73
   261.1 1669.51   268.11667.453     271 1666.68   280.9 1665.94   284.3 1666.33
   286.9 1668.19   287.6 1668.82   290.9  1674.5   297.5 1690.24   300.8 1697.17
   304.1 1702.79     314 1715.42   327.3 1725.29   337.2 1734.66   345.6 1740.76
#Mann= 6 ,-1 , 0
       0     .04       0    42.9     .06       0   211.5      .1       0
   268.1    .045       0   286.9      .1       0   288.1      .1       0
#XS Ineff= 2 , 0
          226.76    1673
Permanent Ineff=
       F       F
#Block Obstruct= 2 , 0
           17.49 1708.82
Bank Sta=268.1,286.9
XS Rating Curve= 0 ,0
Exp/Cntr=0.3,0.1

Type RM Length L Ch R = 1 ,16122   ,108.5,104.4,97.3
XS GIS Cut Line= 5
1986424.69700737247609.7100020481986405.60425345  247548.3376225
1986455.13699877247401.0220010241986481.41427495247328.127560021
 1986486.2330002247272.612002458
#Sta/Elev= 30
       0 1697.53     5.2 1695.63    22.8 1690.87    64.3 1678.51    80.9 1674.75
    84.4 1674.17    91.3 1674.41   108.6 1673.61   122.4 1671.81   139.8 1670.35
   153.5 1666.48     164 1665.46   167.5 1663.78   174.6 1657.75   177.8 1656.57
   181.3 1656.09   184.8 1656.24   187.2 1656.84   189.8 1658.44   195.1  1662.7
   205.5 1663.87   231.1 1664.53   269.6 1663.77   299.5 1663.75   302.7  1665.1
   319.4 1679.63   328.2 1687.79   335.7 1695.63   343.3 1704.76   352.9 1714.97
#Mann= 5 ,-1 , 0
       0     .05       0     100     .06       0   174.6    .045       0
   189.8     .04       0   293.5      .1       0
#Block Obstruct= 1 ,-1
  235.32  270.52 1684.51
Bank Sta=174.6,189.8
XS Rating Curve= 0 ,0
Exp/Cntr=0.5,0.3

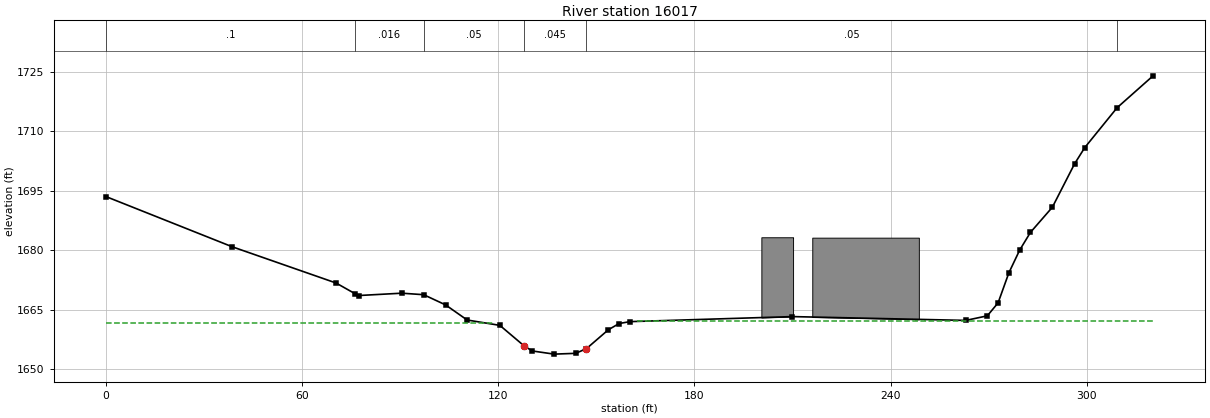
Type RM Length L Ch R = 1 ,16017   ,37.5,38,38.1
XS GIS Cut Line= 3
 1986562.4600206247579.451085156 1986538.3160289247422.541280357
1986516.24360498247262.513539502
#Sta/Elev= 30
       0 1693.52    38.7 1680.84    70.4 1671.73    76.1 1669.08    77.3 1668.57
    90.5 1669.16    97.2 1668.78   103.9 1666.21   110.5  1662.4   120.5 1661.05
   127.9 1655.89   130.4  1654.6   137.1  1653.8   143.7    1654     147 1655.19
   153.7 1659.95     157 1661.52   160.3 1661.99     210 1663.26     263  1662.3
   269.6 1663.45   272.9 1666.73   276.2  1674.3   279.5 1680.02   282.8 1684.49
   289.5 1690.83   296.3 1701.78   299.4 1705.85   309.3 1715.91   320.3 1723.95
#Mann= 6 ,-1 , 0
       0      .1       0    76.1    .016       0    97.2     .05       0
   127.9    .045       0     147     .05       0   309.3      .1       0
#XS Ineff= 2 , 0
           118.5 1661.59   162.5         1662.26
Permanent Ineff=
       F       F
#Block Obstruct= 2 ,-1
  200.49  210.19 1683.26  216.06  248.66 1683.16
Bank Sta=127.9,147
XS Rating Curve= 0 ,0
Exp/Cntr=0.5,0.3