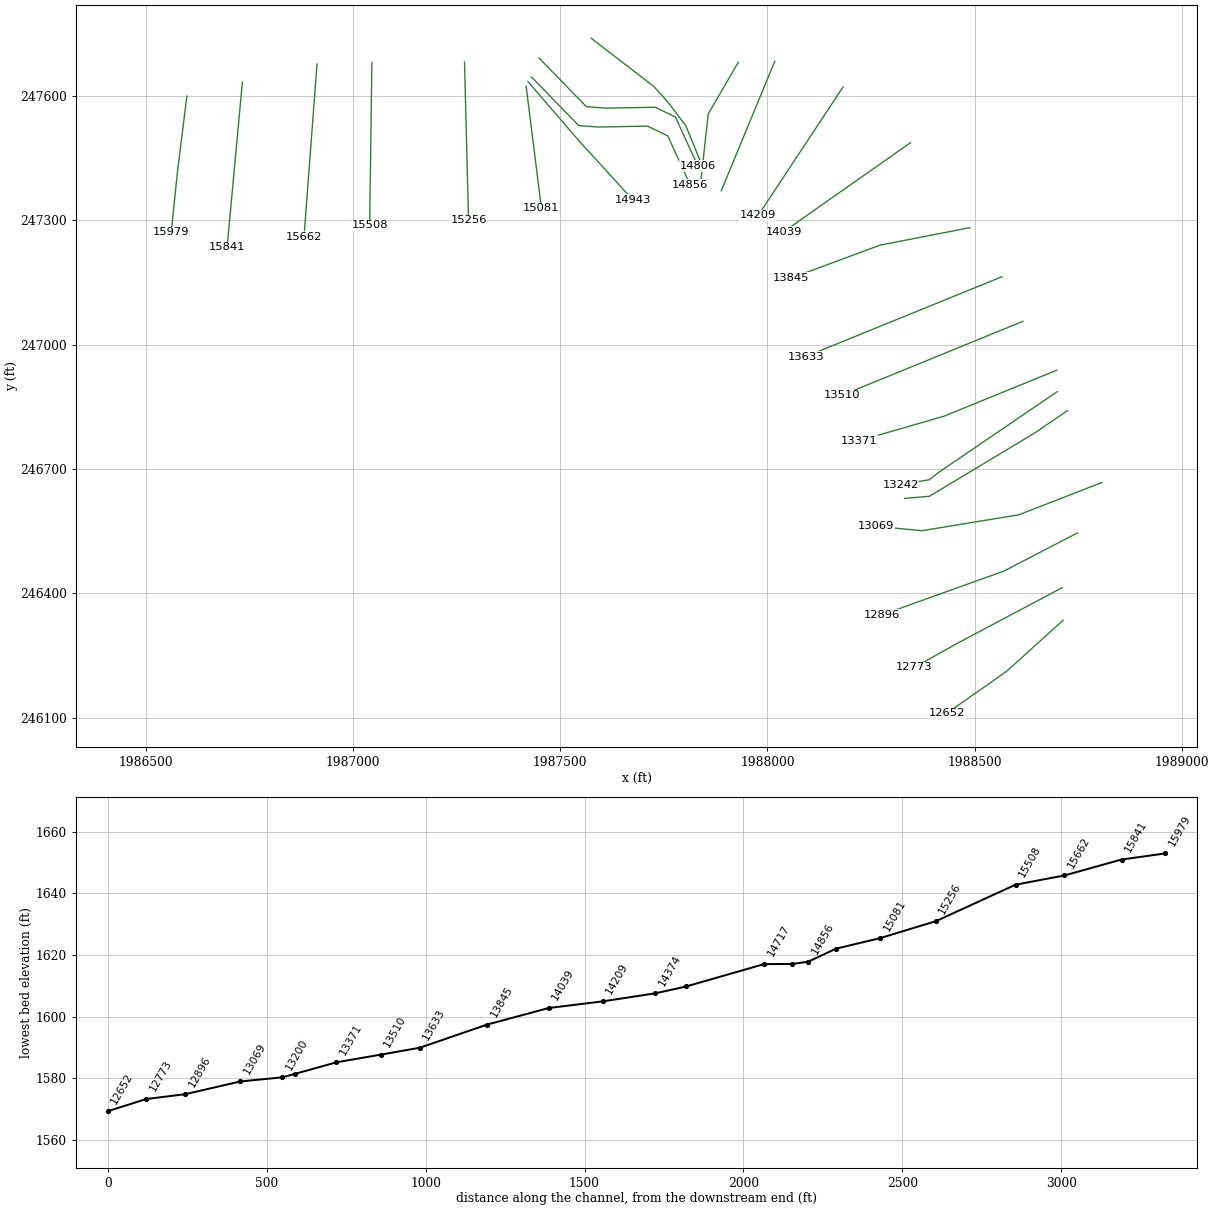
HEC-RAS study MADAMCK.prj: MADAMCK

--- MADAMCK.g01 (geometry) --- (continued)

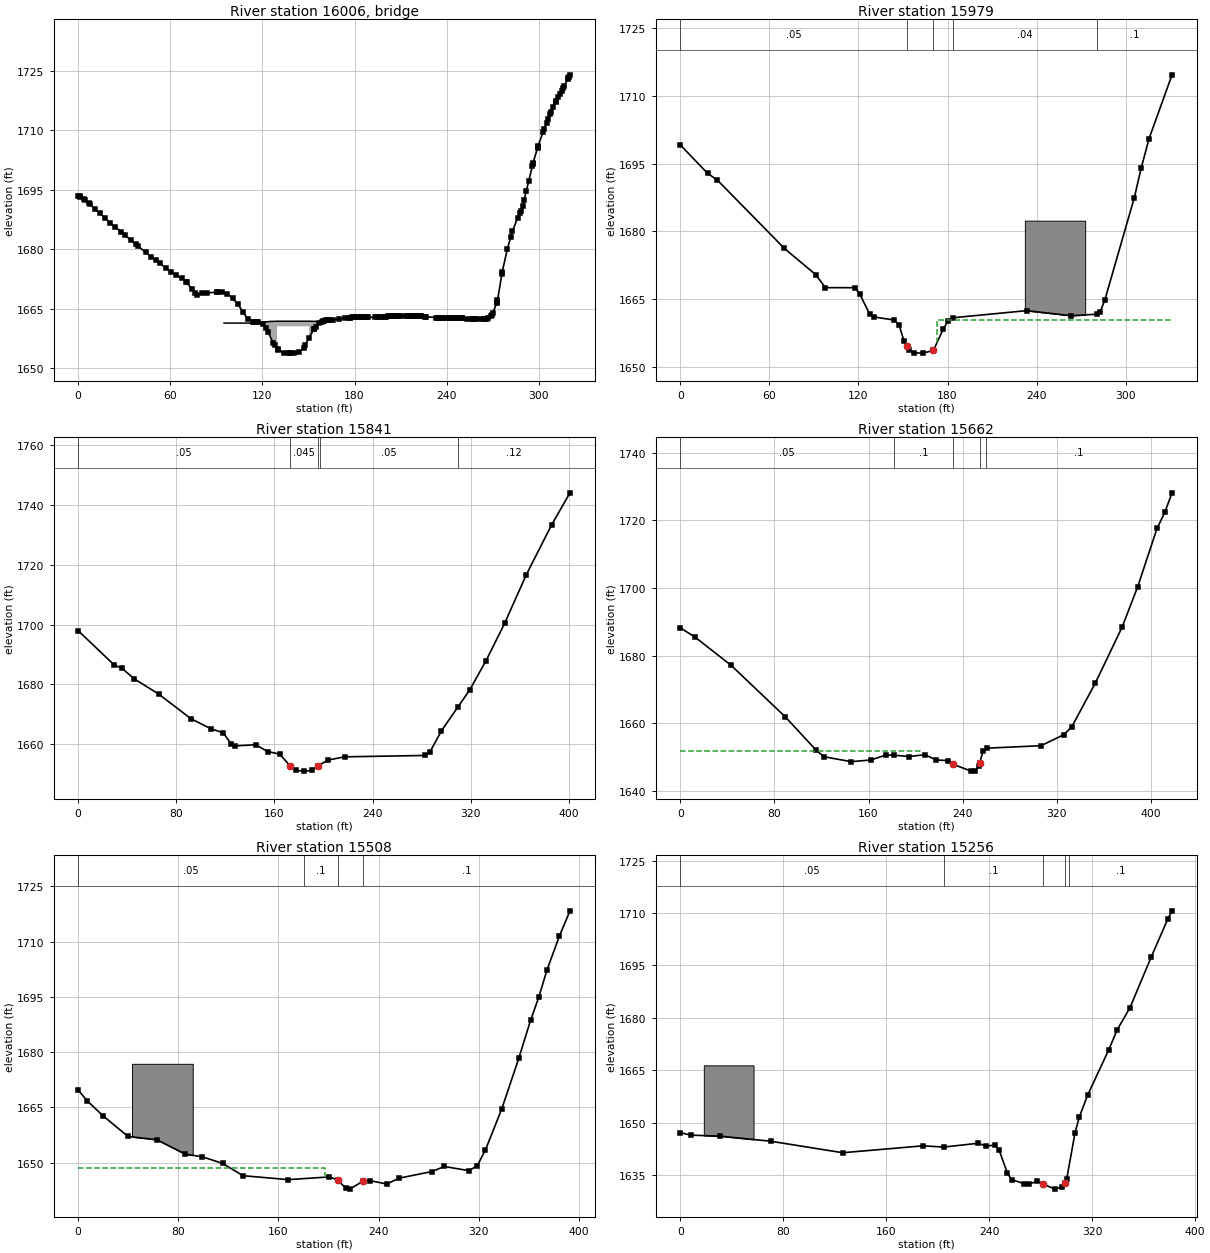
Type RM Length L Ch R = 3 ,16006   ,,,
BEGIN DESCRIPTION:
Unnamed Road
Survey ID: MAC190
END DESCRIPTION:
Bridge Culvert--1,0,-1,-1, 0
Deck Dist Width WeirC Skew NumUp NumDn MinLoCord MaxHiCord MaxSubmerge Is_Ogee
12,16,2.6,0, 10, 11, , , 0.98, 0, 0,0,,
      95     113     125   129.5   129.5     137   150.5   150.5     154     165
1661.3731661.3731661.7771661.8411661.8411661.8411661.8411661.8411661.807  1661.6
                                1660.5631660.5631660.563
     125     143   150.5   150.5     155     167   171.5   171.5     179     184
     195
1661.3731661.3731661.8411661.8411661.8411661.8411661.8411661.8411661.7681661.807
  1661.6
                        1660.5631660.5631660.5631660.563
        
BR Coef=-1 , 1 , 0 ,, 0 ,,,0.8,0,1.2,0,
WSPro=,,,, 1 ,,,, 0 ,,,, 0 ,,,,-1 ,-1 ,-1 , 0 , 0 , 0 , 0 , 0
BR U #Sta/Elev= 181
       0 1693.52       1 1693.33     1.3 1693.25     3.6 1692.64     4.3 1692.44
     7.1 1691.57     7.6 1691.39    10.9 1690.06    14.3 1689.03    17.6 1687.84
    20.9 1686.56    24.2 1685.59      28 1684.39    30.8 1683.46    34.2 1682.32
    37.5 1681.23    38.7 1680.84    44.1 1679.17    47.6 1678.12    50.8  1677.2
    53.1 1676.47    57.4 1675.16    60.7 1674.28      64 1673.38    67.4 1672.62
    70.4 1671.73    70.7 1671.62      74    1670    76.1 1669.08    77.3 1668.57
    80.6 1668.85      84 1668.99    90.5 1669.16    90.6 1669.16    93.9 1669.14
    97.2 1668.78   100.6 1667.59   103.9 1666.21   107.2 1664.23   110.5  1662.4
   113.8 1661.76   114.3 1661.73   116.4 1661.62   117.2 1661.57   120.5 1661.05
   122.1 1660.06   123.8 1659.03   127.1 1656.32   127.9 1655.89     130 1654.84
   130.4  1654.6   133.8 1653.88   137.1  1653.8   137.8  1653.8   140.4 1653.81
   143.7    1654     147 1655.19     148 1655.93   150.3 1657.61   153.7 1659.95
   153.8 1659.99   154.6 1660.36     157 1661.52   158.8 1661.77   159.6 1661.88
   160.3 1661.99   161.3 1662.04   162.5 1662.09   163.6 1662.14   166.31662.238
   170.2 1662.38   173.6 1662.64   176.9 1662.77     177 1662.77   178.1 1662.79
   179.9 1662.82   180.2 1662.83   182.21662.842   183.5 1662.85   184.3 1662.85
   185.7 1662.85   186.8 1662.85   188.2 1662.84   188.7 1662.84   193.4  1662.8
   194.5 1662.82   195.9 1662.84   197.4 1662.88   199.7 1662.95     200 1662.96
   200.3 1662.97   202.1 1663.07   203.2 1663.12   203.4 1663.13   203.6 1663.13
   206.1 1663.19   206.7 1663.21   207.4 1663.21     209 1663.25     210 1663.26
   213.3 1663.25   214.9  1663.2   215.1 1663.19   216.6 1663.15   217.8 1663.13
   218.9  1663.1   219.9 1663.09   220.7 1663.08   222.8 1663.06   223.2 1663.05
   223.6 1663.04   226.1 1662.98   226.5 1662.97   233.2 1662.76   234.3 1662.74
   235.2 1662.72   236.5  1662.7   238.1 1662.67   239.8 1662.65     241 1662.65
     242 1662.66   243.1 1662.66     244 1662.69   245.8 1662.71   246.4 1662.72
   246.9 1662.72   249.7 1662.63   249.8 1662.62   250.1 1662.59     253 1662.34
   256.3  1662.3   257.3  1662.3   258.5  1662.3   259.7 1662.31     263  1662.3
   264.3 1662.36     265 1662.39   266.3 1662.45   267.2 1662.73   268.9 1663.23
   269.6 1663.45   270.1 1663.97   272.7 1666.53   272.9 1666.73   273.1 1667.09
     276 1673.76   276.2  1674.3   279.5 1680.02   281.8  1683.1   282.8 1684.49
   286.2 1687.89   287.6 1689.19   288.1 1689.59   289.5 1690.83   290.5 1692.52
   291.9 1694.72   293.4 1697.13   295.8 1700.94   296.1 1701.47   296.3 1701.78
   299.3 1705.63   299.4 1705.85   299.6 1706.07   302.7  1709.5   303.4 1710.22
   305.1 1711.87     306  1712.8   307.3 1713.98     308 1714.65   309.3 1715.91
   310.9 1717.07   311.1 1717.24   312.7 1718.37   313.8 1719.16     315 1719.98
     316 1720.67   316.7 1721.24   318.8 1722.82   319.3 1723.18   319.6 1723.45
   320.3 1723.95
BR U #Mann= 6
       0      .1    76.1    .016    97.2     .05   127.9     .04     147     .05
   309.3      .1
BR D #Sta/Elev= 169
       0 1699.16     5.5 1697.49     8.5 1696.52    11.8  1695.3    15.1 1693.89
    18.4 1692.84    21.7 1692.25      25 1691.34    29.1 1689.99      32 1688.95
      35 1687.97    38.3 1686.95    44.9 1684.59    55.5 1681.11    58.1 1680.29
    61.4  1679.2    64.7 1677.96      68 1676.88      69 1676.58    70.2 1676.18
    77.9 1673.79      79 1673.49    81.2 1672.88    84.9 1672.05    87.8 1671.25
    87.9 1671.22    91.2 1670.39    94.5 1668.99    97.8  1667.5   101.1 1667.39
   104.4 1667.55   106.8  1667.6   107.7 1667.63   108.4 1667.64   110.5 1667.67
     111 1667.67   111.4 1667.67   114.3 1667.69   117.6 1667.49   120.2 1666.39
   120.9 1666.09   124.2 1663.77   127.5 1661.69   130.8 1660.99     132 1660.92
   133.2 1660.85   134.1 1660.79   137.5 1660.63   140.8  1660.5   144.1 1660.32
   147.4 1659.23   150.7 1655.65   152.1 1654.81   152.5 1654.55     154 1653.66
   155.5 1653.38   157.3 1653.06   158.4 1653.03   158.51653.029   159.6 1653.02
   160.6    1653   161.4    1653   163.4 1652.99   167.2    1653   170.5 1653.58
   173.8 1655.92   174.7 1656.59   175.61657.188   176.1 1657.52   177.1 1658.32
   180.4 1660.12   183.7 1660.83   184.9 1660.87   186.1  1660.9   186.6 1660.92
     187 1660.94   187.8 1660.96   189.8    1661   190.3 1661.02   196.8 1661.34
   196.9 1661.35   197.1 1661.35   199.8 1661.51   200.2 1661.53   200.8 1661.55
   202.8  1661.6   203.5 1661.62   206.8 1661.76   210.1 1661.86   211.8 1661.88
   213.4  1661.9   214.7 1661.93   215.5 1661.95   216.7 1661.98   223.7 1662.05
   226.5 1662.12   226.6 1662.12   226.7 1662.12   227.5 1662.16   229.7 1662.25
   229.9 1662.26   232.7 1662.37   233.2  1662.4   233.9  1662.4   235.7  1662.4
   236.5  1662.4   237.5 1662.31   238.7 1662.21   239.8 1662.11   241.7 1661.97
   243.1 1661.87   246.4  1661.7   247.6 1661.66   248.6 1661.64   249.7 1661.61
   263.3 1661.29   265.6 1661.28   266.2 1661.27     267 1661.27   272.8 1661.26
   276.1 1661.27   277.5 1661.32     278 1661.34   279.4  1661.4   280.5 1661.61
   281.7 1661.83   282.7 1662.02   283.5 1662.75   285.3 1664.29     286 1664.85
   286.5 1665.49     289 1668.53   289.3 1668.87   289.5 1669.11   291.7 1671.45
   292.5 1672.37   292.6 1672.47   295.9 1676.08   296.4 1676.67   298.5  1679.1
   299.2 1679.96     300 1680.91   301.5 1682.49   302.5 1683.58   303.7 1685.05
   304.5 1685.92   305.8 1687.47   307.4 1689.82   309.1 1692.23   310.4 1693.99
   311.1 1694.83   312.4 1696.51   314.8 1699.42   315.7 1700.53   316.4 1701.27
   318.4 1703.19     319 1703.72   319.4 1704.13   322.1 1706.43   322.3 1706.58
   322.4  1706.7   323.7 1707.93   325.4 1709.51   325.6 1709.68   325.8 1709.87
   328.4 1712.19   328.9 1712.61   329.5 1713.13   331.2 1714.67
BR D #Mann= 5
       0     .05   152.5     .04   170.5     .04   183.7     .04   280.5      .1
BC Design=,, 0 ,, 0 ,,,,,,
BC Use User HTab Curves=0
BC User HTab FreeFlow(D)= 0

Type RM Length L Ch R = 1 ,15979   ,137.6,138.2,137.6
XS GIS Cut Line= 3
1986599.00999263247600.0600002051986575.94800123247414.879999385
1986561.15000737247271.034005121
#Sta/Elev= 30
       0 1699.16    18.4 1692.84      25 1691.34    70.2 1676.18    91.2 1670.39
    97.8  1667.5   117.6 1667.49   120.9 1666.09   127.5 1661.69   130.8 1660.99
   144.1 1660.32   147.4 1659.23   150.7 1655.65   152.5 1654.55     154 1653.66
   157.3 1653.06   163.4 1652.99   170.5 1653.58   177.1 1658.32   180.4 1660.12
   183.7 1660.83   233.2  1662.4   263.3 1661.29   280.5 1661.61   282.7 1662.02
     286 1664.85   305.8 1687.47   310.4 1693.99   315.7 1700.53   331.2 1714.67
#Mann= 5 ,-1 , 0
       0     .05       0   152.5    .045       0   170.5     .04       0
   183.7     .04       0   280.5      .1       0
#XS Ineff= 2 , 0
        147.1667  1657.7172.8333         1660.39
Permanent Ineff=
       F       F
#Block Obstruct= 1 ,-1
  232.07   272.7 1682.35
Bank Sta=152.5,170.5
XS Rating Curve= 0 ,0
Exp/Cntr=0.5,0.3

Type RM Length L Ch R = 1 ,15841   ,180,179.6,179.9
XS GIS Cut Line= 2
     1986732.907      247633.957     1986696.014      247234.652
#Sta/Elev= 30
       0 1697.97    29.3 1686.52    35.9 1685.32    45.8 1681.84    65.6 1676.78
    91.9 1668.54   108.4 1665.14   118.3 1663.83   124.9 1659.99   128.2 1659.46
   144.7  1659.8   154.5 1657.56   164.4 1656.69   172.81652.757   177.6 1651.24
   184.4    1651   190.8 1651.24   195.61652.836     204 1654.71   217.2 1655.78
     283 1656.24   286.6 1657.24   296.2 1664.47   309.4  1672.3   319.3 1678.18
   332.5 1687.88   347.7 1700.39   365.4 1716.67   386.1 1733.39     401 1744.04
#Mann= 5 ,-1 , 0
       0     .05       0   172.8    .045       0   195.6     .05       0
   196.9     .05       0   309.4     .12       0
Bank Sta=172.8,195.6
XS Rating Curve= 0 ,0
Exp/Cntr=0.3,0.1

Type RM Length L Ch R = 1 ,15662   ,149.6,153.7,151
XS GIS Cut Line= 2
     1986913.028       247677.36     1986881.561      247260.693
#Sta/Elev= 30
       0 1688.27    12.7 1685.45    43.2 1677.15    89.3 1661.88   115.6 1651.99
   122.2 1650.08   145.2 1648.64   161.7 1649.11   174.8 1650.59   181.9 1650.54
   194.6 1650.14   207.7  1650.7   217.6 1649.12   227.5 1648.96   231.8 1647.85
   247.2 1645.83   250.5 1645.84   253.8 1647.32   254.61648.301   257.1 1651.65
   260.4 1652.62   306.5 1653.35   326.2 1656.66   332.8 1659.01   352.8 1671.96
   375.5 1688.47   388.7  1700.4   405.1 1717.63   411.7 1722.37   417.9 1728.18
#Mann= 5 ,-1 , 0
       0     .05       0   181.9      .1       0   231.8    .045       0
   254.6      .1       0   259.4      .1       0
#XS Ineff= 2 , 0
          203.38 1651.68
Permanent Ineff=
       F       F
Bank Sta=231.8,254.6
XS Rating Curve= 0 ,0
Exp/Cntr=0.3,0.1

Type RM Length L Ch R = 1 ,15508   ,246,251.6,242.7
Node Name=E
XS GIS Cut Line= 2
     1987045.407      247680.615     1987039.981       247287.82
#Sta/Elev= 30
       0 1669.75       7 1666.88    20.1 1662.66    39.8 1657.14    62.8 1656.25
    85.7 1652.31    98.9 1651.64   115.3 1649.83   131.7 1646.48   167.8 1645.42
   200.6 1646.15   207.31645.345   213.7 1643.06     217 1642.84   227.3 1644.96
   233.4 1645.13   246.5 1644.22   256.4 1645.82   282.6 1647.61   292.4 1648.98
   312.1 1647.85   318.7 1649.16   325.3 1653.47   338.4 1664.68   351.9 1678.31
   361.3  1688.6   367.9 1694.93   374.5 1702.35   384.3 1711.45   392.8 1718.34
#Mann= 4 ,-1 , 0
       0     .05       0     180      .1       0   207.3    .045       0
   227.3      .1       0
#XS Ineff= 2 , 0
          197.18 1648.64
Permanent Ineff=
       F       F
#Block Obstruct= 1 ,-1
      43   91.53 1676.84
Bank Sta=207.3,227.3
XS Rating Curve= 0 ,0
Exp/Cntr=0.3,0.1

Type RM Length L Ch R = 1 ,15256   ,166.5,175.5,170.8
XS GIS Cut Line= 2
     1987268.931        247681.7     1987278.697      247299.755
#Sta/Elev= 30
       0 1647.15     8.1 1646.42      31 1646.13    70.4 1644.67   126.2 1641.38
   188.7 1643.36   204.7    1643   231.2 1644.08   237.8 1643.32   244.4 1643.54
   247.6  1642.3   254.2 1635.51   257.5 1633.67   267.3  1632.5   270.6 1632.38
   277.2 1633.17   282.11632.395   291.1 1630.96   296.9 1631.63   298.71632.809
   300.2 1633.76   306.7 1647.05     310 1651.57   316.6 1657.94     333 1670.93
   339.5  1676.6   349.4  1682.9   365.8 1697.33   378.9  1708.4   382.1 1710.64
#Mann= 5 ,-1 , 0
       0     .05       0   204.7      .1       0   282.1    .045       0
   298.7      .1       0   302.1      .1       0
#Block Obstruct= 1 ,-1
   18.32   56.96  1666.4
Bank Sta=282.1,298.7
XS Rating Curve= 0 ,0
Exp/Cntr=0.3,0.1

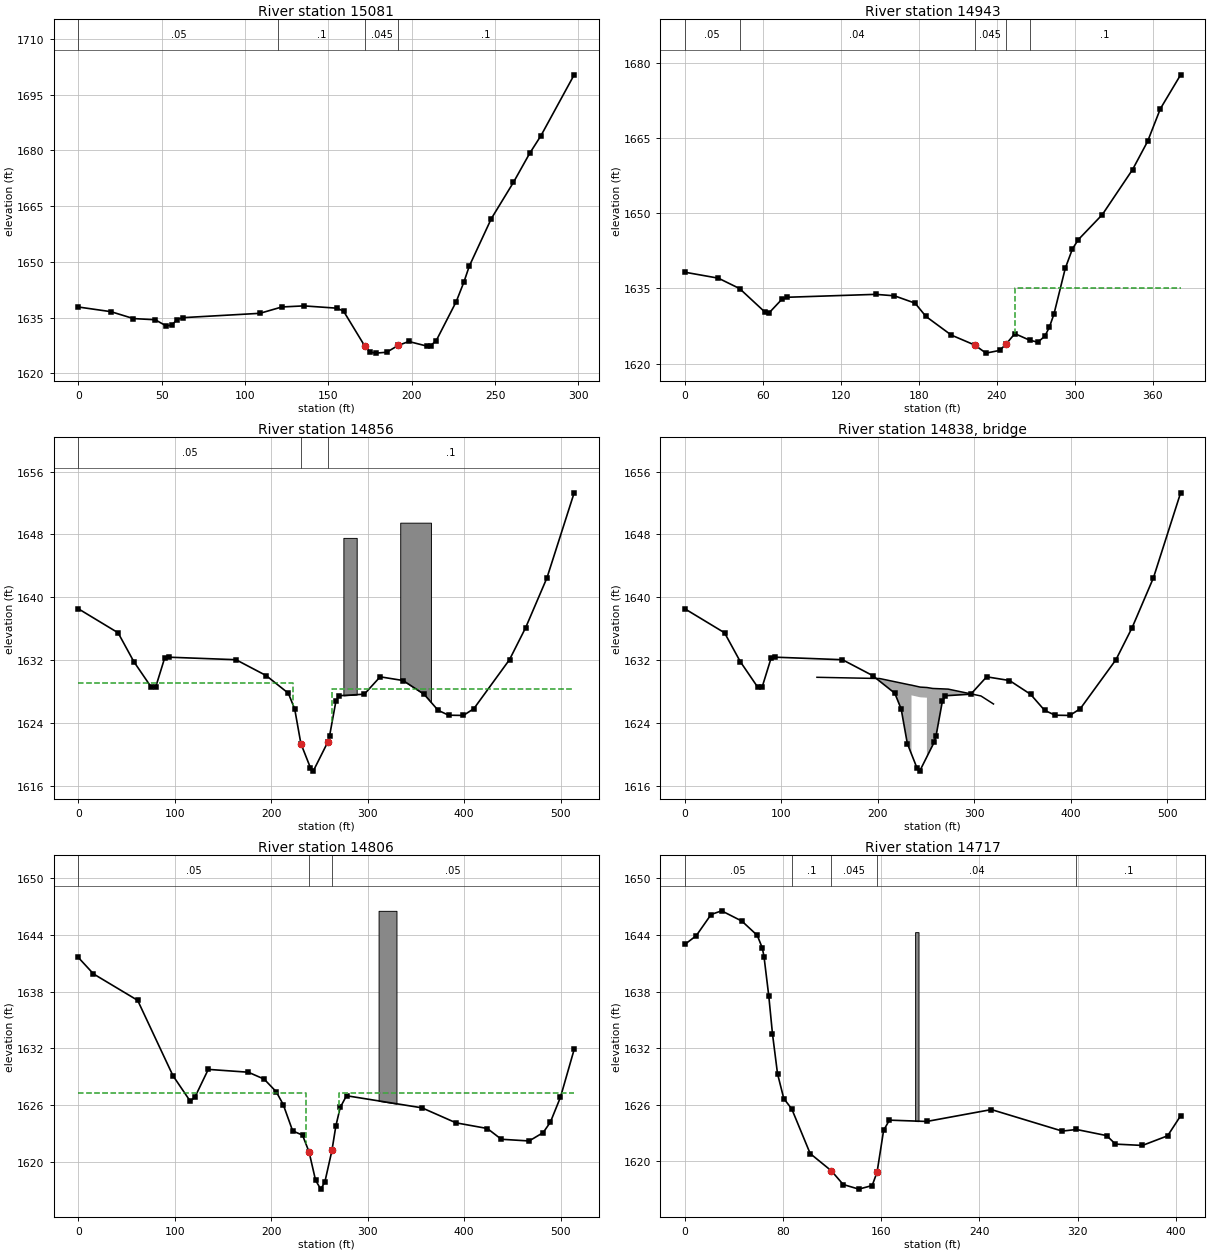
Type RM Length L Ch R = 1 ,15081   ,126.5,137.7,148.4
XS GIS Cut Line= 2
     1987417.585      247624.191     1987454.478      247329.052
#Sta/Elev= 30
       0 1637.87    19.6 1636.61      33 1634.76    46.1 1634.44    52.7 1632.78
      56 1633.01    59.3 1634.49    62.6    1635   108.9 1636.17   122.1 1637.88
   135.3 1638.17   155.2 1637.55   159.1 1636.74   171.9 1627.29     175 1625.76
   178.3 1625.46   184.9 1625.69   191.91627.544   198.2 1628.59     209 1627.36
   211.4  1627.5   214.7 1628.85   226.7 1639.35   231.2  1644.5   234.5 1648.87
   247.7 1661.64     261 1671.42   270.7  1679.2   277.5 1683.98   297.4 1700.34
#Mann= 4 ,-1 , 0
       0     .05       0     120      .1       0   171.9    .045       0
   191.9      .1       0
#Block Obstruct= 2 , 0
           12.92 1657.87
Bank Sta=171.9,191.9
XS Rating Curve= 0 ,0
Exp/Cntr=0.3,0.1

Type RM Length L Ch R = 1 ,14943   ,67.7,87.6,100.9
XS GIS Cut Line= 3
     1987421.926      247635.042     1987542.368      247495.068
     1987674.747      247349.669
#Sta/Elev= 30
       0 1638.23    25.8 1637.04    42.1 1634.97    61.6 1630.28    64.7 1630.08
    74.6 1632.81    78.9 1633.23   146.8 1633.81   161.2 1633.52   177.1 1632.05
   185.4 1629.41   204.9 1625.69     2231623.687   231.6 1622.08   242.1 1622.62
   246.91623.833   253.8 1625.97   265.3 1624.65   271.5 1624.27   276.9 1625.47
   280.4 1627.27   283.9 1629.89   292.6 1639.01   298.1 1642.88   302.6 1644.72
   321.1 1649.73   344.3 1658.69   355.9 1664.33   365.7 1670.84   381.3 1677.62
#Mann= 5 ,-1 , 0
       0     .05       0    42.1     .04       0     223    .045       0
   246.9     .04       0   265.3      .1       0
#XS Ineff= 2 , 0
                             254            1635
Permanent Ineff=
       F       F
#Block Obstruct= 2 , 0
           19.59 1658.23
Bank Sta=223,246.9
XS Rating Curve= 0 ,0
Exp/Cntr=0.5,0.3

Type RM Length L Ch R = 1 ,14856   ,53.8,49.7,51
XS GIS Cut Line= 6
     1987430.606      247645.893     1987544.539      247528.705
     1987592.417      247525.162     1987710.689      247527.332
     1987759.382      247503.748     1987813.636      247385.476
#Sta/Elev= 30
       0 1638.53    41.2 1635.47    57.5  1631.8    75.7 1628.52    80.3  1628.6
    89.4 1632.22      94 1632.36   163.4 1632.04   194.7 1630.02   217.7 1627.77
   224.3 1625.76   230.71621.357  240.58 1618.28   243.51617.846   258.51621.523
   260.4  1622.3     267 1626.74   270.2 1627.45   296.5 1627.65   312.9 1629.86
   336.6 1629.39   358.4 1627.64     373 1625.59   383.9 1624.97   399.1 1624.94
     410  1625.8     447 1632.05   463.7 1636.12   485.8 1642.47     514  1653.3
#Mann= 3 ,-1 , 0
       0     .05       0   230.7    .045       0   258.5      .1       0
#XS Ineff= 2 , 0
             223  1629.1     263         1628.35
Permanent Ineff=
       F       F
#Block Obstruct= 2 ,-1
  274.77  288.56 1647.56   333.7  365.53  1649.5
Bank Sta=230.7,258.5
XS Rating Curve= 0 ,0
Exp/Cntr=0.5,0.3

Type RM Length L Ch R = 3 ,14838   ,,,
BEGIN DESCRIPTION:
Madams Creek Rd
Survey ID: MAC180
END DESCRIPTION:
Bridge Culvert--1,0,-1,-1, 0
Deck Dist Width WeirC Skew NumUp NumDn MinLoCord MaxHiCord MaxSubmerge Is_Ogee
12,26,2.6,0, 12, 12, , , 0.98, 0, 0,0,,
     137     202     233     235     235     244     251     251     257     273
     307     320
  1629.81629.6431628.843  1628.8  1628.81628.551  1628.5  1628.51628.3791628.295
1627.421  1626.4
                                  1627.51627.251  1627.2
                
     137     202     233     245     245     251     257     261     261     273
     307     320
  1629.81629.6431628.8431628.5511628.551  1628.51628.379  1628.4  1628.41628.295
1627.421  1626.4
                                1627.251  1627.21627.079  1627.1
                
BR Coef=-1 , 1 , 0 ,, 0 ,,,0.8,0,1.2,0,
WSPro=,,,, 1 ,,,, 0 ,,,, 0 ,,,,-1 ,-1 ,-1 , 0 , 0 , 0 , 0 , 0
BR U #Sta/Elev= 30
       0 1638.53    41.2 1635.47    57.5  1631.8    75.7 1628.52    80.3  1628.6
    89.4 1632.22      94 1632.36   163.4 1632.04   194.7 1630.02   217.7 1627.77
   224.3 1625.76   230.71621.357  240.58 1618.28   243.51617.846   258.51621.523
   260.4  1622.3     267 1626.74   270.2 1627.45   296.5 1627.65   312.9 1629.86
   336.6 1629.39   358.4 1627.64     373 1625.59   383.9 1624.97   399.1 1624.94
     410  1625.8     447 1632.05   463.7 1636.12   485.8 1642.47     514  1653.3
BR U #Mann= 3
       0     .05   230.7     .04   258.5      .1
BR D #Sta/Elev= 30
       0 1641.63    15.7 1639.89    61.5 1637.09    98.1 1629.11   116.1  1626.4
     121 1626.87   134.7 1629.78   176.2 1629.48   192.6 1628.75   205.1 1627.42
   212.4 1626.06   222.2 1623.26   232.4 1622.82   239.21621.034  245.92 1618.04
   251.3  1617.1  255.49 1617.83   262.91621.191     267 1623.81   271.5 1625.75
     278 1626.99   356.2 1625.71   391.5 1624.12     424 1623.52   438.5 1622.38
   467.3  1622.2   481.8 1623.08   489.3 1624.18   499.8 1626.83     514 1631.89
BR D #Mann= 3
       0     .05   239.2     .04   262.9     .05
BC Design=,, 0 ,, 0 ,,,,,,
BC Use User HTab Curves=0
BC User HTab FreeFlow(D)= 0

Type RM Length L Ch R = 1 ,14806   ,103.4,89.2,78
XS GIS Cut Line= 6
     1987449.052      247691.466     1987562.985      247574.278
     1987610.863      247570.736     1987729.135      247572.906
     1987777.828      247549.322     1987832.082      247431.049
#Sta/Elev= 30
       0 1641.63    15.7 1639.89    61.5 1637.09    98.1 1629.11   116.1  1626.4
     121 1626.87   134.7 1629.78   176.2 1629.48   192.6 1628.75   205.1 1627.42
   212.4 1626.06   222.2 1623.26   232.4 1622.82   239.21621.034  245.92 1618.04
   251.3  1617.1  255.49 1617.83   262.91621.191     267 1623.81   271.5 1625.75
     278 1626.99   356.2 1625.71   391.5 1624.12     424 1623.52   438.5 1622.38
   467.3  1622.2   481.8 1623.08   489.3 1624.18   499.8 1626.83     514 1631.89
#Mann= 3 ,-1 , 0
       0     .05       0   239.2    .045       0   262.9     .05       0
#XS Ineff= 2 , 0
             236 1627.24     270         1627.24
Permanent Ineff=
       F       F
#Block Obstruct= 1 ,-1
  311.25  329.81 1646.57
Bank Sta=239.2,262.9
XS Rating Curve= 0 ,0
Exp/Cntr=0.5,0.3

Type RM Length L Ch R = 1 ,14717   ,277.7,245.4,214.5
XS GIS Cut Line= 5
      1987574.92      247739.209     1987725.745      247623.106
     1987759.555      247585.396     1987802.785      247528.705
     1987837.507       247444.07
#Sta/Elev= 30
       0 1642.99     9.3 1643.91    21.4 1646.16      30 1646.55    46.5 1645.46
      59 1643.95    63.1 1642.62    64.5 1641.71    68.4 1637.52    71.4 1633.52
    75.5  1629.3    80.6 1626.66    87.1 1625.56   102.1 1620.83   119.41618.996
     129 1617.55   141.7 1617.06   152.6 1617.44   156.61618.865   161.9 1623.28
   166.6 1624.37     197 1624.23   249.7 1625.49   307.4 1623.21     319 1623.38
   343.6 1622.73   350.7 1621.83   372.7 1621.69   393.2 1622.71   403.8 1624.83
#Mann= 5 ,-1 , 0
       0     .05       0    87.1      .1       0   119.4    .045       0
   156.6     .04       0     319      .1       0
#Block Obstruct= 1 ,-1
  187.57  190.34 1644.29
Bank Sta=119.4,156.6
XS Rating Curve= 0 ,0
Exp/Cntr=0.3,0.1

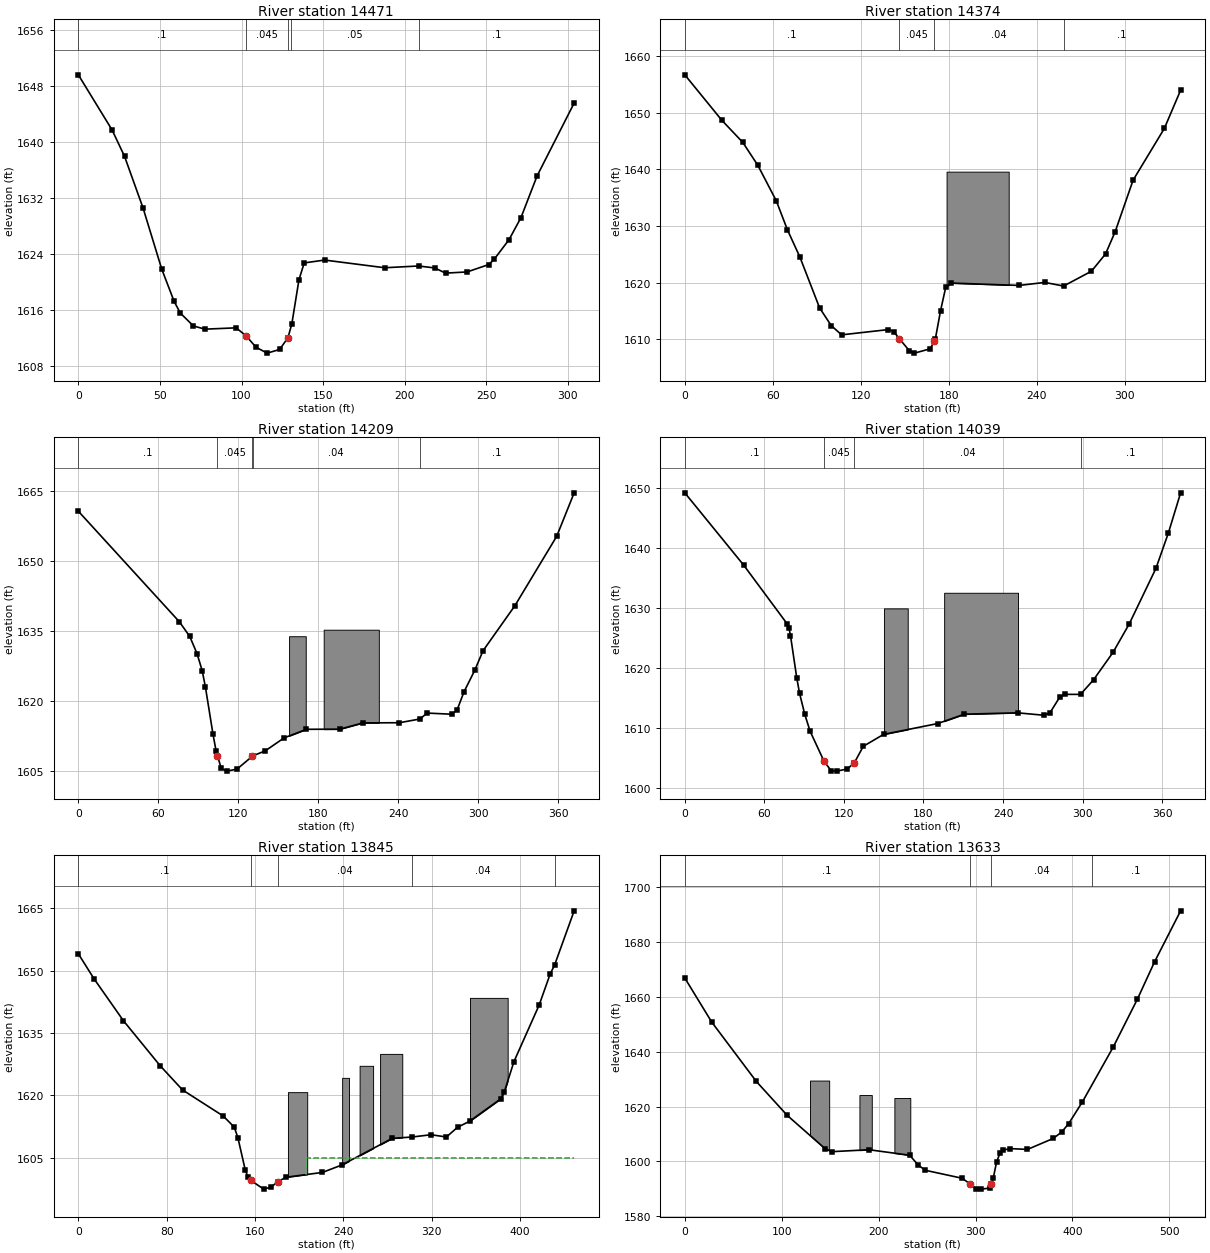
Type RM Length L Ch R = 1 ,14471   ,91.7,97.4,99
XS GIS Cut Line= 3
     1987929.738        247681.7     1987857.039      247556.917
     1987839.677      247398.497
#Sta/Elev= 30
       0 1649.62    20.7 1641.72    28.3 1637.96    39.7 1630.53    51.1 1621.82
    58.7 1617.19    62.5 1615.52    70.5 1613.68    77.6 1613.22    96.7 1613.41
   102.71612.274   108.9 1610.63   115.7 1609.79   123.3 1610.31   128.41611.975
   130.8 1613.96   135.2 1620.31   138.4  1622.7   150.9 1623.11   187.7 1622.01
   208.5 1622.26   218.4 1621.98     225 1621.24   238.2 1621.41   251.4 1622.46
   254.7 1623.19   263.9 1626.03   271.2 1629.18   281.1 1635.16   303.8 1645.58
#Mann= 5 ,-1 , 0
       0      .1       0   102.7    .045       0   128.4     .05       0
   130.5     .05       0   208.5      .1       0
Bank Sta=102.7,128.4
XS Rating Curve= 0 ,0
Exp/Cntr=0.3,0.1

Type RM Length L Ch R = 1 ,14374   ,159.1,164.9,157.5
XS GIS Cut Line= 2
     1988017.629       247683.87     1987888.505       247371.37
#Sta/Elev= 30
       0 1656.72    25.3 1648.68    39.5  1644.8    49.8 1640.74    62.4 1634.46
    69.9 1629.39    78.5 1624.52    91.9 1615.56    99.8 1612.44   106.9 1610.79
   138.9 1611.72   142.4 1611.37   146.31610.109   153.1 1607.99   156.6 1607.56
   167.3 1608.32   170.21609.704   170.8    1610   174.4 1615.06   177.9 1619.16
   181.5 1619.94   228.1 1619.52   245.4 1620.05   258.3 1619.41   277.3 1622.03
   286.9 1625.08   293.5 1629.03   305.7 1638.12     327 1647.25   338.1 1654.01
#Mann= 4 ,-1 , 0
       0      .1       0   146.3    .045       0   170.2     .04       0
   258.3      .1       0
#Block Obstruct= 1 ,-1
   178.5  220.87 1639.62
Bank Sta=146.3,170.2
XS Rating Curve= 0 ,0
Exp/Cntr=0.3,0.1

Type RM Length L Ch R = 1 ,14209   ,174.4,169.8,163.8
XS GIS Cut Line= 2
     1988182.559      247622.021     1987977.481      247311.691
#Sta/Elev= 30
       0  1660.7    75.8 1636.99    83.6 1633.84    89.1 1630.12    92.9 1626.53
    95.3 1623.08     101 1612.93   103.3 1609.37   104.41608.255   107.2 1605.55
   111.2 1604.96     119 1605.38   130.51608.134   130.8 1608.22   140.3 1609.32
   154.4 1612.09   171.1 1613.93   196.2 1613.96   213.4  1615.3   240.9 1615.34
   256.3 1616.14   261.7 1617.41   280.3 1617.16   284.2 1618.11   289.4 1621.99
   297.4 1626.57   303.6 1630.76   327.5 1640.42   358.9 1655.31     372 1664.64
#Mann= 5 ,-1 , 0
       0      .1       0   104.4    .045       0   130.5     .04       0
   130.8     .04       0   256.3      .1       0
#Block Obstruct= 2 ,-1
  158.11  170.62 1633.89  184.09  225.45 1635.29
Bank Sta=104.4,130.5
XS Rating Curve= 0 ,0
Exp/Cntr=0.3,0.1

Type RM Length L Ch R = 1 ,14039   ,200.5,194.6,187.1
XS GIS Cut Line= 2
      1988345.32      247487.473      1988039.33      247272.629
#Sta/Elev= 30
       0 1649.15    44.4 1637.11    77.3  1627.3    78.5 1626.69    79.7 1625.39
    84.4 1618.37    86.5 1615.81    90.5 1612.24    94.5 1609.45     105 1604.45
   110.3  1602.9   114.6 1602.81   122.6 1603.17   127.91604.217   134.6 1606.94
   149.9 1608.93   190.7 1610.73   210.8 1612.29   250.9 1612.52   270.5 1612.12
   275.2 1612.46   282.9 1615.19   286.9 1615.59   298.4 1615.59   308.2 1618.01
     323 1622.61   335.1  1627.3   355.3 1636.58   364.7 1642.49   373.9 1649.15
#Mann= 4 ,-1 , 0
       0      .1       0     105    .045       0   127.9     .04       0
   298.4      .1       0
#Block Obstruct= 2 ,-1
  150.18  168.11 1629.91  195.58  251.27 1632.51
Bank Sta=105,127.9
XS Rating Curve= 0 ,0
Exp/Cntr=0.3,0.1

Type RM Length L Ch R = 1 ,13845   ,209.9,211.5,215.8
XS GIS Cut Line= 3
     1988488.549      247282.395     1988271.535      247240.077
     1988057.776      247160.867
#Sta/Elev= 30
       0 1654.04    14.2 1648.03    40.9 1637.91    74.3 1627.04    94.4 1621.27
   131.2    1615   141.2 1612.33   144.5 1609.81   151.2 1601.99   153.8 1600.21
   156.11599.522   167.9  1597.4   174.6  1597.9   180.4 1599.13     188 1600.26
   221.1 1601.42   238.6  1603.2   284.4 1609.63   301.9 1609.93   319.4 1610.49
   333.4 1609.95   343.5 1612.29   354.4 1613.74   382.4 1619.09   385.9 1620.88
   394.6 1628.11   417.4 1641.71   427.4  1649.2   431.4 1651.35   449.1 1664.38
#Mann= 5 ,-1 , 0
       0      .1       0   156.1    .045       0   180.4     .04       0
   301.9     .04       0   431.4      .1       0
#XS Ineff= 2 , 0
                             206            1605
Permanent Ineff=
       F       F
#Block Obstruct= 5 ,-1
  189.85  207.31 1620.74  238.94  245.14 1624.18  254.76     267 1627.08
  273.31  293.41 1629.95  354.74  388.88 1643.43
Bank Sta=156.1,180.4
XS Rating Curve= 0 ,0
Exp/Cntr=0.3,0.1

Type RM Length L Ch R = 1 ,13633   ,123.3,123.1,123.4
XS GIS Cut Line= 2
     1988566.001      247163.937     1988092.043      246971.229
#Sta/Elev= 30
       0 1666.82    27.8 1650.76    73.8 1629.14   105.7 1616.76   144.8 1604.62
   151.7 1603.55   190.1 1604.25   232.1 1602.25   240.4 1598.82     248 1596.78
   286.3 1593.85   293.91591.888   300.5 1589.99   305.9  1589.9   314.7 1590.29
   316.41591.807   318.2  1593.8   321.7 1599.78   325.3 1603.12   327.9 1604.09
   335.9 1604.66   353.6 1604.37   380.2 1608.37   388.9 1610.71   396.1 1613.76
   410.3 1621.72   442.2 1641.76     467 1659.12   484.7 1672.71   511.6  1691.3
#Mann= 4 ,-1 , 0
       0      .1       0   293.9    .045       0   316.4     .04       0
     420      .1       0
#Block Obstruct= 3 ,-1
  129.18  148.98 1629.46  180.18  192.93 1624.18  216.25  232.67  1623.1
Bank Sta=293.9,316.4
XS Rating Curve= 0 ,0
Exp/Cntr=0.3,0.1

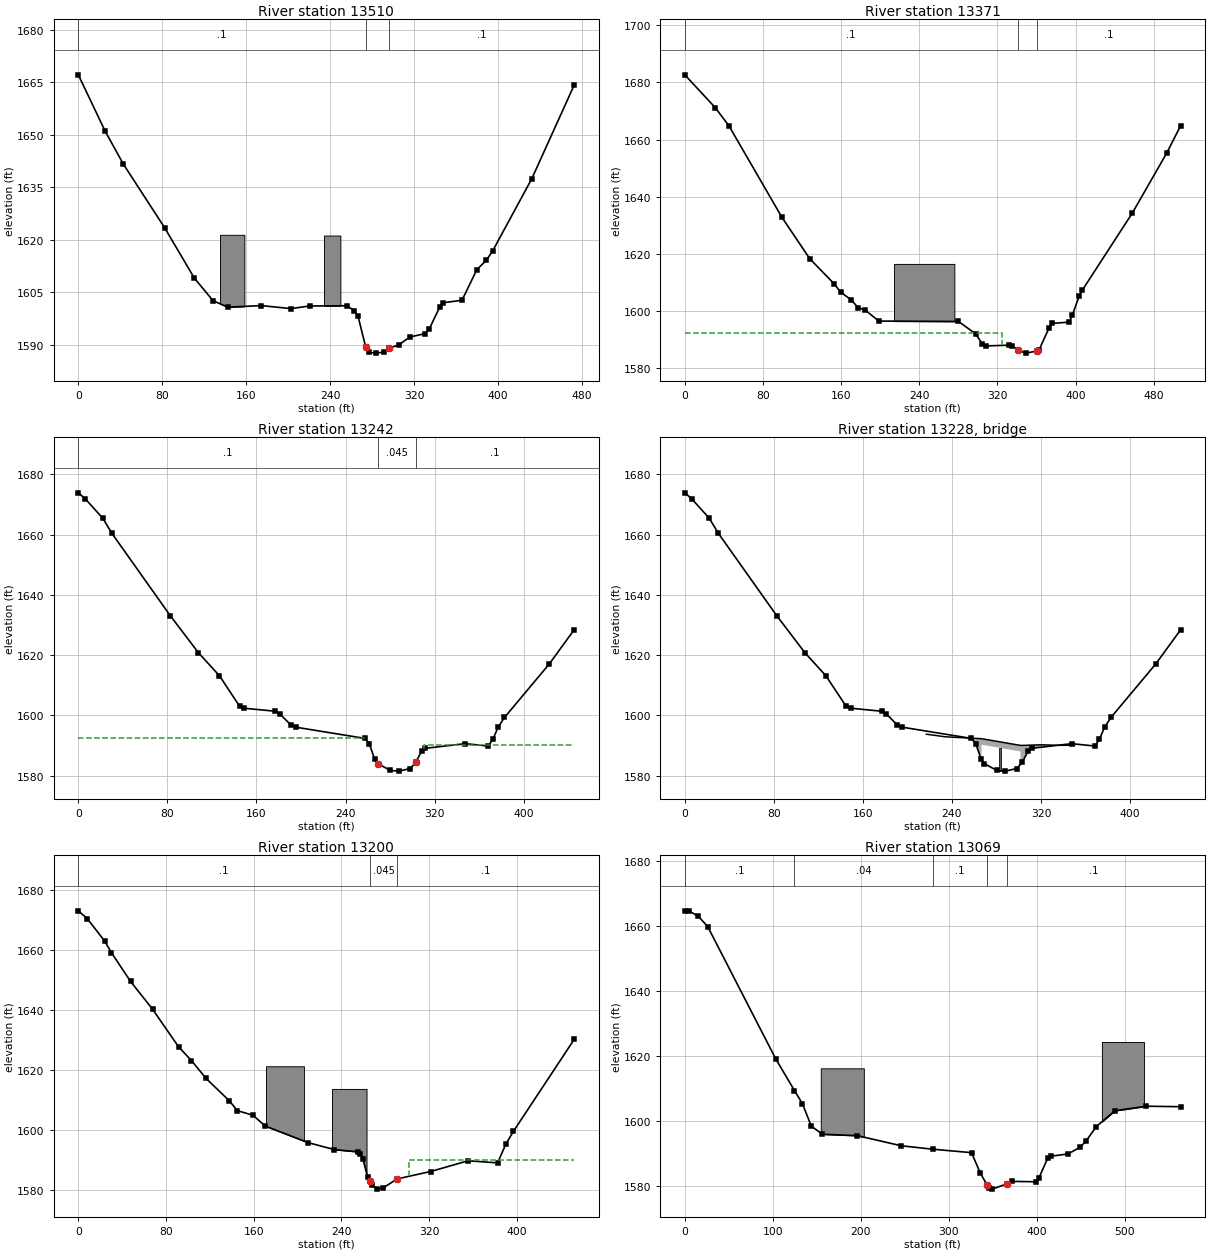
Type RM Length L Ch R = 1 ,13510   ,140.6,138.7,136.7
XS GIS Cut Line= 2
     1988616.348      247056.299     1988178.848      246877.479
#Sta/Elev= 30
       0 1667.18    25.5 1651.12    42.8 1641.72    82.2 1623.52   110.6 1609.08
   128.4 1602.64   142.5 1600.79   174.4 1601.24   202.7 1600.38   220.4 1601.13
   255.9  1601.2     263 1599.79   266.5 1598.34   273.81589.523   277.1 1587.86
   283.9 1587.66   291.3 1587.96   296.11589.005   305.5 1590.05   316.1 1592.28
   330.3 1593.21   334.7 1594.69   344.5 1600.86     348 1602.07   365.7 1602.76
   379.9 1611.54   388.8 1614.15   395.1 1616.97   432.2 1637.48   472.6 1664.24
#Mann= 3 ,-1 , 0
       0      .1       0   273.8    .045       0   296.1      .1       0
#Block Obstruct= 2 ,-1
  135.03  158.24 1621.47   234.1  249.78 1621.26
Bank Sta=273.8,296.1
XS Rating Curve= 0 ,0
Exp/Cntr=0.3,0.1

Type RM Length L Ch R = 1 ,13371   ,115.5,129.2,135.2
XS GIS Cut Line= 3
     1988697.946      246938.243     1988425.376      246827.132
     1988220.515      246768.104
#Sta/Elev= 30
       0 1682.68    31.2 1671.17    45.1 1664.86    99.4 1632.76   127.8  1618.3
   152.6 1609.55   159.7 1606.49   170.3 1603.86   177.4  1601.1   184.5 1600.29
   198.6 1596.41   280.1 1596.28   297.7 1591.93   304.5 1588.41   307.9  1587.7
   331.8 1587.96   335.3 1587.73   340.61586.251   348.9 1585.18   360.61585.911
   362.6 1586.29   372.8 1593.98   376.2  1595.6   393.3 1596.04   396.7 1598.48
   403.5 1605.04     407  1607.3   458.2 1634.33   493.1 1655.18   507.5 1664.84
#Mann= 3 , 0 , 0
       0      .1       0   340.6    .045       0   360.6      .1       0
#XS Ineff= 2 , 0
             325 1592.36
Permanent Ineff=
       F       F
#Block Obstruct= 1 ,-1
  214.09  275.91 1616.44
Bank Sta=340.6,360.6
XS Rating Curve= 0 ,0
Exp/Cntr=0.5,0.3

Type RM Length L Ch R = 1 ,13242   ,42.6,41.9,41.1
XS GIS Cut Line= 4
1988699.54262753246886.7461548191988414.61868927246692.831710244
1988390.34881083246673.9674965761988321.29645661246662.251442782
#Sta/Elev= 30
       0 1673.87     6.1 1671.93      22 1665.42      30  1660.5    82.5 1633.12
   107.9 1620.78   126.8 1613.11     145 1602.95     149 1602.35   176.8 1601.36
   180.8 1600.56   190.6  1596.9   195.3 1596.06   257.5 1592.33   261.4 1590.56
   266.1 1585.51   269.1 1583.95   280.3 1581.69   287.9 1581.47   298.3 1582.34
   303.1 1584.42   308.7  1588.3   311.7 1589.04   347.6 1590.59   368.4  1589.8
   372.5 1592.14   377.1 1596.03   382.8 1599.28     423 1617.03   445.4  1628.4
#Mann= 3 , 0 , 0
       0      .1       0   269.1    .045       0   303.1      .1       0
#XS Ineff= 2 , 0
           257.5  1592.6   310.5          1590.1
Permanent Ineff=
       F       F
Bank Sta=269.1,303.1
XS Rating Curve= 0 ,0
Exp/Cntr=0.5,0.3

Type RM Length L Ch R = 3 ,13228   ,,,
BEGIN DESCRIPTION:
Unnamed Road
Survey ID: MAC170
END DESCRIPTION:
Bridge Culvert--1,0,-1,-1, 0
Deck Dist Width WeirC Skew NumUp NumDn MinLoCord MaxHiCord MaxSubmerge Is_Ogee
9,16,2.6,0, 11, 11, , , 0.98, 0, 0,0,,
     217     234     252   266.5   266.5   301.5   301.5     303     320     336
     350
 1593.731592.8681592.517 1592.24 1592.241590.0111590.0111590.0111590.208 1590.05
 1590.05
                                 1590.241588.011
        
     217     234     255   264.5   264.5   299.5   299.5     301     320     336
     350
 1593.731592.8681592.517 1592.24 1592.241590.0111590.0111590.0111590.208 1590.05
 1590.05
                                 1590.241588.011
        
Pier Skew, UpSta & Num, DnSta & Num=  ,283, 2 ,283, 2 , 0 , 0 , 0 ,,
     1.5     1.5
       0    1591
     1.5     1.5
       0    1591
BR Coef=-1 , 1 , 0 ,1.25, 0 ,,,0.8,0,2,0,
WSPro=,,,, 1 ,,,, 0 ,,,, 0 ,,,,-1 ,-1 ,-1 , 0 , 0 , 0 , 0 , 0
BR U #Sta/Elev= 30
       0 1673.87     6.1 1671.93      22 1665.42      30  1660.5    82.5 1633.12
   107.9 1620.78   126.8 1613.11     145 1602.95     149 1602.35   176.8 1601.36
   180.8 1600.56   190.6  1596.9   195.3 1596.06   257.5 1592.33   261.4 1590.56
   266.1 1585.51   269.1 1583.95   280.3 1581.69   287.9 1581.47   298.3 1582.34
   303.1 1584.42   308.7  1588.3   311.7 1589.04   347.6 1590.59   368.4  1589.8
   372.5 1592.14   377.1 1596.03   382.8 1599.28     423 1617.03   445.4  1628.4
BR U #Mann= 3
       0      .1   269.1     .04   303.1      .1
BR D #Sta/Elev= 30
       0 1672.93     8.1 1670.36      24 1662.88    30.2    1659    47.7 1649.41
    67.7  1640.2    91.6 1627.61   103.2  1623.1   116.5 1617.17   137.6 1609.76
   145.2 1606.42   159.5 1604.86   170.5 1601.31   209.7 1595.77   233.6 1593.46
   255.2 1592.72   257.5 1591.88   259.7 1590.38   263.9 1584.38     266 1582.97
   267.7 1581.82   272.41580.295  278.17  1580.7     291  1583.7   321.4 1586.15
   355.8 1589.74   382.6 1589.03   390.3 1595.39   397.1 1599.53   452.5 1630.13
BR D #Mann= 3
       0      .1     266     .04     291      .1
BC Design=,, 0 ,, 0 ,,,,,,
BC Use User HTab Curves=0
BC User HTab FreeFlow(D)= 0

Type RM Length L Ch R = 1 ,13200   ,138.5,131.4,123.9
XS GIS Cut Line= 4
1988724.08466838246840.9753064221988646.33541393246787.739320173
1988390.79383048246634.1227855661988330.93022619246628.870623468
#Sta/Elev= 30
       0 1672.93     8.1 1670.36      24 1662.88    30.2    1659    47.7 1649.41
    67.7  1640.2    91.6 1627.61   103.2  1623.1   116.5 1617.17   137.6 1609.76
   145.2 1606.42   159.5 1604.86   170.5 1601.31   209.7 1595.77   233.6 1593.46
   255.2 1592.72   257.5 1591.88   259.7 1590.38   263.9 1584.38     266 1582.97
   267.7 1581.82   272.41580.295  278.17  1580.7     291  1583.7   321.4 1586.15
   355.8 1589.74   382.6 1589.03   390.3 1595.39   397.1 1599.53   452.5 1630.13
#Mann= 3 , 0 , 0
       0      .1       0     266    .045       0     291      .1       0
#XS Ineff= 2 , 0
        255.8333 1590.24302.1667         1590.06
Permanent Ineff=
       F       F
#Block Obstruct= 2 ,-1
  171.25  205.87  1621.2  231.55  263.02 1613.65
Bank Sta=266,291
XS Rating Curve= 0 ,0
Exp/Cntr(USF)=0,0
Exp/Cntr=0.5,0.3

Type RM Length L Ch R = 1 ,13069   ,159.7,173.4,173.9
XS GIS Cut Line= 4
     1988807.321       246667.41     1988605.932      246589.285
     1988373.293       246551.09     1988262.182      246561.507
#Sta/Elev= 30
       0 1664.66     4.9  1664.6    15.5 1662.94      26 1659.82   103.2 1619.14
   124.6 1609.32   133.6  1605.3   143.8 1598.32   156.4 1595.87     196 1595.43
     246 1592.31   281.8 1591.25   325.8 1590.19   335.8 1583.87   343.71580.161
   345.7 1579.23   349.1 1578.96   366.61580.632   372.3 1581.34   398.9 1581.23
   402.3 1582.33   412.2  1588.4   415.6 1589.09   435.5 1589.79   448.7  1591.8
   455.6 1593.64   467.6 1598.23   488.7  1603.1   524.6 1604.49   563.4 1604.34
#Mann= 5 ,-1 , 0
       0      .1       0   124.6     .04       0   281.8      .1       0
   343.7    .045       0   366.6      .1       0
#Block Obstruct= 2 ,-1
  154.49  203.44 1616.16  473.96  521.71 1624.28
Bank Sta=343.7,366.6
XS Rating Curve= 0 ,0
Exp/Cntr=0.3,0.1

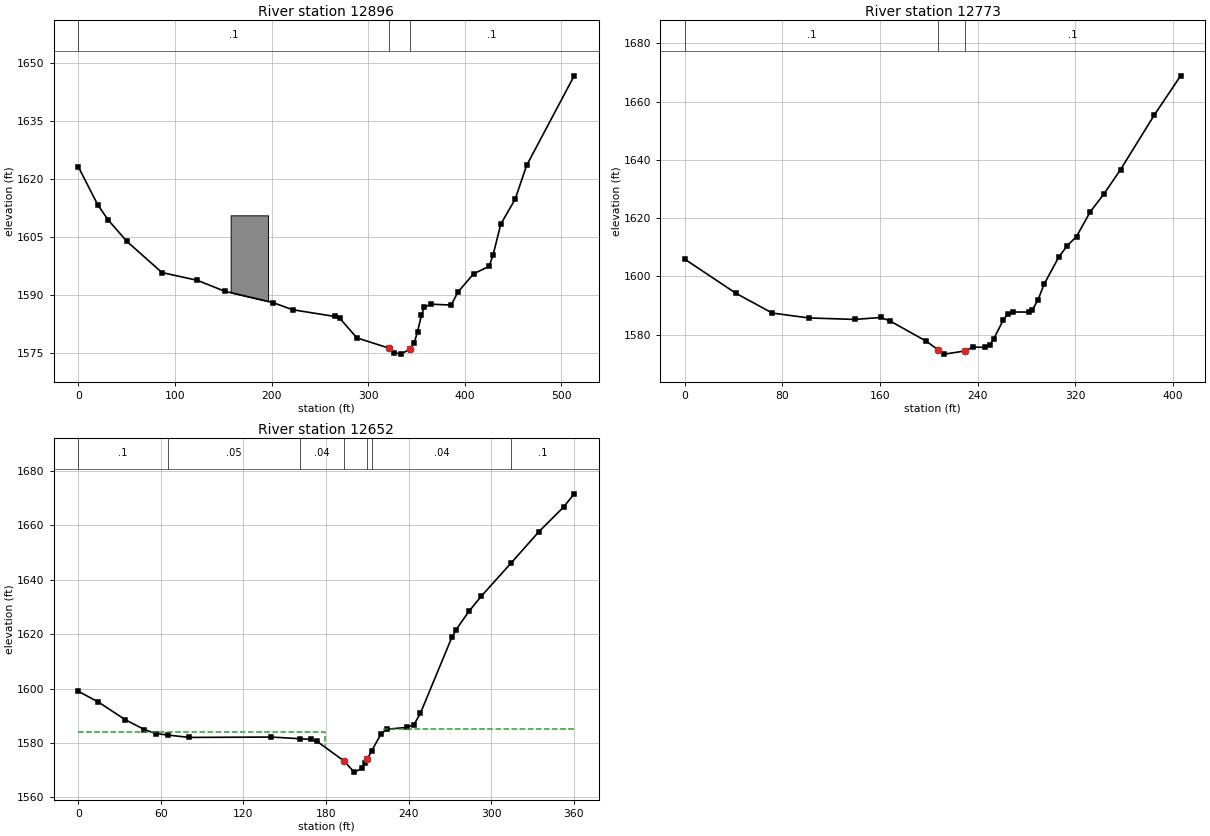
Type RM Length L Ch R = 1 ,12896   ,115.9,122.7,125.1
XS GIS Cut Line= 3
     1988748.293      246545.882     1988571.209      246453.868
     1988276.071      246347.965
#Sta/Elev= 30
       0 1623.13      20 1613.37    30.8 1609.45    50.3 1603.89    86.5 1595.87
   123.3 1593.85   151.3 1591.06   201.2 1588.14   221.7 1586.28   265.4 1584.54
   270.8 1584.02   288.2 1579.03   321.51576.366   326.9 1575.23   333.5 1574.83
   343.31576.106   347.5 1577.68     351  1580.6   355.1 1584.92   357.9 1586.89
   364.9 1587.71   385.8 1587.48   392.8 1590.83     409 1595.54   425.1 1597.48
   429.1 1600.32   437.2 1608.37     452 1614.75   463.9 1623.48   513.1 1646.59
#Mann= 3 ,-1 , 0
       0      .1       0   321.5    .045       0   343.3      .1       0
#Block Obstruct= 1 ,-1
  157.62  196.28 1610.62
Bank Sta=321.5,343.3
XS Rating Curve= 0 ,0
Exp/Cntr=0.3,0.1

Type RM Length L Ch R = 1 ,12773   ,119.1,120.9,121.5
XS GIS Cut Line= 3
     1988711.834      246413.937     1988460.098      246280.257
     1988354.196      246221.229
#Sta/Elev= 30
       0 1605.87      42 1594.13    71.7 1587.37   101.4  1585.7   139.1 1585.18
   160.8 1585.85   168.3 1584.62     198 1577.67   207.71574.689   212.8 1573.26
   229.31574.327   236.2 1575.68   246.3 1575.59     250 1576.42   253.2 1578.55
   261.1 1585.08   264.8 1587.15   268.6 1587.74   282.3  1587.7   284.7 1588.39
   289.5 1591.92   294.3 1597.18   306.4 1606.57   313.4 1610.51     321 1613.66
   332.2 1622.12   343.5 1628.31   357.1 1636.67   384.8 1655.45   406.3 1668.86
#Mann= 3 ,-1 , 0
       0      .1       0   207.7    .045       0   229.3      .1       0
Bank Sta=207.7,229.3
XS Rating Curve= 0 ,0
Exp/Cntr=0.5,0.3

Type RM Length L Ch R = 1 ,12652   ,34.1,34.2,33.9
XS GIS Cut Line= 4
     1988713.294      246334.841      1988577.66      246212.228
     1988544.023      246188.357     1988432.261      246110.232
#Sta/Elev= 30
       0 1598.99    14.4 1595.12    34.2 1588.54      48 1584.95    56.3 1583.48
    65.2 1582.92    80.5 1582.06   140.4 1582.19   161.1 1581.59   168.8 1581.33
   173.5  1580.6   193.1  1573.4   200.5  1569.3  206.55 1570.72   208.3 1572.81
     2101574.099   213.3 1577.19     220 1583.33   224.1 1585.05   239.2 1585.76
     244 1586.77   248.7    1591   271.5 1618.84   274.6 1621.68     284 1628.44
   292.7 1633.86   314.6 1646.17   334.5 1657.53   352.8 1666.77   360.4 1671.59
#Mann= 7 ,-1 , 0
       0      .1       0    65.2     .05       0   161.1     .04       0
   193.1    .045       0     210     .04       0   213.3     .04       0
   314.6      .1       0
#XS Ineff= 2 , 0
           179.5 1584.14   222.5         1585.22
Permanent Ineff=
       F       F
Bank Sta=193.1,210
XS Rating Curve= 0 ,0
Exp/Cntr=0.5,0.3