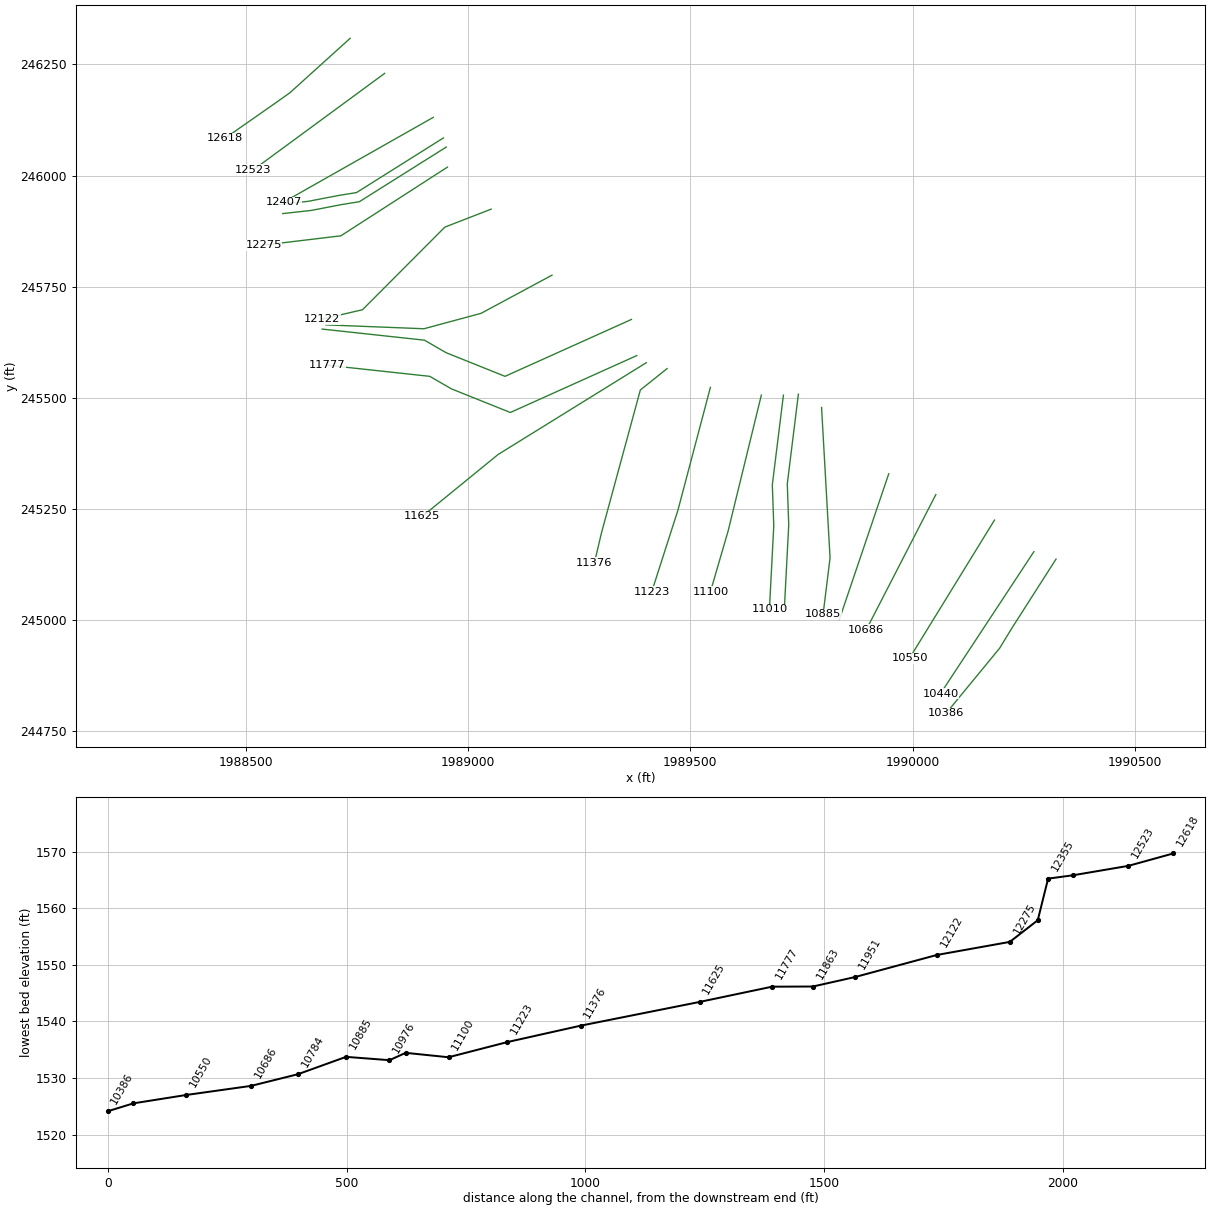
HEC-RAS study MADAMCK.prj: MADAMCK

--- MADAMCK.g01 (geometry) --- (continued)

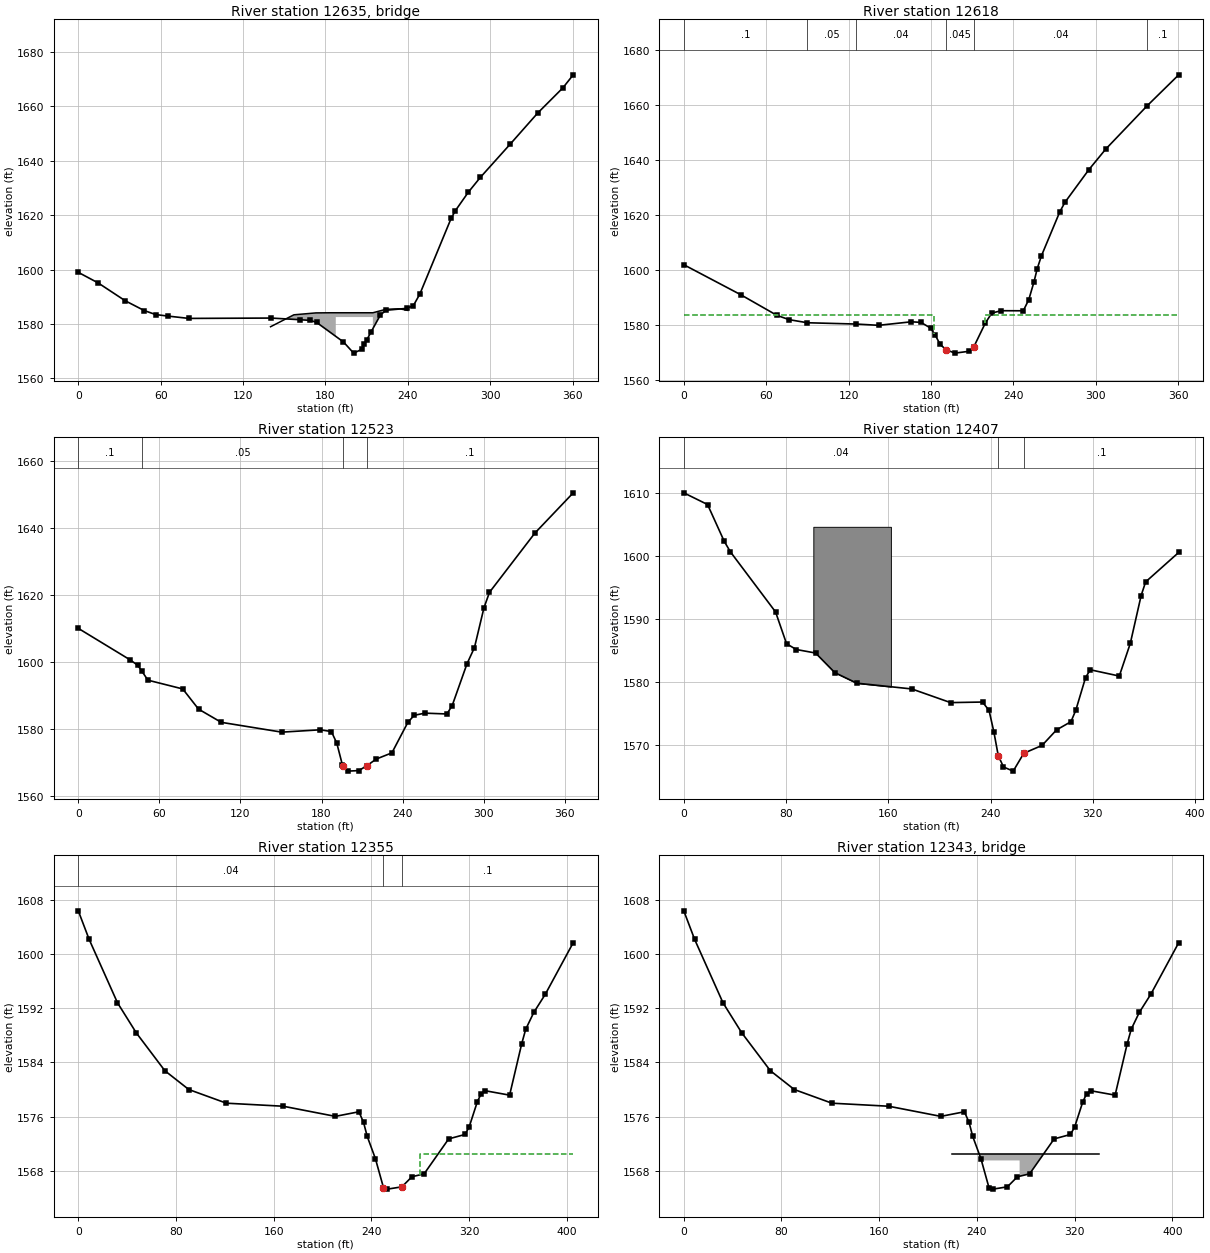
Type RM Length L Ch R = 3 ,12635   ,,,
BEGIN DESCRIPTION:
Unnamed Road
Survey ID: MAC160
END DESCRIPTION:
Bridge Culvert--1,0,-1,-1, 0
Deck Dist Width WeirC Skew NumUp NumDn MinLoCord MaxHiCord MaxSubmerge Is_Ogee
8,10,2.6,0, 13, 13, , , 0.98, 0, 0,0,,
     140     157     173     184   187.5   187.5     200     212   214.5   214.5
     224     234     240
    15791583.3881584.0871584.1391584.1391584.1391584.1391584.1391584.1391584.139
1585.4071585.598    1585
                                        1582.5561582.5561582.5561582.556
                        
     140     157     173     184   187.5   187.5     200     212   214.5   214.5
     224     234     240
    15791583.3881584.0871584.1391584.1391584.1391584.1391584.1391584.1391584.139
1585.4071585.598    1585
                                        1582.5561582.5561582.5561582.556
                        
BR Coef=-1 , 1 , 0 ,, 0 ,,,0.8,0,1.2,0,
WSPro=,,,, 1 ,,,, 0 ,,,, 0 ,,,,-1 ,-1 ,-1 , 0 , 0 , 0 , 0 , 0
BR U #Sta/Elev= 30
       0 1598.99    14.4 1595.12    34.2 1588.54      48 1584.95    56.3 1583.48
    65.2 1582.92    80.5 1582.06   140.4 1582.19   161.1 1581.59   168.8 1581.33
   173.5  1580.6   193.1  1573.4   200.5  1569.3  206.55 1570.72   208.3 1572.81
     2101574.099   213.3 1577.19     220 1583.33   224.1 1585.05   239.2 1585.76
     244 1586.77   248.7    1591   271.5 1618.84   274.6 1621.68     284 1628.44
   292.7 1633.86   314.6 1646.17   334.5 1657.53   352.8 1666.77   360.4 1671.59
BR U #Mann= 7
       0      .1    65.2     .05   161.1     .04   193.1     .04     210     .04
   213.3     .04   314.6      .1
BR D #Sta/Elev= 30
       0 1601.89    41.4 1590.99    67.9 1583.44    76.8 1581.89      90 1580.77
   125.4  1580.3   141.9 1579.84   165.7 1581.12   172.7 1580.91   179.7 1578.83
   182.9 1576.46   186.7 1572.87     1911570.986  197.36 1569.72   207.9  1570.4
     2111571.814   219.6 1580.68   224.3  1584.3   231.1 1585.15   247.2 1585.13
   251.2 1589.15     255 1595.63   257.3 1600.34   260.4  1605.1   273.8 1621.13
   277.6 1624.63     295 1636.49   307.2 1643.92   337.4  1659.7   360.4 1670.97
BR D #Mann= 6
       0      .1      90     .05   125.4     .04     191     .04     211     .04
   337.4      .1
BC Design=,, 0 ,, 0 ,,,,,,
BC Use User HTab Curves=0
BC User HTab FreeFlow(D)= 0

Type RM Length L Ch R = 1 ,12618   ,93,94.3,93.8
XS GIS Cut Line= 4
     1988734.995        246308.8     1988599.361      246186.187
     1988565.724      246162.315     1988453.962       246084.19
#Sta/Elev= 30
       0 1601.89    41.4 1590.99    67.9 1583.44    76.8 1581.89      90 1580.77
   125.4  1580.3   141.9 1579.84   165.7 1581.12   172.7 1580.91   179.7 1578.83
   182.9 1576.46   186.7 1572.87     1911570.986  197.36 1569.72   207.9  1570.4
     2111571.814   219.6 1580.68   224.3  1584.3   231.1 1585.15   247.2 1585.13
   251.2 1589.15     255 1595.63   257.3 1600.34   260.4  1605.1   273.8 1621.13
   277.6 1624.63     295 1636.49   307.2 1643.92   337.4  1659.7   360.4 1670.97
#Mann= 6 ,-1 , 0
       0      .1       0      90     .05       0   125.4     .04       0
     191    .045       0     211     .04       0   337.4      .1       0
#XS Ineff= 2 , 0
           182.5 1583.62   219.5         1583.62
Permanent Ineff=
       F       F
Bank Sta=191,211
XS Rating Curve= 0 ,0
Exp/Cntr=0.5,0.3

Type RM Length L Ch R = 1 ,12523   ,117.4,116.3,114.3
XS GIS Cut Line= 2
     1988812.529       246229.91      1988517.39      246012.896
#Sta/Elev= 30
       0 1610.12    38.5 1600.68      44  1599.1    46.8  1597.5    51.5 1594.66
    77.3 1592.04      89 1586.02   105.8 1582.08   150.6 1579.15   179.1 1579.85
   187.3 1579.33   191.3 1575.89   195.4 1569.47   196.2 1568.91   199.5 1567.52
   207.6 1567.68   213.7 1569.17   220.5 1571.12   232.1 1572.97   243.9 1582.06
   248.6 1584.17   256.5 1584.82   272.8 1584.57   276.7 1587.06   287.7 1599.57
   293.2 1604.38   300.2 1616.21   304.3 1620.86   337.9 1638.53   366.3 1650.55
#Mann= 4 ,-1 , 0
       0      .1       0    46.8     .05       0   196.2    .045       0
   213.7      .1       0
Bank Sta=196.2,213.7
XS Rating Curve= 0 ,0
Exp/Cntr=0.3,0.1

Type RM Length L Ch R = 1 ,12407   ,57.2,51.9,47.8
XS GIS Cut Line= 2
     1988921.904      246130.951     1988585.099      245939.979
#Sta/Elev= 30
       0 1610.08    18.6 1608.22    31.6 1602.39    36.4 1600.72    71.8 1591.15
    80.4 1586.09      88 1585.18   103.1 1584.62   118.1 1581.51   135.3 1579.83
   178.4 1578.91   208.7 1576.74   233.7 1576.83   238.8  1575.5   242.6 1572.07
     2461568.323   250.1 1566.51   257.7 1565.85     266 1568.69   280.3 1569.94
   291.6  1572.4   302.9 1573.71   306.7 1575.54   314.3 1580.71     318 1581.96
   340.7 1580.96   349.3 1586.14   357.8 1593.76   361.3 1595.92   387.2 1600.61
#Mann= 3 ,-1 , 0
       0     .04       0     246    .045       0     266      .1       0
#Block Obstruct= 1 ,-1
  101.34  162.02 1604.68
Bank Sta=246,266
XS Rating Curve= 0 ,0
Exp/Cntr=0.5,0.3

Type RM Length L Ch R = 1 ,12355   ,22,21.7,22.2
XS GIS Cut Line= 5
1988944.76493223246084.6660988181988749.36073797245961.721818542
1988708.97324493 245955.188547611988641.26480072245942.122005745
1988577.11995884245934.994801091
#Sta/Elev= 30
       0 1606.42     8.9 1602.19    32.1 1592.82    47.5 1588.37    70.9 1582.77
    90.5 1579.99   121.3 1577.97   167.8 1577.52   210.5 1576.02   229.8  1576.7
   233.6 1575.13   236.6 1573.06   243.3 1569.77   249.9 1565.49   253.2 1565.26
     265  1565.6   273.2 1567.09   283.2 1567.52   303.3 1572.69   316.6 1573.34
     320 1574.41   326.8  1578.2     330  1579.4   333.3 1579.81   353.2 1579.16
   363.1 1586.76   366.4 1588.91     373 1591.39   382.4 1594.07   405.3 1601.71
#Mann= 3 , 0 , 0
       0     .04       0   249.9    .045       0     265      .1       0
#XS Ineff= 2 , 0
             240  1570.5     280          1570.5
Permanent Ineff=
       F       F
Bank Sta=249.9,265
XS Rating Curve= 0 ,0
Exp/Cntr(USF)=0,0
Exp/Cntr=0.5,0.3

Type RM Length L Ch R = 3 ,12343   ,,,
BEGIN DESCRIPTION:
Unnamed Road
END DESCRIPTION:
Bridge Culvert--1,0,-1,-1, 0
Deck Dist Width WeirC Skew NumUp NumDn MinLoCord MaxHiCord MaxSubmerge Is_Ogee
5,16,2.6,0, 5, 5, , , 0.98, 0, 0,0,,
     220     245     275     275     340
  1570.5  1570.5  1570.5  1570.5  1570.5
          1569.5  1569.5
     220     245     275     275     340
  1570.5  1570.5  1570.5  1570.5  1570.5
          1569.5  1569.5
BR Coef=-1 , 0 , 0 ,, 0 ,,,0.8,-1,,0,
WSPro=,,,, 1 ,,,, 0 ,,,, 0 ,,,,-1 ,-1 ,-1 , 0 , 0 , 0 , 0 , 0
BR U #Sta/Elev= 30
       0 1606.42     8.9 1602.19    32.1 1592.82    47.5 1588.37    70.9 1582.77
    90.5 1579.99   121.3 1577.97   167.8 1577.52   210.5 1576.02   229.8  1576.7
   233.6 1575.13   236.6 1573.06   243.3 1569.77   249.9 1565.49   253.2 1565.26
     265  1565.6   273.2 1567.09   283.2 1567.52   303.3 1572.69   316.6 1573.34
     320 1574.41   326.8  1578.2     330  1579.4   333.3 1579.81   353.2 1579.16
   363.1 1586.76   366.4 1588.91     373 1591.39   382.4 1594.07   405.3 1601.71
BR U #Mann= 3
       0     .04   249.9     .04     265      .1
BR D #Sta/Elev= 30
       0 1602.56    43.5 1586.55      58  1583.7    70.3 1580.49   119.6 1577.52
   194.7 1575.83     218 1576.66   224.3 1575.95   229.9 1573.71   238.3 1564.41
   243.1 1561.62   246.4 1562.21   247.5 1561.59   249.7 1560.05   259.7  1560.3
     263 1558.74   266.9  1557.9   269.8 1558.21  272.321560.198   279.7 1566.25
     283 1567.25   297.8 1569.97   313.1  1571.6   316.4 1572.39   326.4 1576.66
   333.1 1578.11   359.6  1577.6   362.9 1578.43   379.4 1585.22   405.3 1591.75
BR D #Mann= 3
       0     .04   247.5     .04  272.32      .1
BC Design=,, 0 ,, 0 ,,,,,,
BC Use User HTab Curves=0
BC User HTab FreeFlow(D)= 0

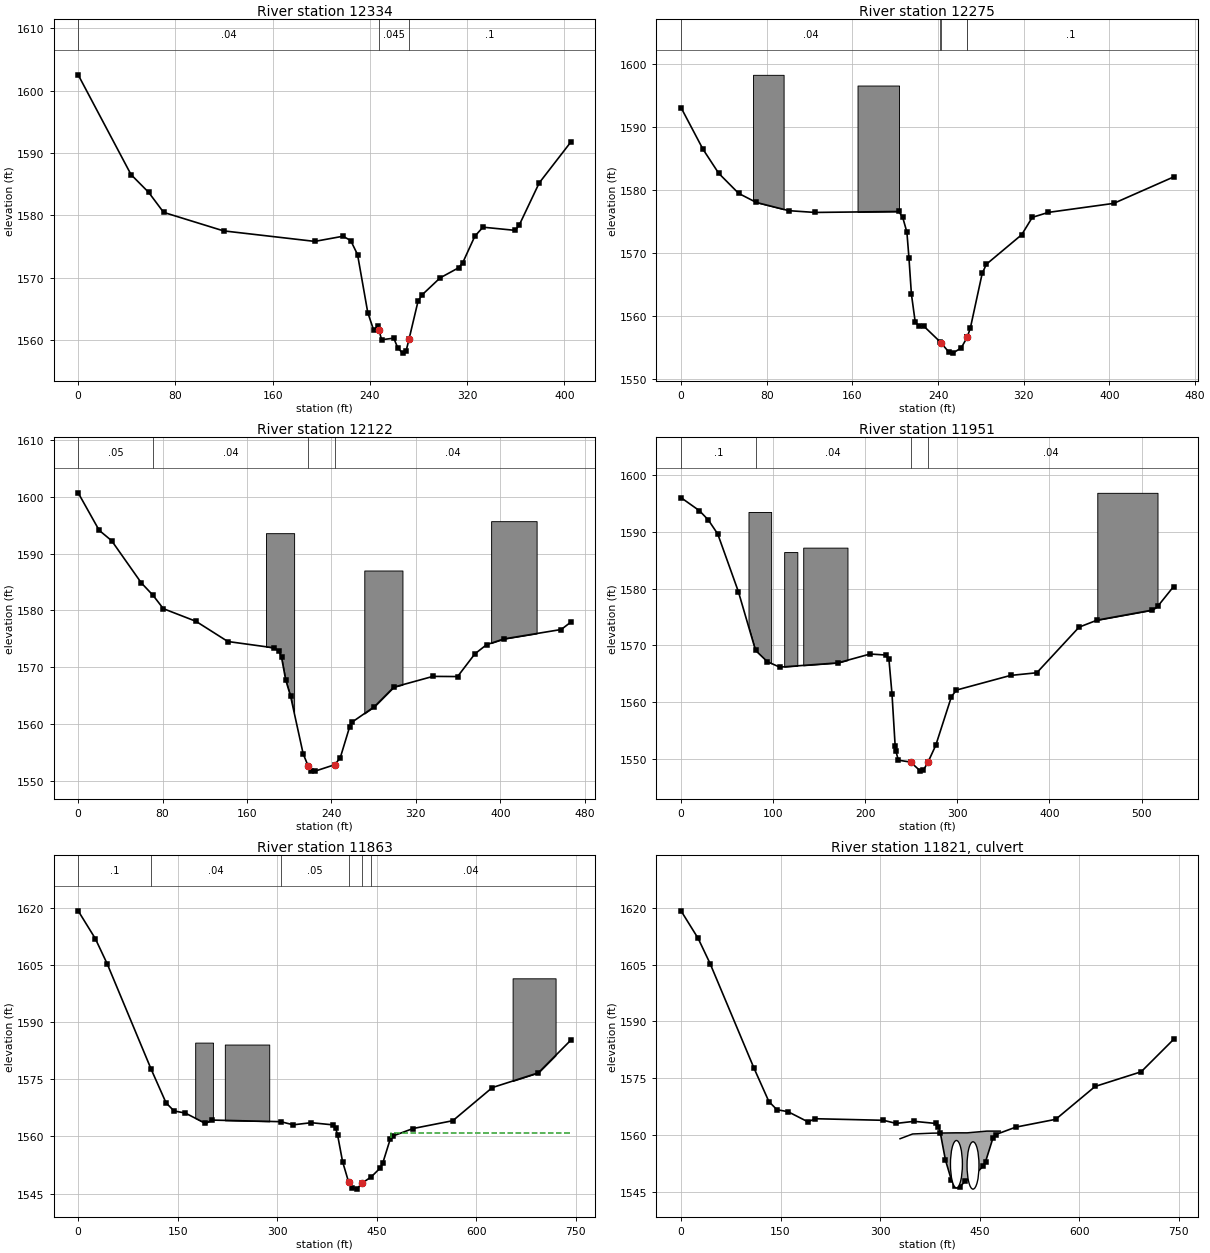
Type RM Length L Ch R = 1 ,12334   ,51.7,58.5,66.2
XS GIS Cut Line= 5
1988951.11144095246064.0765560531988755.70724669245941.132275777
1988715.31975365245934.5990048451988647.61130944 245921.53246298
1988583.46646756245914.405258326
#Sta/Elev= 30
       0 1602.56    43.5 1586.55      58  1583.7    70.3 1580.49   119.6 1577.52
   194.7 1575.83     218 1576.66   224.3 1575.95   229.9 1573.71   238.3 1564.41
   243.1 1561.62   246.4 1562.21   247.5 1561.59   249.7 1560.05   259.7  1560.3
     263 1558.74   266.9  1557.9   269.8 1558.21  272.321560.198   279.7 1566.25
     283 1567.25   297.8 1569.97   313.1  1571.6   316.4 1572.39   326.4 1576.66
   333.1 1578.11   359.6  1577.6   362.9 1578.43   379.4 1585.22   405.3 1591.75
#Mann= 3 , 0 , 0
       0     .04       0   247.5    .045       0  272.32      .1       0
#XS Ineff= 2 , 0
             240    1563     280            1563
Permanent Ineff=
       F       F
Bank Sta=247.5,272.32
XS Rating Curve= 0 ,0
Exp/Cntr(USF)=0,0
Exp/Cntr=0.5,0.3

Type RM Length L Ch R = 1 ,12275   ,150.3,152.8,158.4
Node Name=D
XS GIS Cut Line= 3
1988953.70213256246018.8811755681988714.11913256245864.367175568
1988540.50813256245843.533175568
#Sta/Elev= 30
       0 1593.11    20.5 1586.49    35.2 1582.66    53.8 1579.47    70.3 1578.03
   100.7 1576.72     125 1576.44   203.3 1576.59     207 1575.65   210.9  1573.3
   212.8 1569.26   215.1 1563.48   218.7 1558.97   222.6 1558.35   226.5 1558.39
   242.1 1555.84   242.51555.748   249.9 1554.28   253.8 1554.07   261.6  1554.9
   267.11556.556   267.4  1556.7   270.2 1558.09   281.2 1566.74   285.1  1568.2
   318.1  1572.9     328 1575.66   343.1 1576.45     404 1577.88   459.9 1582.08
#Mann= 5 ,-1 , 0
       0     .04       0   242.1     .04       0   242.5    .045       0
   267.1      .1       0   267.4      .1       0
#Block Obstruct= 2 ,-1
   67.25   95.78 1598.32   164.8  203.56 1596.62
Bank Sta=242.5,267.1
XS Rating Curve= 0 ,0
Exp/Cntr=0.3,0.1

Type RM Length L Ch R = 1 ,12122   ,178.1,171.6,162.2
XS GIS Cut Line= 4
1989052.08390953245924.4004615531988948.06318995 245884.01648376
1988762.78161088245698.037755674 1988672.5791629245677.117289594
#Sta/Elev= 30
       0 1600.67    19.9 1594.08    31.7 1592.26    59.8 1584.85      71 1582.64
    80.7 1580.31   111.6 1578.09   141.8 1574.54   185.4 1573.43   190.1  1572.9
   192.7 1571.74   196.6 1567.82   201.3  1564.9   213.2  1554.8   217.9 1552.67
   220.5 1551.84   224.5 1551.76   243.1 1552.89   248.3 1554.09   257.3 1559.59
   259.6 1560.38   280.7 1563.09   299.1 1566.52   336.2 1568.41   359.5 1568.38
   375.9 1572.37     387 1573.98   403.3 1574.99   457.7 1576.65   466.7 1577.93
#Mann= 4 ,-1 , 0
       0     .05       0      71     .04       0   217.9    .045       0
   243.1     .04       0
#Block Obstruct= 3 ,-1
  177.94  204.62 1593.58  271.11  307.27 1587.02  391.28  434.39 1595.69
Bank Sta=217.9,243.1
XS Rating Curve= 0 ,0
Exp/Cntr=0.3,0.1

Type RM Length L Ch R = 1 ,11951   ,97.1,88.1,75.8
XS GIS Cut Line= 4
1989188.93224439245775.810628984     1989029.543      245689.979
     1988901.071      245655.257     1988680.585      245663.938
#Sta/Elev= 30
       0    1596      20  1593.7    29.7 1592.06    39.9 1589.59    62.3 1579.44
    80.9 1569.11    93.7 1567.12   107.2 1566.16   170.4 1566.91   205.3 1568.47
   222.3 1568.29   225.7 1567.63   229.1 1561.36   232.5 1552.28   233.2 1551.46
   235.9 1549.78   249.3 1549.44     260 1547.85   263.1 1548.02     268 1549.37
   276.6  1552.4   293.6 1560.96     299 1562.12   357.8  1564.7   386.3 1565.17
   432.2  1573.2   451.9 1574.44   511.6  1576.2   517.6 1576.87   534.8 1580.34
#Mann= 4 ,-1 , 0
       0      .1       0    80.9     .04       0   249.3    .045       0
     268     .04       0
#Block Obstruct= 4 ,-1
   73.25   97.84 1593.48  111.99  126.28 1586.42  132.67  180.73  1587.2
  451.97  517.36 1596.85
Bank Sta=249.3,268
XS Rating Curve= 0 ,0
Exp/Cntr=0.5,0.3

Type RM Length L Ch R = 1 ,11863   ,88.4,85.4,87.1
XS GIS Cut Line= 5
     1989367.591      245676.204     1989083.302      245548.166
     1988950.924      245601.334     1988902.096      245629.546
     1988672.061      245654.503
#Sta/Elev= 30
       0 1619.17    25.8 1611.89    43.8 1605.25     110 1577.62   132.4 1568.82
   144.5 1566.67   161.2 1566.15   191.3 1563.46   202.1 1564.29   305.1 1563.87
   324.2 1563.05   351.2  1563.6   384.3 1563.03   387.9 1562.21   390.9 1560.39
   398.4 1553.41   407.51548.047   412.6  1546.5   419.7 1546.18   428.1  1547.8
   441.4 1549.36   455.1  1551.7   458.9 1552.97   470.3 1559.33     474 1560.09
   504.5 1562.07   564.6 1564.13     624 1572.81   693.4 1576.68   742.2 1585.22
#Mann= 6 ,-1 , 0
       0      .1       0     110     .04       0   305.1     .05       0
   407.5    .045       0   428.1     .04       0   441.4     .04       0
#XS Ineff= 2 , 0
             382 1560.51     472         1561.02
Permanent Ineff=
       F       F
#Block Obstruct= 3 ,-1
  176.33  203.03 1584.61     221   287.9  1584.1  654.63   719.4 1601.47
Bank Sta=407.5,428.1
XS Rating Curve= 0 ,0
Exp/Cntr=0.5,0.3

Type RM Length L Ch R = 2 ,11821   ,,,
BEGIN DESCRIPTION:
Madams Creek Road
Survey ID: MAC150
END DESCRIPTION:
Bridge Culvert--1,0,-1,-1, 0
Deck Dist Width WeirC Skew NumUp NumDn MinLoCord MaxHiCord MaxSubmerge Is_Ogee
24,30,2.6,0, 7, 7, , , 0.98, 0, 0,0,,
     330     349     379     415     431     461     481
    15591560.2611560.4791560.5621560.5591561.0221561.022
                                                        
     330     349     379     415     431     461     481
    15591560.2611560.4791560.5621560.5591561.0221561.022
                                                        
BR Coef=-1 , 1 , 0 ,, 0 ,,,0.8,0,1.2,0,
WSPro=,,,, 1 ,,,, 0 ,,,, 0 ,,,,-1 ,-1 ,-1 , 0 , 0 , 0 , 0 , 0
Culvert=5,12.5,18,50,0.019,0.7,1,41,2,1546.039,415,1545.826,406,Culvert #1  , 0 ,14
     415     406
BC Culvert Barrel=1,Barrel1,0
Culvert Bottom n=0.019
Culvert=5,12.5,18,50,0.019,0.7,1,41,2,1545.702,440,1546.15,431,Culvert #2  , 0 ,14
     440     431
BC Culvert Barrel=1,Barrel1,0
Culvert Bottom n=0.019
BC Design=,, 0 ,, 0 ,,,,,,
BC Use User HTab Curves=0
BC User HTab FreeFlow(D)= 0

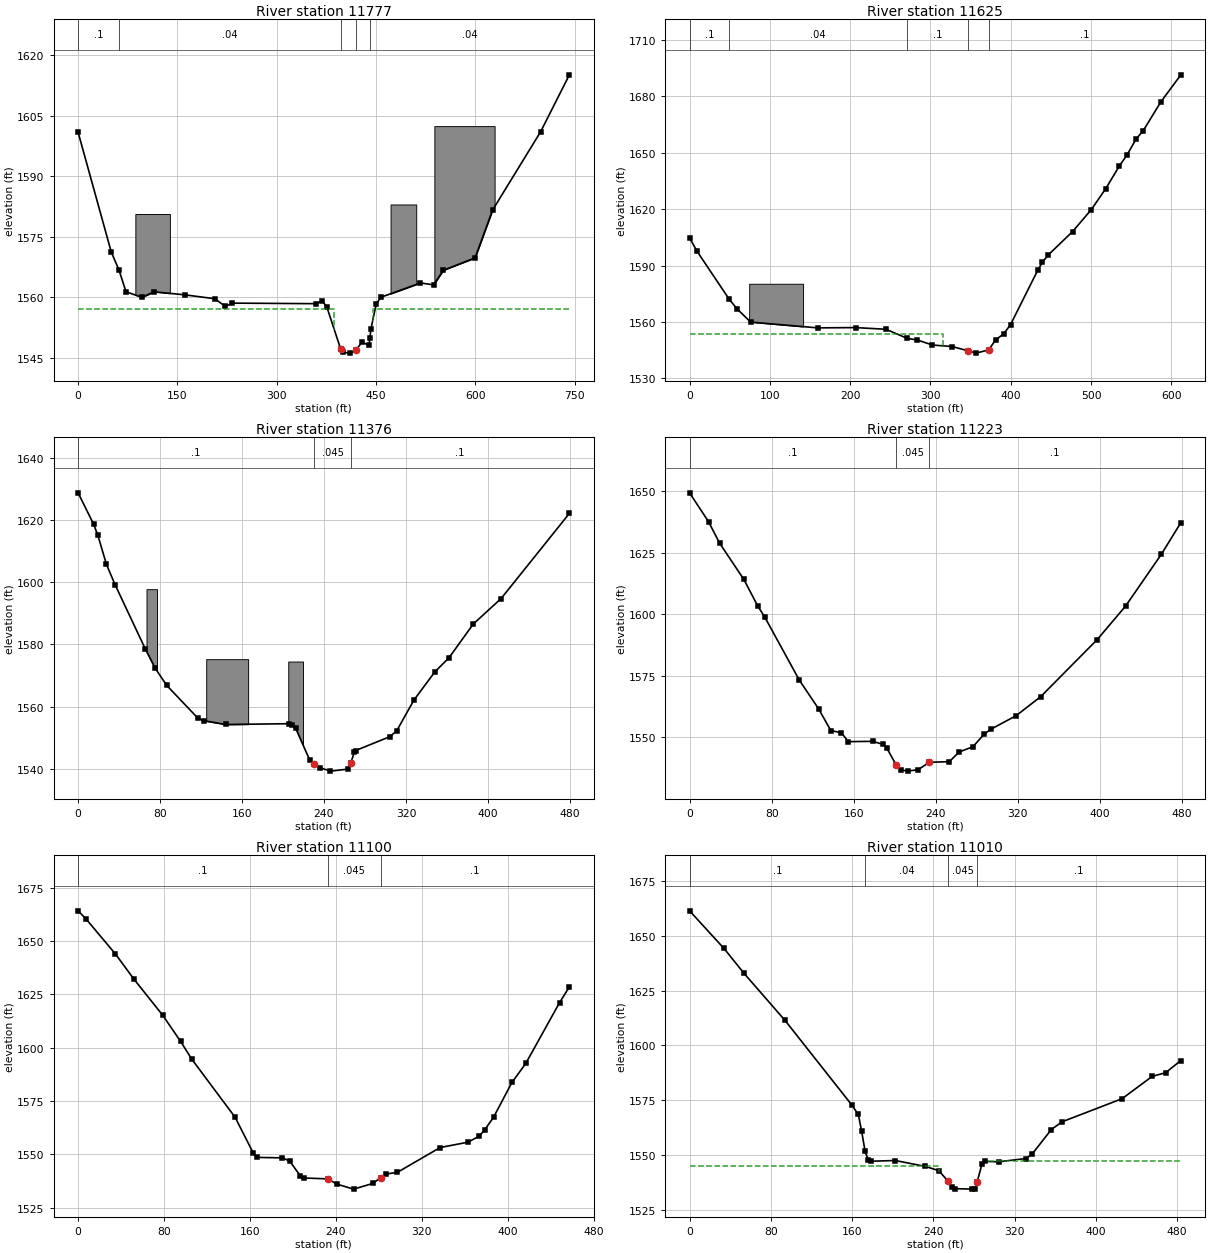
Type RM Length L Ch R = 1 ,11777   ,137.8,151.9,165
XS GIS Cut Line= 5
     1989379.526      245594.824     1989095.238      245466.786
      1988962.86      245519.954     1988914.032      245548.166
     1988683.997      245573.122
#Sta/Elev= 30
       0 1600.87    50.1 1571.19    61.7 1566.76    72.4 1561.34    96.5 1559.99
   114.9 1561.35   161.2 1560.59   206.4 1559.63   222.4 1557.74   233.2 1558.54
   359.2  1558.4   368.9 1559.11     376 1557.48   396.7 1547.14   400.7 1546.34
   411.3 1546.15   419.8 1546.93     429 1548.86   439.6 1548.06   440.7 1549.82
   442.5 1552.18   450.2 1558.22   457.3 1559.98   517.2 1563.54     537 1563.06
   551.8 1566.69   599.7 1569.75   626.1 1581.57   698.7 1600.98   742.2  1615.1
#Mann= 5 ,-1 , 0
       0      .1       0    61.7     .04       0   396.7    .045       0
   419.8     .04       0   440.7     .04       0
#XS Ineff= 2 , 0
             387    1557     445            1557
Permanent Ineff=
       F       F
#Block Obstruct= 3 ,-1
   86.49  138.63 1580.63  472.03  510.84 1582.98  538.21  629.25 1602.39
Bank Sta=396.7,419.8
XS Rating Curve= 0 ,0
Exp/Cntr=0.5,0.3

Type RM Length L Ch R = 1 ,11625   ,237.5,249.3,263.4
XS GIS Cut Line= 3
     1989401.071      245578.868     1989067.737      245372.271
     1988897.599      245233.382
#Sta/Elev= 30
       0 1604.73     9.3 1597.61    49.4 1572.07    59.3 1566.91      76 1559.98
   159.4 1556.89   207.1 1557.03   244.6 1556.13     271  1551.3   283.3 1550.48
   302.5 1547.75     327 1546.96   346.41544.704   356.6 1543.45   372.61545.172
     381 1550.48   391.3 1553.72   399.7 1558.64   433.6 1587.57   439.5 1591.85
   446.5  1595.6   476.9 1608.08   500.2 1619.73   518.3 1630.97   535.1 1642.91
   544.5 1648.67   556.1 1657.35   564.9 1661.74   586.9 1677.07   611.8 1691.47
#Mann= 5 ,-1 , 0
       0      .1       0    49.4     .04       0     271      .1       0
   346.4    .045       0   372.6      .1       0
#XS Ineff= 2 , 0
          315.89 1553.67
Permanent Ineff=
       F       F
#Block Obstruct= 1 ,-1
   74.21  141.35 1580.35
Bank Sta=346.4,372.6
XS Rating Curve= 0 ,0
Exp/Cntr=0.3,0.1

Type RM Length L Ch R = 1 ,11376   ,152.1,153,153.6
XS GIS Cut Line= 4
1989447.73311109245565.553346661 1989387.6218081245517.441557232
1989300.19203112245195.8386267581989284.30478215245128.414804408
#Sta/Elev= 30
       0 1628.76    15.1 1618.69    19.3 1615.08    27.7 1605.71    36.1 1599.21
    65.5 1578.61    74.8 1572.57    86.5 1566.82   117.1 1556.22   122.6 1555.48
   144.3 1554.25   205.5  1554.5   208.9  1554.1   212.3 1553.06   225.9 1542.93
   230.5 1541.57   236.1 1540.37   246.3 1539.25   263.3  1539.9   266.2 1541.91
   269.6 1545.36   270.8 1545.86   304.1 1550.31   310.9 1552.18   327.9 1562.17
   348.3 1571.21   361.9 1575.66   385.7 1586.56   412.9 1594.77   479.5 1622.14
#Mann= 3 , 0 , 0
       0      .1       0   230.5    .045       0   266.2      .1       0
#Block Obstruct= 3 ,-1
   66.75   76.99 1597.77  125.04  165.95 1575.26  205.12  219.51  1574.5
Bank Sta=230.5,266.2
XS Rating Curve= 0 ,0
Exp/Cntr=0.3,0.1

Type RM Length L Ch R = 1 ,11223   ,119.7,123.4,123.7
XS GIS Cut Line= 3
     1989545.168      245523.312     1989472.251      245247.271
     1989413.224      245063.243
#Sta/Elev= 30
       0 1649.22    18.5 1637.49    29.2 1628.86    52.9 1614.09    66.4 1603.34
    73.2 1598.89     107 1573.23   125.8 1561.58   137.7 1552.79   147.9 1551.96
   154.7 1548.31   178.4 1548.45   188.6  1547.2     192 1545.86   201.21539.002
   205.6 1536.93   212.4 1536.36   222.7 1536.94   233.61539.941   253.1  1540.2
   262.7 1544.11   276.2 1546.27     287 1551.31   293.9 1553.41   318.2 1558.83
   342.2 1566.56   397.3 1589.72   424.9 1603.27   459.9 1624.36   478.8 1637.12
#Mann= 3 ,-1 , 0
       0      .1       0   201.2    .045       0   233.6      .1       0
Bank Sta=201.2,233.6
XS Rating Curve= 0 ,0
Exp/Cntr=0.3,0.1

Type RM Length L Ch R = 1 ,11100   ,82.4,89.8,97.2
XS GIS Cut Line= 3
     1989659.751      245505.951     1989585.098      245200.396
     1989545.168      245063.243
#Sta/Elev= 30
       0 1664.24     7.7 1660.22    34.8 1643.97    51.6 1632.43    78.7 1615.29
    95.5 1602.95   105.7 1594.73   146.2 1567.36   163.1 1550.59   166.5 1548.56
   190.1 1548.34   196.9  1546.9     207 1539.84   210.4  1538.9   232.61538.467
   240.8 1536.04   256.51533.671   274.5 1536.35   281.81539.097   286.3 1540.72
   297.2 1541.54   337.1 1553.19   362.9 1555.68   373.2 1558.44   378.7 1561.59
   386.8  1567.4   403.9  1583.7   416.8 1592.63   448.3 1621.21   457.4 1628.56
#Mann= 3 ,-1 , 0
       0      .1       0   232.6    .045       0   281.8      .1       0
Bank Sta=232.6,281.8
XS Rating Curve= 0 ,0
Exp/Cntr=0.5,0.3

Type RM Length L Ch R = 1 ,11010   ,34.8,33.9,34.1
XS GIS Cut Line= 4
     1989709.387      245505.848     1989684.431      245304.025
     1989687.686      245211.794      1989677.92      245024.077
#Sta/Elev= 30
       0 1661.34    33.9 1644.17    53.7 1632.78      94 1611.35   159.5 1572.92
   166.1  1568.5   169.4 1560.79   172.8 1551.61   176.1 1547.61   178.3 1547.16
   202.5  1547.5   232.2 1544.79   245.2  1542.9   254.3 1538.16   258.3  1535.4
   261.6 1534.66     278 1534.45   281.3  1534.6   282.91537.477   287.9 1545.99
   291.2  1547.1   304.3 1546.92   331.1  1548.4   337.4 1550.54   356.1 1561.62
   366.7 1565.15   425.8  1575.7   455.4 1585.86   468.6 1587.53   483.6 1593.09
#Mann= 4 ,-1 , 0
       0      .1       0   172.8     .04       0   254.3    .045       0
   282.9      .1       0
#XS Ineff= 2 , 0
             246 1545.13     294         1547.24
Permanent Ineff=
       F       F
Bank Sta=254.3,282.9
XS Rating Curve= 0 ,0
Exp/Cntr=0.5,0.3

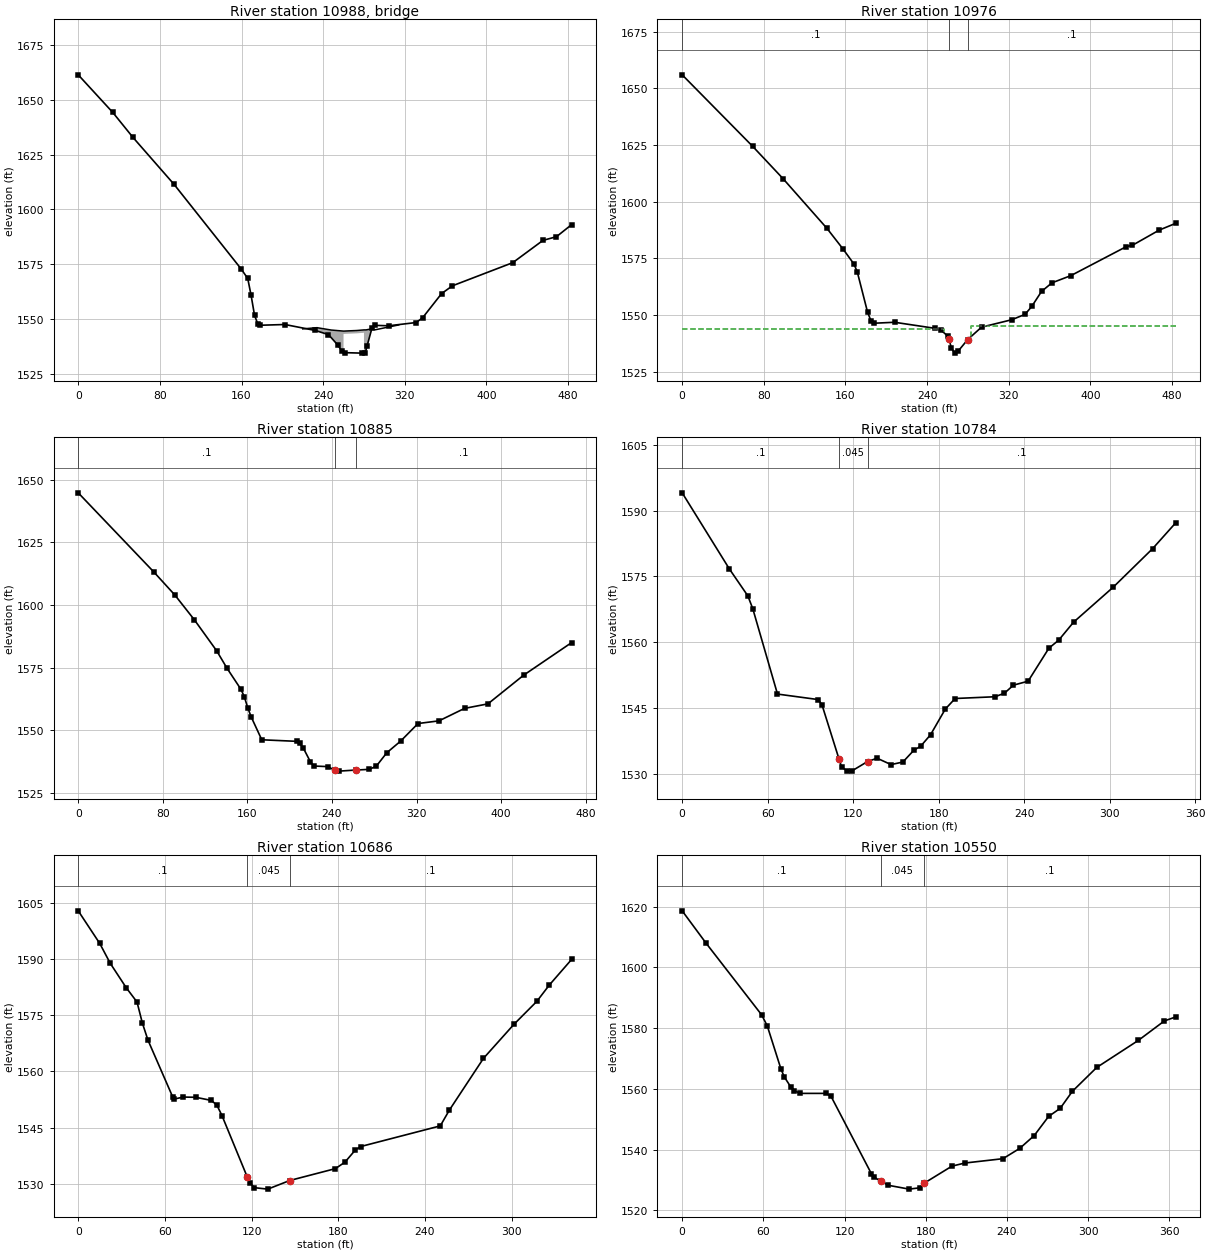
Type RM Length L Ch R = 3 ,10988   ,,,
BEGIN DESCRIPTION:
Unnamed Road
Survey ID: MAC140RP
END DESCRIPTION:
Bridge Culvert--1,0,-1,-1, 0
Deck Dist Width WeirC Skew NumUp NumDn MinLoCord MaxHiCord MaxSubmerge Is_Ogee
14,11,2.6,0, 12, 12, , , 0.98, 0, 0,0,,
     220     234     248     260     260     273     280     280     282     287
     291     314
  1545.51546.0561544.9741544.4971544.4971544.765 1545.04 1545.04 1545.041545.483
1545.0881547.304
                                  1543.2 1543.47 1543.74
                
     220     234     248     260     260     273     280     280     282     287
     291     314
  1545.51546.0561544.9741544.4971544.4971544.765 1545.04 1545.04 1545.041545.483
1545.0881547.304
                                  1543.2 1543.47 1543.74
                
BR Coef=-1 , 1 , 0 ,, 0 ,,,0.8,0,1.2,0,
WSPro=,,,, 1 ,,,, 0 ,,,, 0 ,,,,-1 ,-1 ,-1 , 0 , 0 , 0 , 0 , 0
BR U #Sta/Elev= 30
       0 1661.34    33.9 1644.17    53.7 1632.78      94 1611.35   159.5 1572.92
   166.1  1568.5   169.4 1560.79   172.8 1551.61   176.1 1547.61   178.3 1547.16
   202.5  1547.5   232.2 1544.79   245.2  1542.9   254.3 1538.16   258.3  1535.4
   261.6 1534.66     278 1534.45   281.3  1534.6   282.91537.477   287.9 1545.99
   291.2  1547.1   304.3 1546.92   331.1  1548.4   337.4 1550.54   356.1 1561.62
   366.7 1565.15   425.8  1575.7   455.4 1585.86   468.6 1587.53   483.6 1593.09
BR U #Mann= 4
       0      .1   172.8     .04   254.3     .04   282.9      .1
BR D #Sta/Elev= 30
       0 1655.97    69.2 1624.35    98.9 1610.12   141.9 1588.19   157.5 1579.17
   168.3 1572.48   171.6 1568.96   181.6 1551.34   184.9 1547.47   188.2 1546.35
   208.1 1546.77   247.4 1544.12   253.9 1543.17   260.5 1540.57   261.3 1539.55
  263.86 1535.29   267.11533.151  270.53  1534.1   279.71539.096   293.3 1544.61
   322.9 1547.88     336 1550.27   342.6 1553.79   352.1 1560.36   362.3 1564.17
   380.8 1567.34   435.3 1580.18   441.2 1580.75   467.4 1587.44   483.6 1590.43
BR D #Mann= 3
       0      .1   261.3     .04   279.7      .1
BC Design=,, 0 ,, 0 ,,,,,,
BC Use User HTab Curves=0
BC User HTab FreeFlow(D)= 0

Type RM Length L Ch R = 1 ,10976   ,89.8,90.9,91.8
XS GIS Cut Line= 4
     1989743.024      245508.019     1989718.068      245306.195
     1989721.323      245213.965     1989711.557      245026.248
#Sta/Elev= 30
       0 1655.97    69.2 1624.35    98.9 1610.12   141.9 1588.19   157.5 1579.17
   168.3 1572.48   171.6 1568.96   181.6 1551.34   184.9 1547.47   188.2 1546.35
   208.1 1546.77   247.4 1544.12   253.9 1543.17   260.5 1540.57   261.3 1539.55
  263.86 1535.29   267.11533.151  270.53  1534.1   279.71539.096   293.3 1544.61
   322.9 1547.88     336 1550.27   342.6 1553.79   352.1 1560.36   362.3 1564.17
   380.8 1567.34   435.3 1580.18   441.2 1580.75   467.4 1587.44   483.6 1590.43
#Mann= 3 , 0 , 0
       0      .1       0   261.3    .045       0   279.7      .1       0
#XS Ineff= 2 , 0
             257 1543.74     283            1545
Permanent Ineff=
       F       F
Bank Sta=261.3,279.7
XS Rating Curve= 0 ,0
Exp/Cntr=0.5,0.3

Type RM Length L Ch R = 1 ,10885   ,105.8,100.8,90.7
XS GIS Cut Line= 3
     1989795.168      245478.173     1989814.265      245139.632
      1989798.64      245012.896
#Sta/Elev= 30
       0  1644.8    71.7 1613.13    91.4 1604.02   109.9  1594.1   130.9 1581.79
   140.7 1574.82   153.9 1566.39   157.1 1563.43   160.4 1558.92   163.7 1555.28
   173.6 1546.25   206.6 1545.63   209.7 1544.78     213 1542.86   219.6 1537.47
   222.9 1535.78     236 1535.54   242.41534.142   246.7 1533.74   262.41534.169
   275.4 1534.45     282 1535.76   291.9 1541.09     305 1545.74   321.4 1552.74
   341.2  1553.8   365.4 1558.78   387.5 1560.58   421.3 1572.03   466.8 1585.07
#Mann= 3 ,-1 , 0
       0      .1       0   242.4    .045       0   262.4      .1       0
Bank Sta=242.4,262.4
XS Rating Curve= 0 ,0
Exp/Cntr=0.3,0.1

Type RM Length L Ch R = 1 ,10784   ,100,98,94.3
XS GIS Cut Line= 2
      1989946.21      245328.868     1989835.098      245000.743
#Sta/Elev= 30
       0 1594.05    33.2 1576.68    46.1 1570.58    49.6 1567.62    66.9 1548.22
    95.4 1546.97    98.1  1545.8   110.11533.404   111.9 1531.63   115.4 1530.77
   118.9 1530.67   130.11532.851   136.8 1533.61   146.6 1532.16   154.9 1532.74
   162.6 1535.42   167.4 1536.35   174.3 1538.94   184.7 1544.81   191.6 1547.21
   219.6 1547.61   226.2 1548.42   232.5 1550.25   242.8 1551.15   257.4 1558.67
   264.3 1560.51   274.7 1564.59   302.4 1572.52   330.2 1581.34   346.4 1587.22
#Mann= 3 , 0 , 0
       0      .1       0   110.1    .045       0   130.1      .1       0
Bank Sta=110.1,130.1
XS Rating Curve= 0 ,0
Exp/Cntr=0.3,0.1

Type RM Length L Ch R = 1 ,10686   ,134.8,135.8,130.7
XS GIS Cut Line= 2
     1990052.112      245281.993     1989895.862      244978.173
#Sta/Elev= 30
       0 1602.85    14.9 1594.15    22.2 1588.83    33.3  1582.3    40.7 1578.52
    44.4 1572.91    48.3 1568.33    65.4  1553.2    66.5 1552.64    72.7 1553.17
    81.3 1553.11    92.2 1552.27      96 1550.99    99.5 1548.23   117.1 1531.75
     119  1530.3   121.8    1529   131.2 1528.61   146.41530.911     178 1534.08
   184.6  1535.8   191.9 1539.09   195.6 1539.98   250.6 1545.48   256.9  1549.7
   280.5  1563.5   301.7 1572.62   317.4 1578.69   326.1 1583.07   341.6 1589.93
#Mann= 3 ,-1 , 0
       0      .1       0   117.1    .045       0   146.4      .1       0
Bank Sta=117.1,146.4
XS Rating Curve= 0 ,0
Exp/Cntr=0.3,0.1

Type RM Length L Ch R = 1 ,10550   ,109.9,110.7,109
XS GIS Cut Line= 2
     1990184.057      245224.701     1989993.085      244913.937
#Sta/Elev= 30
       0 1618.62    17.6 1608.01    58.7  1584.4    62.9 1580.74      73 1566.57
    75.4    1564    80.1 1560.76      83 1559.44    86.9 1558.52   106.4 1558.52
     110 1557.58   139.8 1532.13   142.1 1530.92   146.61529.624   152.4 1528.26
   167.8    1527   175.5 1527.43     179 1528.99   199.4 1534.57   208.9 1535.59
   237.1 1537.02   249.5 1540.41   260.2 1544.63   270.9 1550.96   279.4 1553.58
   288.4 1559.19   306.4 1567.05   337.2 1575.97   356.4 1582.37   364.8 1583.69
#Mann= 3 , 0 , 0
       0      .1       0   146.6    .045       0     179      .1       0
Bank Sta=146.6,179
XS Rating Curve= 0 ,0
Exp/Cntr=0.3,0.1

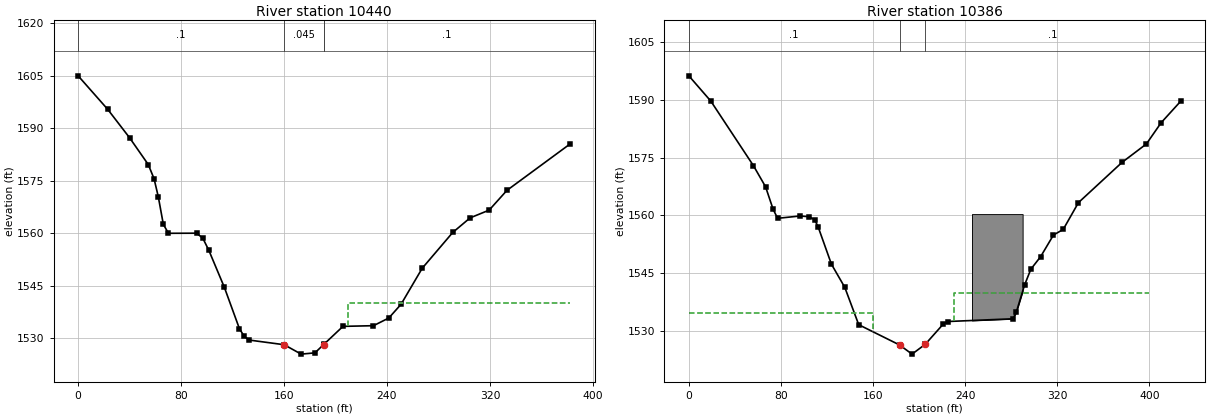
Type RM Length L Ch R = 1 ,10440   ,53.4,53.8,54.5
XS GIS Cut Line= 2
     1990272.598      245153.521     1990062.529      244834.076
#Sta/Elev= 30
       0 1604.91      23 1595.34      40 1587.23    54.5  1579.6      59 1575.55
    62.3  1570.4    66.2 1562.54    70.2 1559.99    92.1 1560.02    96.9 1558.58
   101.6  1555.1   113.6  1544.6   125.3 1532.81   129.1 1530.55     133 1529.53
   160.11528.204   173.3 1525.52     184 1525.88   190.8 1528.25   191.2  1528.4
   205.8 1533.44   229.5 1533.63   241.4 1535.82   250.9 1539.72   267.4 1550.03
   291.1 1560.23   304.6 1564.39   319.4  1566.6   333.2 1572.23   382.3 1585.48
#Mann= 4 ,-1 , 0
       0      .1       0   160.1    .045       0   190.8      .1       0
   191.2      .1       0
#XS Ineff= 2 , 0
                             210            1540
Permanent Ineff=
       F       F
Bank Sta=160.1,190.8
XS Rating Curve= 0 ,0
Exp/Cntr=0.5,0.3

Type RM Length L Ch R = 1 ,10386   ,43.9,44,45.1
XS GIS Cut Line= 4
     1990322.451      245136.924     1990222.625      244980.674
     1990195.498      244936.187     1990075.056      244789.702
#Sta/Elev= 30
       0 1596.14    19.1 1589.59    56.1 1572.88    66.6 1567.44    73.2 1561.58
    77.1 1559.27    96.6 1559.87   104.6 1559.68   109.3 1558.85   112.2 1557.11
   123.8  1547.4   135.4 1541.41   147.5 1531.74     183 1526.49   193.81524.123
   205.3 1526.67   220.7 1531.83   224.6 1532.56   281.5 1533.27   284.5 1535.15
   291.5    1542     297 1546.11   305.5 1549.36   316.6 1554.94   325.1  1556.4
   338.3 1563.33   376.1 1573.73   397.3 1578.51   410.1    1584   427.2  1589.6
#Mann= 3 , 0 , 0
       0      .1       0     183    .045       0   205.3      .1       0
#XS Ineff= 3 ,-1
       0     160 1534.64     226     230 1531.79     230     400    1540
Permanent Ineff=
       F       F       F
#Block Obstruct= 1 ,-1
  245.84  289.83 1560.36
Bank Sta=183,205.3
XS Rating Curve= 0 ,0
Exp/Cntr=0.5,0.3