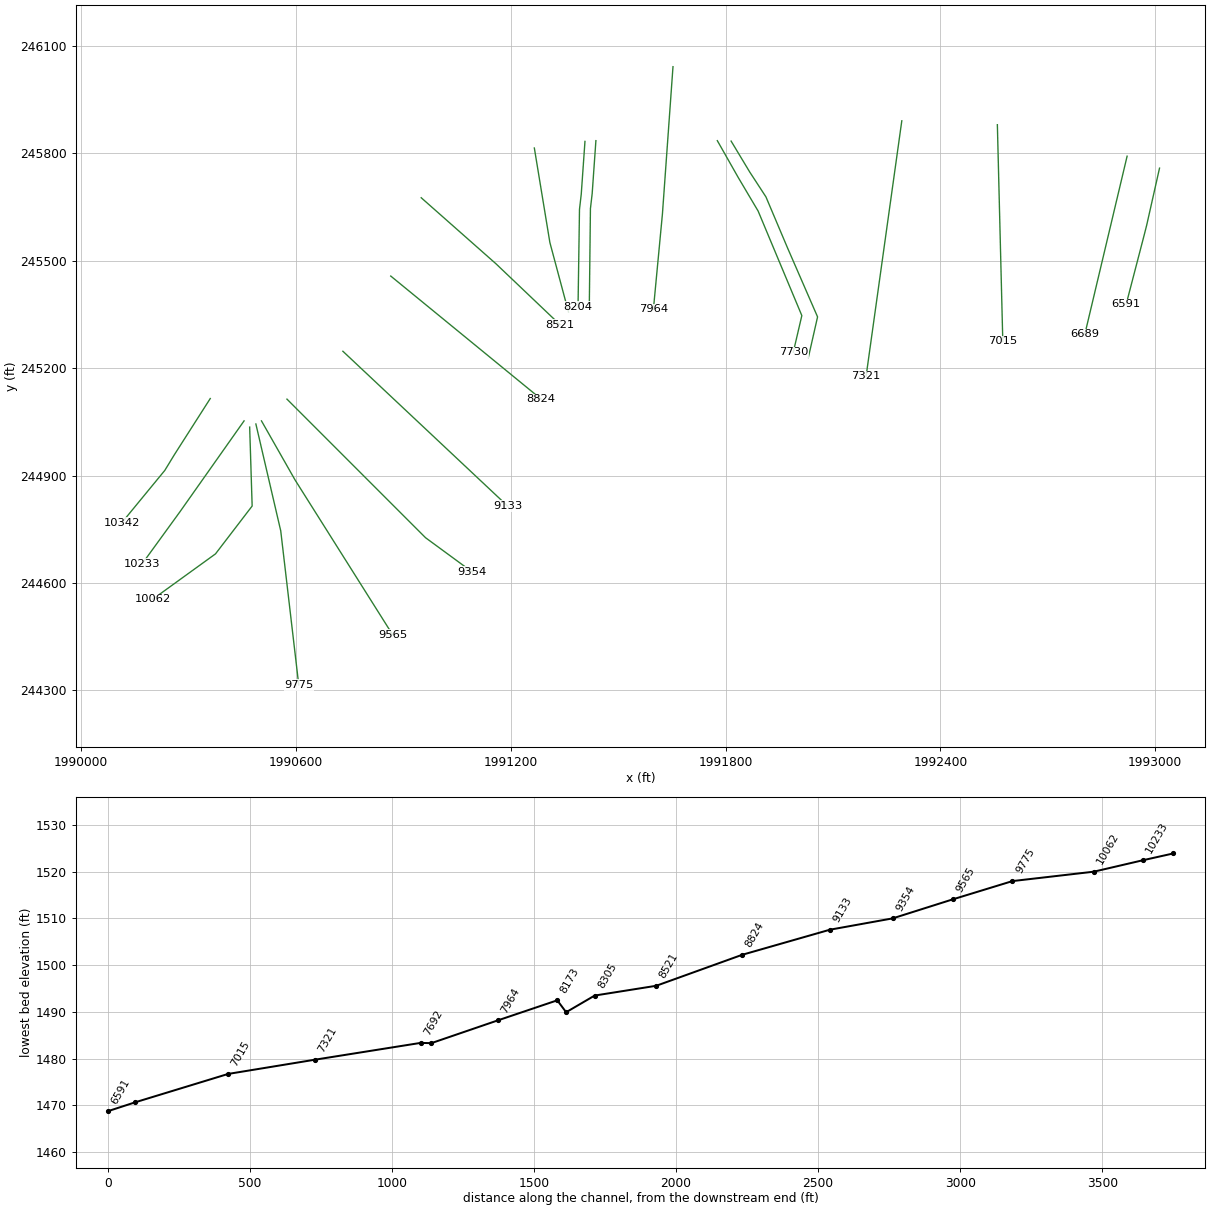
HEC-RAS study MADAMCK.prj: MADAMCK

--- MADAMCK.g01 (geometry) --- (continued)

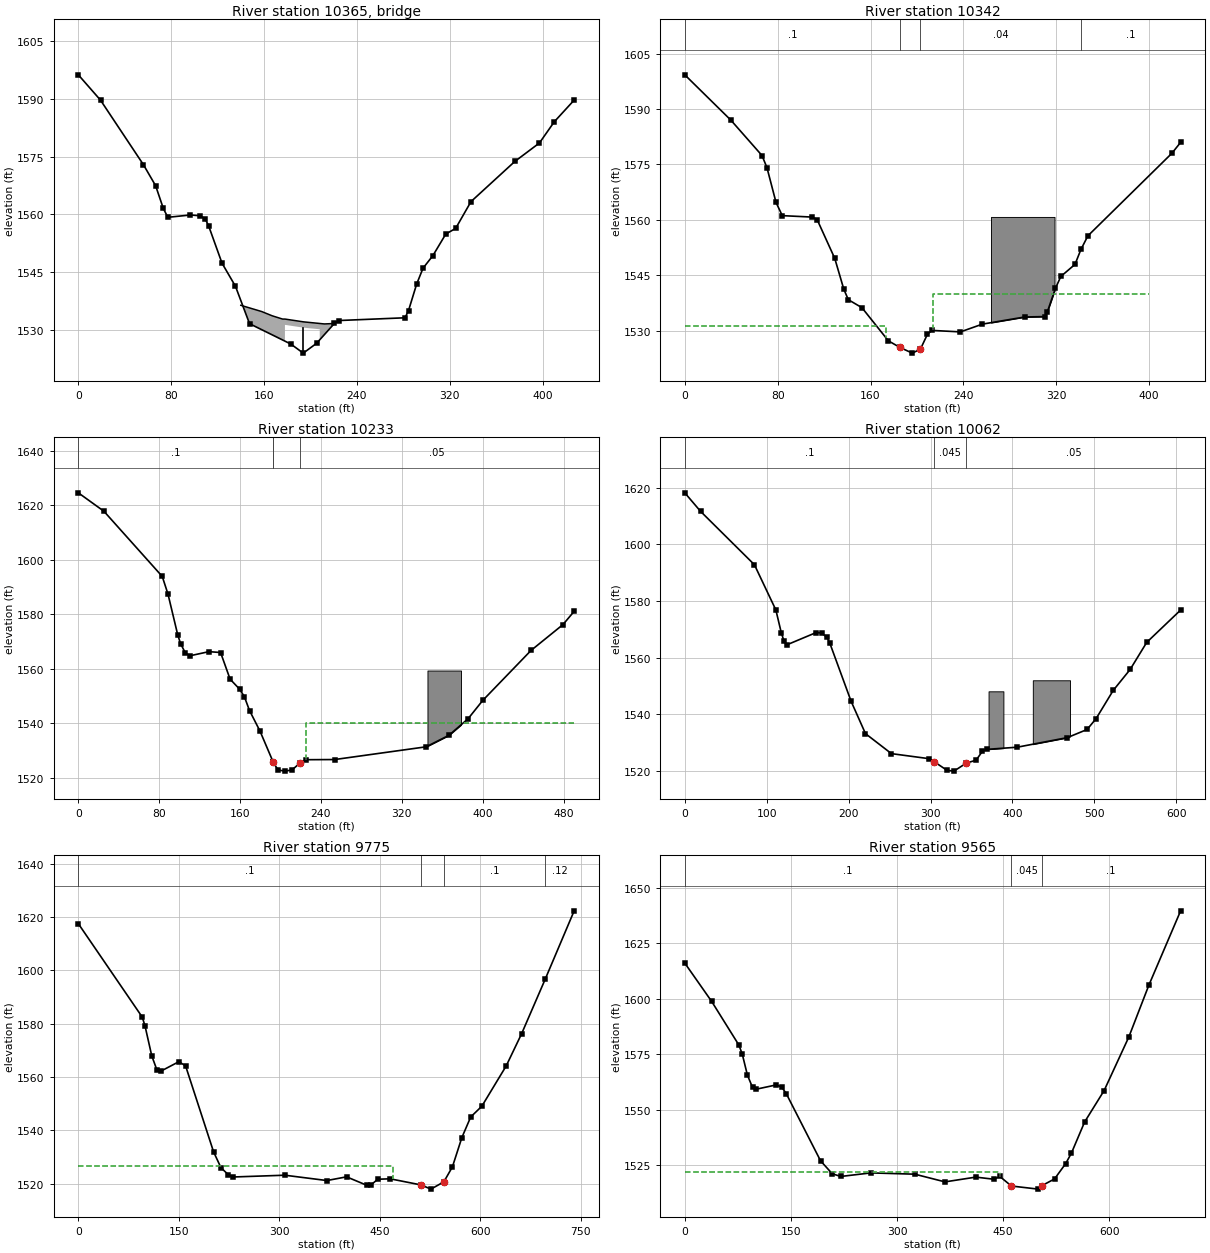
Type RM Length L Ch R = 3 ,10365   ,,,
BEGIN DESCRIPTION:
Unnamed Road
Survey ID: MAC130
END DESCRIPTION:
Bridge Culvert--1,0,-1,-1, 0
Deck Dist Width WeirC Skew NumUp NumDn MinLoCord MaxHiCord MaxSubmerge Is_Ogee
18,12,2.6,0, 11, 13, , , 0.98, 0, 0,0,,
     140     158     167     176     178     178     194     208     208     212
     221
  1536.51534.8831533.788 1532.94 1532.94 1532.941532.2161531.7981531.7981531.678
  1531.8
                                         1531.441530.7161530.298
        
     140     158     167     176     178     178     194     208     208     212
     221     230     240
  1536.51534.8831533.788 1532.94 1532.94 1532.941532.2161531.7981531.7981531.678
  1531.8  1530.5    1529
                                         1531.441530.7161530.298
                        
Pier Skew, UpSta & Num, DnSta & Num=  ,193, 2 ,193, 2 , 0 , 0 , 0 ,,
       1       1
       0    1531
       1       1
       0    1531
BR Coef=-1 , 1 , 0 ,2, 0 ,,,0.8,0,1.2,0,
WSPro=,,,, 1 ,,,, 0 ,,,, 0 ,,,,-1 ,-1 ,-1 , 0 , 0 , 0 , 0 , 0
BR U #Sta/Elev= 30
       0 1596.14    19.1 1589.59    56.1 1572.88    66.6 1567.44    73.2 1561.58
    77.1 1559.27    96.6 1559.87   104.6 1559.68   109.3 1558.85   112.2 1557.11
   123.8  1547.4   135.4 1541.41   147.5 1531.74     183 1526.49   193.81524.123
   205.3 1526.67   220.7 1531.83   224.6 1532.56   281.5 1533.27   284.5 1535.15
   291.5    1542     297 1546.11   305.5 1549.36   316.6 1554.94   325.1  1556.4
   338.3 1563.33   376.1 1573.73   397.3 1578.51   410.1    1584   427.2  1589.6
BR U #Mann= 3
       0      .1     183     .04   205.3      .1
BR D #Sta/Elev= 30
       0 1599.25    39.7 1586.98    66.5 1577.41    70.8 1574.11    78.6  1564.7
      84 1561.13   109.8 1560.74     114 1560.07   129.2 1549.56     137 1541.21
   140.9 1538.37   152.6 1536.22   175.4 1527.24   185.3 1525.46     196 1523.91
     203 1524.98   209.1 1529.04   212.9 1530.06   237.5 1529.66   256.4 1531.76
   292.8 1533.69     310  1533.8   312.4 1535.12   319.3 1541.42     324 1544.67
   336.2 1547.94   341.3 1551.97   347.3 1555.66   419.6 1577.99   427.2 1580.96
BR D #Mann= 4
       0      .1   185.3     .04     203     .04   341.3      .1
BC Design=,, 0 ,, 0 ,,,,,,
BC Use User HTab Curves=0
BC User HTab FreeFlow(D)= 0

Type RM Length L Ch R = 1 ,10342   ,108.3,108.8,106.3
XS GIS Cut Line= 4
     1990360.429      245115.223     1990260.603      244958.973
     1990233.476      244914.486     1990113.033      244768.001
#Sta/Elev= 30
       0 1599.25    39.7 1586.98    66.5 1577.41    70.8 1574.11    78.6  1564.7
      84 1561.13   109.8 1560.74     114 1560.07   129.2 1549.56     137 1541.21
   140.9 1538.37   152.6 1536.22   175.4 1527.24   185.3 1525.46     196 1523.91
     203 1524.98   209.1 1529.04   212.9 1530.06   237.5 1529.66   256.4 1531.76
   292.8 1533.69     310  1533.8   312.4 1535.12   319.3 1541.42     324 1544.67
   336.2 1547.94   341.3 1551.97   347.3 1555.66   419.6 1577.99   427.2 1580.96
#Mann= 4 ,-1 , 0
       0      .1       0   185.3    .045       0     203     .04       0
   341.3      .1       0
#XS Ineff= 3 ,-1
       0173.6667 1531.37212.3333     214  1528.8     214     400    1540
Permanent Ineff=
       F       F       F
#Block Obstruct= 1 ,-1
  263.83  318.54 1560.78
Bank Sta=185.3,203
XS Rating Curve= 0 ,0
Exp/Cntr=0.5,0.3

Type RM Length L Ch R = 1 ,10233   ,169.9,171.5,163.5
XS GIS Cut Line= 3
      1990454.89      245052.826     1990276.071      244799.354
     1990170.168      244653.521
#Sta/Elev= 30
       0 1624.57    25.3 1617.81      83 1593.88    88.7 1587.37    98.3 1572.45
   101.1 1569.25   105.7  1565.9   110.1 1564.74   129.2 1566.28   140.7 1565.96
   150.1 1556.18   159.5 1552.52   164.2 1549.76   169.3 1544.68   179.7  1537.1
   192.5 1525.94   192.61525.855   197.4 1522.87   204.2 1522.43   211.3 1522.85
   218.81525.267   225.3 1526.62   253.5 1526.68   344.1 1531.36   366.5 1535.57
   385.4 1541.62     400 1548.38   447.7 1566.71   479.3  1576.2   490.4 1581.08
#Mann= 4 ,-1 , 0
       0      .1       0   192.5      .1       0   192.6    .045       0
   218.8     .05       0
#XS Ineff= 2 , 0
                             225            1540
Permanent Ineff=
       F       F
#Block Obstruct= 1 ,-1
  345.31  378.48 1559.35
Bank Sta=192.6,218.8
XS Rating Curve= 0 ,0
Exp/Cntr=0.3,0.1

Type RM Length L Ch R = 1 ,10062   ,219.9,286.2,291.3
XS GIS Cut Line= 4
     1990470.515      245035.465      1990477.46      244814.979
     1990375.029      244681.298     1990199.682      244554.562
#Sta/Elev= 30
       0 1618.16    19.3 1611.61      85  1592.8   111.2 1576.84   117.8 1568.82
   121.1  1565.9   124.4 1564.52   160.5 1568.89     167 1568.73   173.6 1567.18
   176.9 1565.27   203.1  1544.6   220.6 1533.23   252.3 1526.17   297.8 1524.41
   304.8 1523.26   320.2 1520.28   328.6    1520   343.71522.823   355.7 1523.87
   363.3 1526.97   368.7 1527.67   405.9 1528.44     467 1531.81   491.2 1534.69
   502.2 1538.53   523.1 1548.47   543.8 1555.87     564 1565.41   605.4 1576.82
#Mann= 3 , 0 , 0
       0      .1       0   304.8    .045       0   343.7     .05       0
#Block Obstruct= 2 ,-1
  370.89  389.01 1548.15  424.93  470.38 1552.04
Bank Sta=304.8,343.7
XS Rating Curve= 0 ,0
Exp/Cntr=0.3,0.1

Type RM Length L Ch R = 1 ,9775    ,193.2,210.2,216.1
XS GIS Cut Line= 3
     1990487.876      245044.146     1990557.321      244745.535
     1990607.668      244314.979
#Sta/Elev= 30
       0 1617.56    95.4 1582.52    99.5 1579.24   109.6 1567.99   117.2 1562.75
   123.1 1562.23   150.1 1565.79   160.1 1564.22   201.9 1531.95   212.9 1526.03
   223.8 1523.42   230.8 1522.54   308.3 1523.21     371 1521.21   400.4  1522.6
   430.5 1519.44   437.1 1519.63     447  1521.7   465.4 1521.86   511.91519.547
   526.3 1517.99   545.6 1520.72   558.4 1526.36   572.5 1537.34   585.7 1545.06
   602.3 1549.09   638.6 1564.18   661.7  1576.3   696.8 1596.69   740.1 1622.38
#Mann= 4 ,-1 , 0
       0      .1       0   511.9    .045       0   545.6      .1       0
   696.8     .12       0
#XS Ineff= 2 , 0
             470 1526.73
Permanent Ineff=
       F       F
Bank Sta=511.9,545.6
XS Rating Curve= 0 ,0
Exp/Cntr=0.3,0.1

Type RM Length L Ch R = 1 ,9565    ,203,211.5,216.4
XS GIS Cut Line= 3
     1990503.501      245052.826     1990597.251      244887.896
     1990869.821      244455.604
#Sta/Elev= 30
       0 1616.05      38 1598.74    76.5 1579.05    81.3 1574.89    88.5  1565.5
    95.7 1559.99   100.5 1559.13     129 1561.08   136.8 1560.19   143.4 1557.17
   191.9 1526.84   208.3 1521.05   220.4 1519.79     263  1521.4   325.1 1520.82
   367.8 1517.35   411.3  1519.5   436.9 1518.54   445.3 1519.79   461.61515.486
   499.6 1514.08   504.21515.559   522.6 1518.68   538.4 1525.63   546.4 1530.29
   565.1 1544.37   592.7 1558.57   627.6 1582.72   655.8 1606.01   700.8 1639.63
#Mann= 3 , 0 , 0
       0      .1       0   461.6    .045       0   504.2      .1       0
#XS Ineff= 2 , 0
           446.2 1521.81
Permanent Ineff=
       F       F
Bank Sta=461.6,504.2
XS Rating Curve= 0 ,0
Exp/Cntr=0.3,0.1

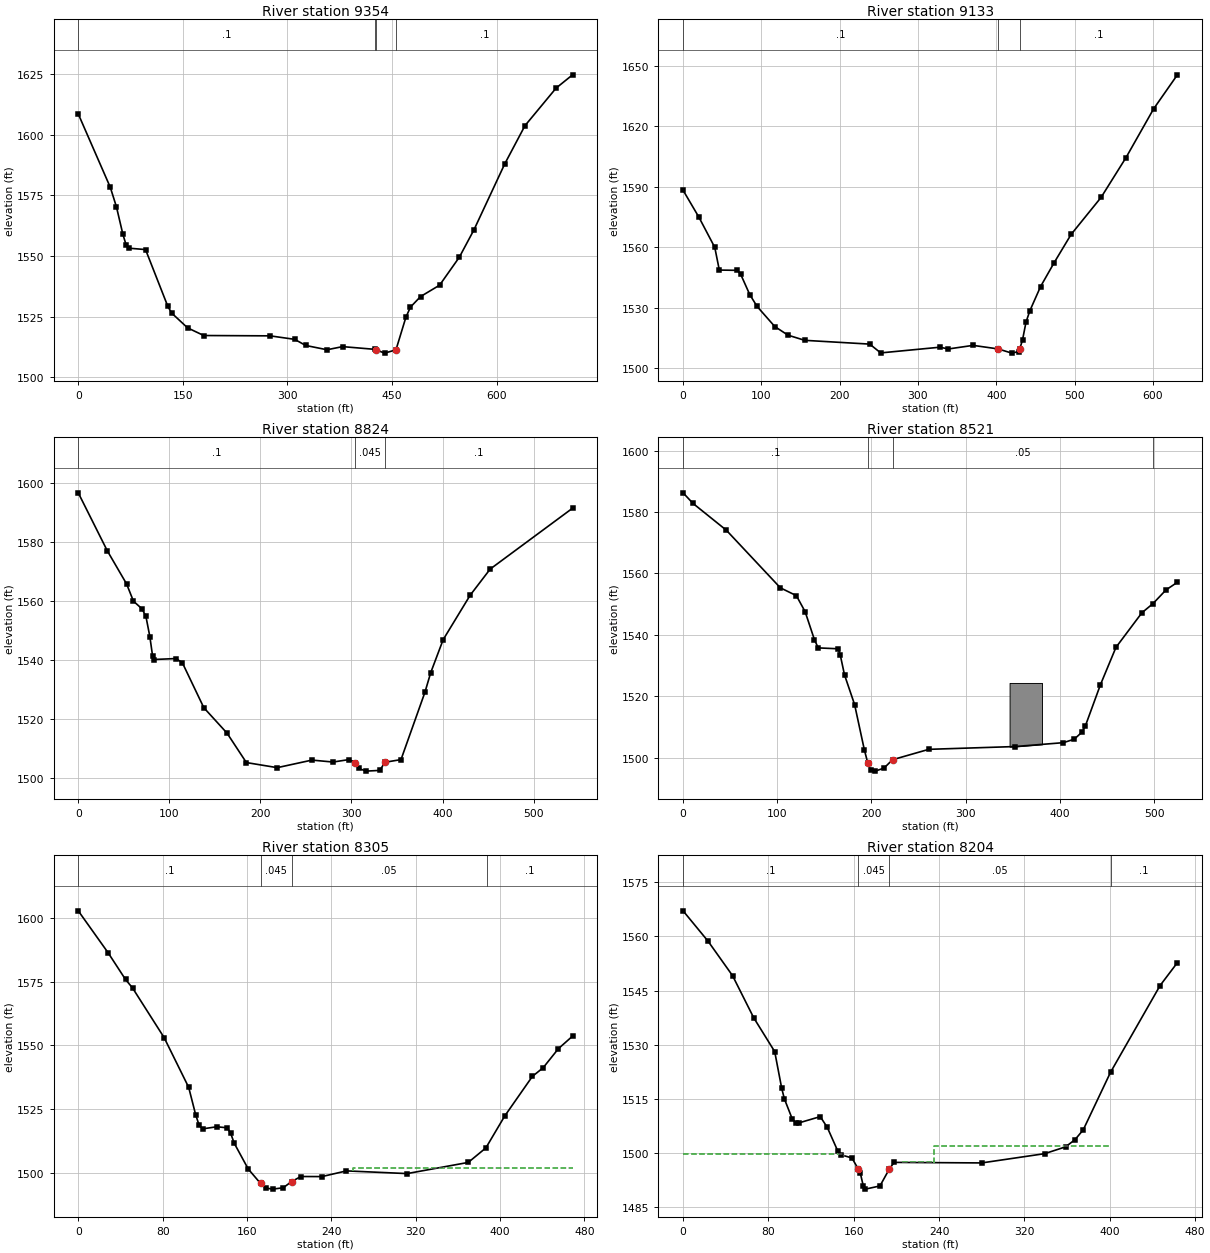
Type RM Length L Ch R = 1 ,9354    ,221.5,220.7,219.7
Node Name=C
XS GIS Cut Line= 3
     1990574.682       245113.59     1990961.835      244726.437
     1991092.043      244630.951
#Sta/Elev= 30
       0 1608.62      46 1578.33    54.8 1570.28      64    1559    68.7 1554.58
    73.3 1553.26    96.5  1552.7   128.5 1529.26   134.1 1526.49   156.8 1520.43
     180 1517.27   275.2 1517.13   310.4 1515.69   326.2 1513.17   356.8  1511.4
   379.1 1512.69   425.9 1511.56   426.6 1511.42   439.4 1510.01   455.7 1511.37
     470 1524.86   476.5 1528.99   490.9 1533.32   518.3 1538.03   546.6 1549.57
   567.7 1560.93   611.7 1588.02   640.7 1603.77   685.4 1619.28     709 1624.74
#Mann= 4 ,-1 , 0
       0      .1       0   425.9      .1       0   426.6    .045       0
   455.7      .1       0
Bank Sta=426.6,455.7
XS Rating Curve= 0 ,0
Exp/Cntr=0.3,0.1

Type RM Length L Ch R = 1 ,9133    ,307.9,308.9,302
XS GIS Cut Line= 2
     1990730.932      245247.271     1991191.001      244814.979
#Sta/Elev= 30
       0  1588.3    20.3  1574.9    40.5 1559.98    46.3 1548.75    69.2 1548.61
    73.6 1546.64    85.2 1536.58    94.5 1530.74   117.1 1520.78     134 1516.49
   155.4 1513.93   238.4 1512.06   252.4  1507.7   327.9 1510.52   338.9 1509.66
   370.4 1511.43   402.31509.683   419.9 1507.59   428.5 1508.37     4301509.737
   433.5 1514.09     438 1522.98   442.9  1528.6   456.6 1540.59     474 1552.47
   495.6 1566.42   533.9 1584.78   565.7 1604.49     601 1628.66   631.3 1645.49
#Mann= 3 , 0 , 0
       0      .1       0   402.3    .045       0     430      .1       0
Bank Sta=402.3,430
XS Rating Curve= 0 ,0
Exp/Cntr=0.3,0.1

Type RM Length L Ch R = 1 ,8824    ,277.3,302.6,292.6
XS GIS Cut Line= 2
     1990864.612       245457.34     1991284.751       245113.59
#Sta/Elev= 30
       0 1596.81    31.9  1577.1    53.1 1565.83    60.6 1559.99      70 1557.38
    74.3  1554.8    78.6 1547.97    81.6 1541.39    82.8 1540.16   107.3 1540.48
   114.3 1539.06   137.9 1523.77   163.4 1515.12   184.6 1505.13   218.5  1503.4
   256.6 1505.97   279.8 1505.31   297.8 1506.17   304.11504.948   308.1 1503.12
     316 1502.22   331.1 1502.47   336.81505.233   354.4 1506.14   380.7 1529.05
     387 1535.66   400.7 1546.91   430.4 1562.03   452.3 1570.89   542.8 1591.59
#Mann= 3 , 0 , 0
       0      .1       0   304.1    .045       0   336.8      .1       0
Bank Sta=304.1,336.8
XS Rating Curve= 0 ,0
Exp/Cntr=0.3,0.1

Type RM Length L Ch R = 1 ,8521    ,227.6,216.6,200.4
XS GIS Cut Line= 3
     1990949.682       245676.09     1991158.015      245492.063
     1991336.834      245321.923
#Sta/Elev= 30
       0 1586.26    10.6  1582.8    45.9 1574.09   103.3 1555.31   120.3 1552.76
   129.6 1547.53   139.5 1538.38   143.5 1535.74   164.5 1535.45   166.8 1533.56
   171.4 1526.94   182.1 1517.29   192.4 1502.62   196.21498.109   199.3 1495.87
     204 1495.59   213.3 1496.57   222.41499.307   260.9 1502.69   352.6  1503.6
   403.7 1504.86   415.3 1505.99   423.4 1508.27   426.9 1510.14   443.1 1523.74
   459.6 1535.92   487.2 1547.21   498.8 1550.14   512.7 1554.62   524.8 1557.12
#Mann= 4 ,-1 , 0
       0      .1       0   196.2    .045       0   222.4     .05       0
   498.8      .1       0
#Block Obstruct= 1 ,-1
  346.64  381.07 1524.32
Bank Sta=196.2,222.4
XS Rating Curve= 0 ,0
Exp/Cntr=0.3,0.1

Type RM Length L Ch R = 1 ,8305    ,106.3,100.5,93.9
XS GIS Cut Line= 3
     1991265.654      245814.979     1991309.057       245551.09
      1991361.14      245356.646
#Sta/Elev= 30
       0 1602.91    28.2 1586.49    44.8 1575.93    51.5 1572.57    81.4 1553.08
   104.7 1533.52   111.3 1522.77   114.6 1518.62     118  1517.2   131.3 1518.01
   141.2 1517.62   144.6 1515.37   147.8 1511.61   161.2 1501.39   172.81495.762
   177.8 1493.92   184.5  1493.5   194.4 1494.05   202.21496.453   211.1 1498.46
     231 1498.43   254.3 1500.67   311.8 1499.61   369.8    1504   386.5 1509.71
   404.4 1522.26   430.6 1537.83   440.8 1541.22   455.3 1548.74   468.7 1553.66
#Mann= 4 ,-1 , 0
       0      .1       0   172.8    .045       0   202.2     .05       0
  387.43      .1       0
#XS Ineff= 2 , 0
                          260.85         1501.81
Permanent Ineff=
       F       F
Bank Sta=172.8,202.2
XS Rating Curve= 0 ,0
Exp/Cntr=0.5,0.3

Type RM Length L Ch R = 1 ,8204    ,32.3,31.2,30.6
XS GIS Cut Line= 4
     1991407.069      245833.456     1991396.652       245685.54
     1991391.791      245643.873     1991387.688      245370.752
#Sta/Elev= 30
       0 1567.11    23.4  1558.7    46.4 1549.13    66.2 1537.47    85.9 1528.08
    92.5 1517.85      95 1514.95   102.3 1509.44   105.6 1508.37   108.9 1508.33
   128.6 1510.04   135.2 1507.05   145.1 1500.46   148.4 1499.43   158.3 1498.57
   164.41495.432   166.1 1494.45     169 1490.75   170.91489.934  184.59 1490.82
   193.51495.589   197.9 1497.35   279.9  1497.2     339 1499.77   358.6 1501.66
   367.4 1503.65   375.1 1506.35   400.7 1522.32   447.2  1546.4   463.4 1552.74
#Mann= 4 ,-1 , 0
       0      .1       0   164.4    .045       0   193.5     .05       0
   400.7      .1       0
#XS Ineff= 3 ,-1
       0     151 1499.72     205     235 1497.56     235     400    1502
Permanent Ineff=
       F       F       F
Bank Sta=164.4,193.5
XS Rating Curve= 0 ,0
Exp/Cntr=0.5,0.3

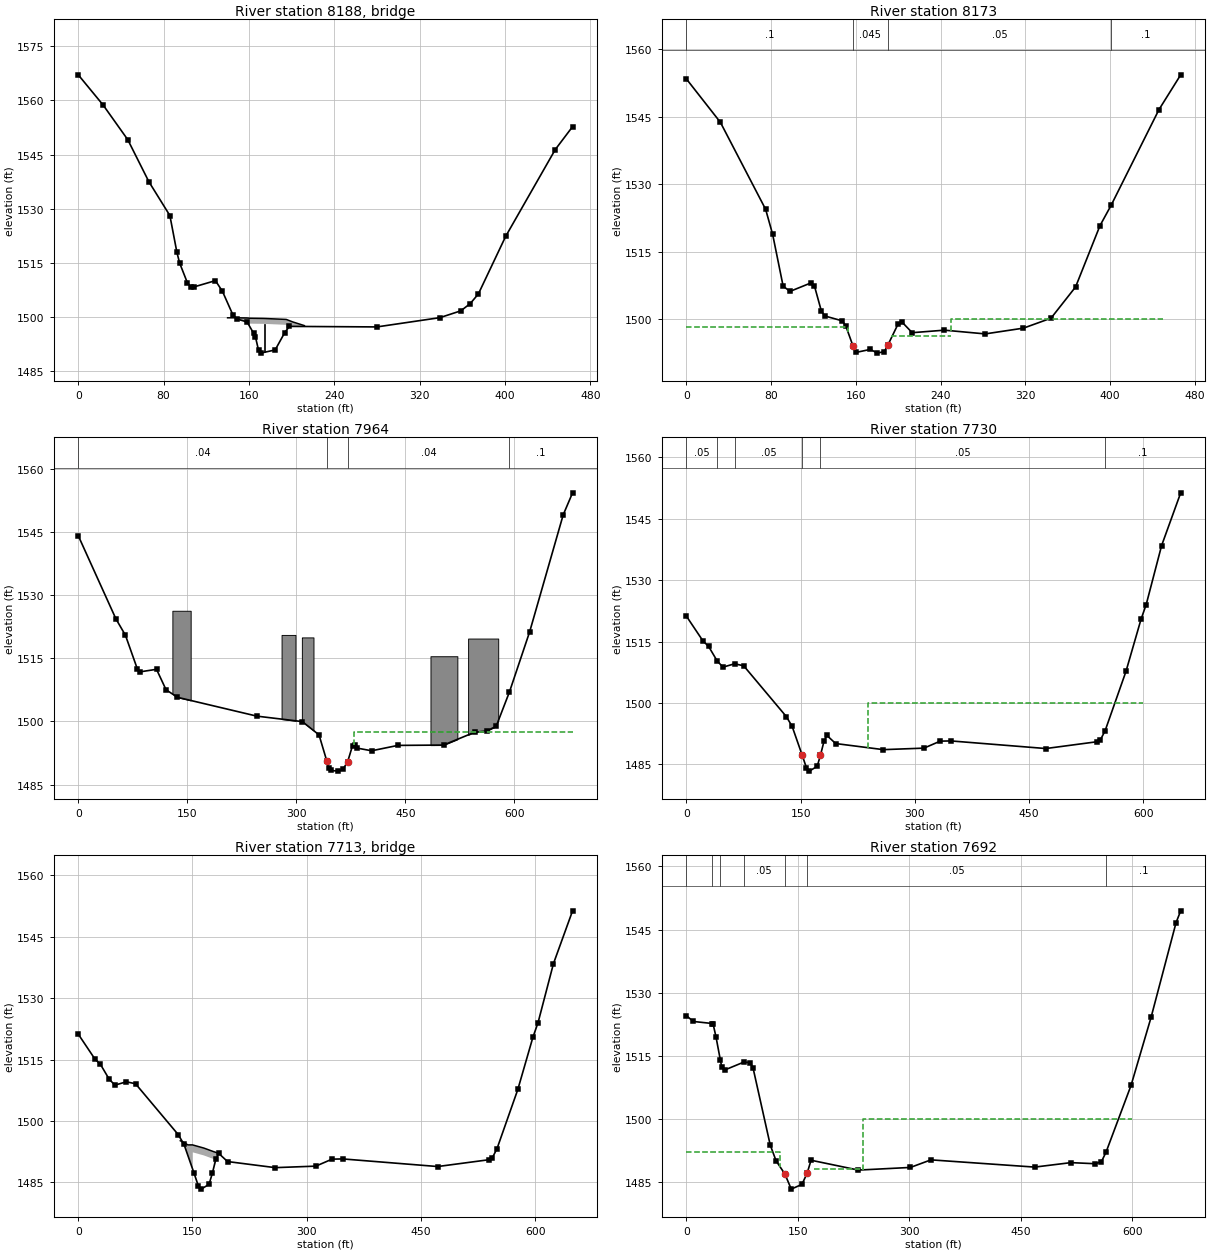
Type RM Length L Ch R = 3 ,8188    ,,,
BEGIN DESCRIPTION:
Bridge Pass
Survey ID: MAC120
END DESCRIPTION:
Bridge Culvert--1,0,-1,-1, 0
Deck Dist Width WeirC Skew NumUp NumDn MinLoCord MaxHiCord MaxSubmerge Is_Ogee
10,12,2.6,0, 10, 8, , , 0.98, 0, 0,0,,
     140     148     158     161     161     174     195     195     201     212
 1499.73 1499.731499.688 1499.61 1499.61 1499.551499.2781499.2781498.5971497.563
                                 1498.11 1498.051497.778
     140     148     156     156     174     190     190     201
 1499.73 1499.731499.6881499.688 1499.551499.2781499.2781498.597
                        1498.188 1498.051497.778
Pier Skew, UpSta & Num, DnSta & Num=  ,175, 2 ,175, 2 , 0 , 0 , 0 ,,
       1       1
       0    1499
       1       1
       0    1499
BR Coef=-1 , 1 , 0 ,1.25, 0 ,,,0.8,0,2,0,
WSPro=,,,, 1 ,,,, 0 ,,,, 0 ,,,,-1 ,-1 ,-1 , 0 , 0 , 0 , 0 , 0
BR U #Sta/Elev= 30
       0 1567.11    23.4  1558.7    46.4 1549.13    66.2 1537.47    85.9 1528.08
    92.5 1517.85      95 1514.95   102.3 1509.44   105.6 1508.37   108.9 1508.33
   128.6 1510.04   135.2 1507.05   145.1 1500.46   148.4 1499.43   158.3 1498.57
   164.41495.432   166.1 1494.45     169 1490.75   170.91489.934  184.59 1490.82
   193.51495.589   197.9 1497.35   279.9  1497.2     339 1499.77   358.6 1501.66
   367.4 1503.65   375.1 1506.35   400.7 1522.32   447.2  1546.4   463.4 1552.74
BR U #Mann= 4
       0      .1   164.4     .04   193.5     .05   400.7      .1
BR D #Sta/Elev= 30
       0 1553.38    32.1 1543.74    74.8 1524.41    81.4 1518.86    91.3 1507.36
    97.8 1506.19   117.6 1508.08   120.9 1507.35   127.4 1501.81   130.7 1500.73
   147.2 1499.64   150.5 1498.47   157.1 1494.16   160.4 1492.65   173.6 1493.31
   180.2 1492.48   186.8 1492.83   190.2 1494.29     200 1499.06   203.2 1499.45
   213.1 1497.02   243.5 1497.58     282 1496.75   318.1 1498.03   344.1 1500.24
   367.3 1507.18   390.3 1520.78     401 1525.39     446 1546.57   466.5 1554.29
BR D #Mann= 4
       0      .1   157.1     .04   190.2     .05     401      .1
BC Design=,, 0 ,, 0 ,,,,,,
BC Use User HTab Curves=0
BC User HTab FreeFlow(D)= 0

Type RM Length L Ch R = 1 ,8173    ,206.7,209.1,202.8
XS GIS Cut Line= 4
     1991437.625      245835.539     1991427.208      245687.623
     1991422.347      245645.956     1991419.155      245369.666
#Sta/Elev= 30
       0 1553.38    32.1 1543.74    74.8 1524.41    81.4 1518.86    91.3 1507.36
    97.8 1506.19   117.6 1508.08   120.9 1507.35   127.4 1501.81   130.7 1500.73
   147.2 1499.64   150.5 1498.47   157.1 1494.16   160.4 1492.65   173.6 1493.31
   180.2 1492.48   186.8 1492.83   190.2 1494.29     200 1499.06   203.2 1499.45
   213.1 1497.02   243.5 1497.58     282 1496.75   318.1 1498.03   344.1 1500.24
   367.3 1507.18   390.3 1520.78     401 1525.39     446 1546.57   466.5 1554.29
#Mann= 4 ,-1 , 0
       0      .1       0   157.1    .045       0   190.2     .05       0
     401      .1       0
#XS Ineff= 3 ,-1
       0 152.333  1498.2 193.667     250  1496.2     250     450    1500
Permanent Ineff=
       F       F       F
Bank Sta=157.1,190.2
XS Rating Curve= 0 ,0
Exp/Cntr=0.5,0.3

Type RM Length L Ch R = 1 ,7964    ,221.9,234.1,263.5
XS GIS Cut Line= 3
     1991652.951      246042.193     1991623.438      245630.734
     1991598.192      245364.241
#Sta/Elev= 30
       0 1544.19    51.8 1524.41    64.9 1520.52    81.3  1512.5    84.4 1511.79
   107.7 1512.41   120.8 1507.55   136.5 1505.75   245.8 1501.27   308.3 1499.97
   331.3 1496.82   342.2 1490.49   344.5 1489.04   347.8 1488.34   357.7 1488.19
   364.2  1488.6   370.8 1490.48   377.4 1494.25   380.7 1494.41     384 1493.66
   403.7 1493.03   439.8 1494.31   502.6 1494.39   545.4 1497.44   561.9 1497.74
   575.1 1498.86   593.4 1507.05   621.2 1521.36   667.3 1549.15   680.2 1554.39
#Mann= 4 ,-1 , 0
       0     .04       0   342.2    .045       0   370.8     .04       0
   593.4      .1       0
#XS Ineff= 2 , 0
                             380         1497.59
Permanent Ineff=
       F       F
#Block Obstruct= 5 ,-1
  129.51  154.68 1526.34  279.76   298.9 1520.59  307.69  323.68    1520
  484.67  521.67 1515.52  536.45  577.88 1519.73
Bank Sta=342.2,370.8
XS Rating Curve= 0 ,0
Exp/Cntr=0.5,0.3

Type RM Length L Ch R = 1 ,7730    ,37.1,38,39
XS GIS Cut Line= 6
1991776.78316541245835.5220945411991834.78405735245733.349128765
1991872.16788353245670.1814971231991890.69623387245639.034423461
 1992012.8395866245346.9260272481991988.87822105245244.370173501
#Sta/Elev= 30
       0 1521.21    21.7 1515.17    29.2  1513.8    40.5 1510.23    48.1 1508.74
    63.2 1509.56    75.2 1509.08   131.2 1496.66   138.8 1494.29     152 1487.24
  157.71  1484.1   161.51483.317  171.76  1484.5     176 1487.16   180.8 1490.69
   184.6 1492.03     196 1490.06   258.6 1488.57     312 1488.94   333.3 1490.65
   347.5  1490.7     472 1488.84   539.5 1490.51   543.7 1490.98   549.8 1493.17
   577.2 1507.68     597 1520.44   603.8 1524.05     624 1538.45   649.1 1551.36
#Mann= 6 ,-1 , 0
       0     .05       0    40.5    .016       0    63.2     .05       0
     152    .045       0     176     .05       0   549.8      .1       0
#XS Ineff= 3 ,-1
       0     130 1495.32     182     238 1488.81     238     600    1500
Permanent Ineff=
       F       F       F
Bank Sta=152,176
XS Rating Curve= 0 ,0
Exp/Cntr(USF)=0,0
Exp/Cntr=0.5,0.3

Type RM Length L Ch R = 3 ,7713    ,,,
BEGIN DESCRIPTION:
Unnamed Road
Survey ID: 54089MAC110
END DESCRIPTION:
Bridge Culvert--1,0,-1,-1, 0
Deck Dist Width WeirC Skew NumUp NumDn MinLoCord MaxHiCord MaxSubmerge Is_Ogee
9,10,2.6,0, 8, 9, , , 0.98, 0, 0,0,,
     134     144     150     150     165     178     178     186
1495.1511494.1341494.1341494.1341493.3521492.4631492.4631491.993
                        1492.3341491.5521490.663
     100     134     135     135     150     163     163     171     180
1495.1511494.1341494.1341494.1341493.3521492.4631492.4631491.993    1490
                        1492.3341491.5521490.663
BR Coef=-1 , 1 , 0 ,, 0 ,,,0.8,0,1.2,0,
WSPro=,,,, 1 ,,,, 0 ,,,, 0 ,,,,-1 ,-1 ,-1 , 0 , 0 , 0 , 0 , 0
BR U #Sta/Elev= 30
       0 1521.21    21.7 1515.17    29.2  1513.8    40.5 1510.23    48.1 1508.74
    63.2 1509.56    75.2 1509.08   131.2 1496.66   138.8 1494.29     152 1487.24
  157.71  1484.1   161.51483.317  171.76  1484.5     176 1487.16   180.8 1490.69
   184.6 1492.03     196 1490.06   258.6 1488.57     312 1488.94   333.3 1490.65
   347.5  1490.7     472 1488.84   539.5 1490.51   543.7 1490.98   549.8 1493.17
   577.2 1507.68     597 1520.44   603.8 1524.05     624 1538.45   649.1 1551.36
BR U #Mann= 6
       0     .05    40.5    .016    63.2     .05     152     .04     176     .05
   549.8      .1
BR D #Sta/Elev= 30
       0 1524.57     9.2 1523.19    34.8  1522.7      36 1522.54    39.8 1519.55
    45.8 1513.93    47.5 1512.45    51.3 1511.64    76.9 1513.51    85.8 1513.43
    89.6 1512.21   112.8 1493.84   120.7 1490.07   132.4 1486.99   141.11483.368
  155.52 1484.51   162.5 1487.18   167.7 1490.23   231.4 1487.89   301.4 1488.52
     329 1490.32   468.6  1488.6   517.2 1489.66   550.2  1489.4   558.4  1489.9
   564.6 1492.17   598.2    1508   625.1 1524.14   658.8 1546.68     665 1549.46
BR D #Mann= 7
       0    .016    34.8     .05    45.8    .016    76.9     .05   132.4     .04
   162.5     .05   564.6      .1
BC Design=,, 0 ,, 0 ,,,,,,
BC Use User HTab Curves=0
BC User HTab FreeFlow(D)= 0

Type RM Length L Ch R = 1 ,7692    ,383.9,371.3,329.9
XS GIS Cut Line= 6
1991815.24856593245834.3756015291991867.02457071245748.384071969
1991912.57593801245678.4792682181991972.82744318245536.081621368
1992056.77461861245343.2677803051992031.04991819245229.905296458
#Sta/Elev= 30
       0 1524.57     9.2 1523.19    34.8  1522.7      36 1522.54    39.8 1519.55
    45.8 1513.93    47.5 1512.45    51.3 1511.64    76.9 1513.51    85.8 1513.43
    89.6 1512.21   112.8 1493.84   120.7 1490.07   132.4 1486.99   141.11483.368
  155.52 1484.51   162.5 1487.18   167.7 1490.23   231.4 1487.89   301.4 1488.52
     329 1490.32   468.6  1488.6   517.2 1489.66   550.2  1489.4   558.4  1489.9
   564.6 1492.17   598.2    1508   625.1 1524.14   658.8 1546.68     665 1549.46
#Mann= 7 ,-1 , 0
       0    .016       0    34.8     .05       0    45.8    .016       0
    76.9     .05       0   132.4    .045       0   162.5     .05       0
   564.6      .1       0
#XS Ineff= 3 ,-1
       0     126 1492.28     172     238  1488.1     238     600    1500
Permanent Ineff=
       F       F       F
Bank Sta=132.4,162.5
XS Rating Curve= 0 ,0
Exp/Cntr(USF)=0,0
Exp/Cntr=0.5,0.3

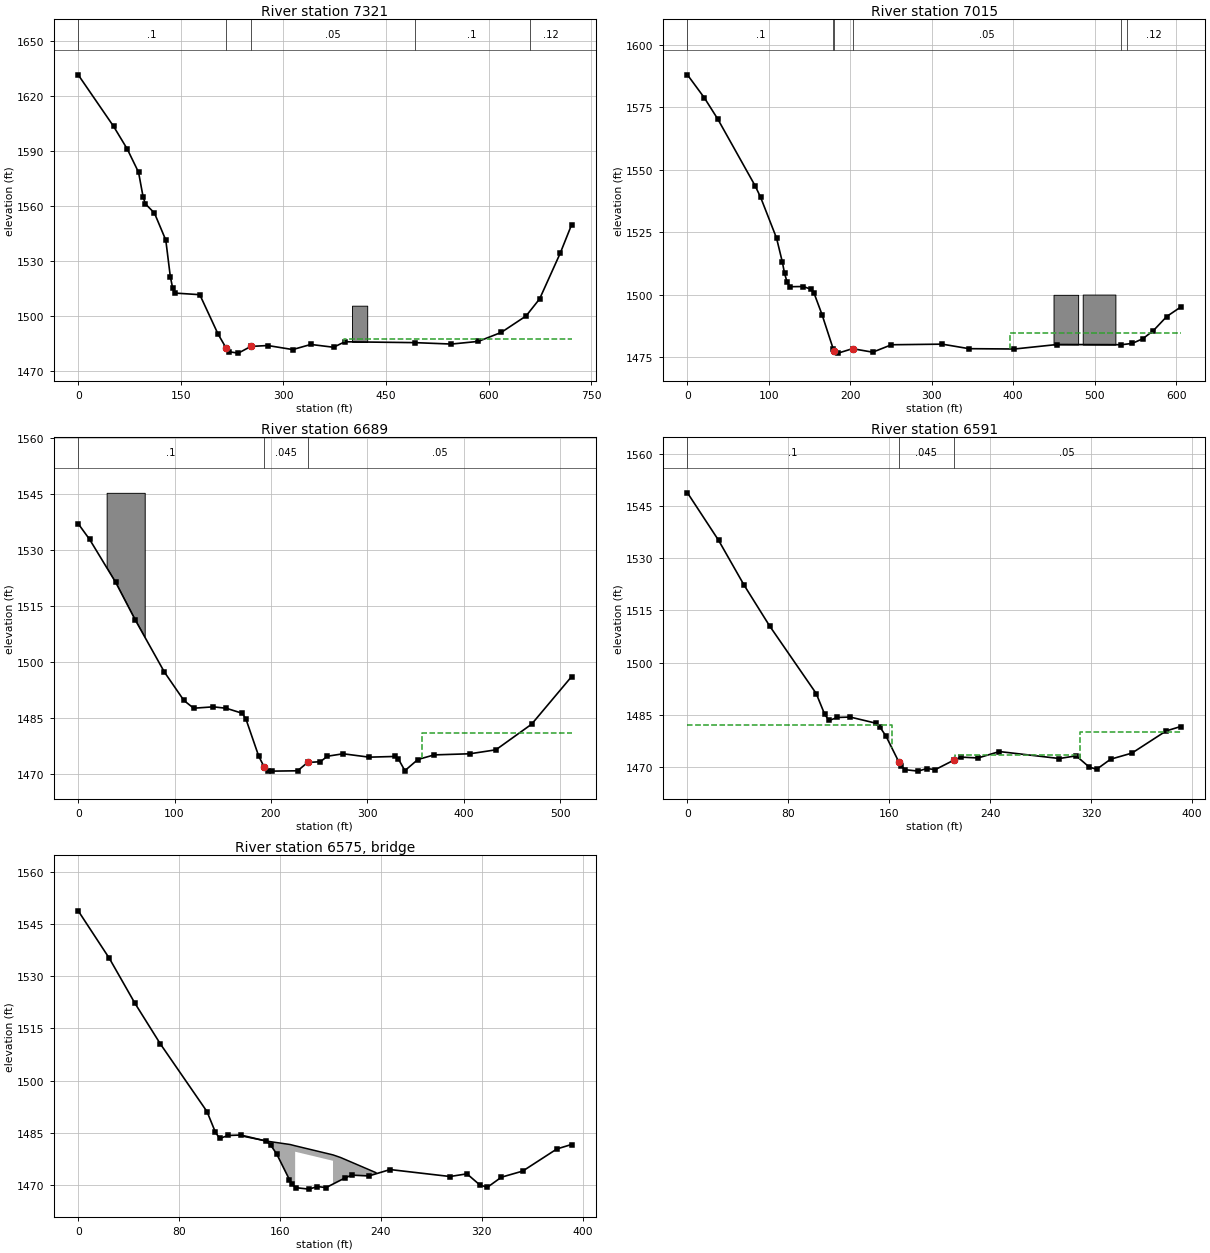
Type RM Length L Ch R = 1 ,7321    ,302.7,306,310.9
XS GIS Cut Line= 2
     1992292.057      245890.934     1992192.231      245176.958
#Sta/Elev= 30
       0 1631.42    51.8 1603.29    71.7 1590.98    88.2 1578.32    94.9 1564.77
    98.2 1561.09   111.4  1556.1     128 1541.36   134.6  1521.5   137.9 1515.48
   141.2 1512.51   177.7 1511.62   204.4 1490.14   216.31482.463   220.7 1480.51
     234 1479.78   252.31483.442   277.1 1483.92   313.5 1481.72     340 1484.51
   373.1 1482.98   389.7 1485.97   491.7  1485.5   545.4 1484.72   584.7 1486.17
   618.3 1491.08   654.5 1500.03   674.3 1509.33   704.4 1534.21   720.9 1549.61
#Mann= 5 ,-1 , 0
       0      .1       0   216.3    .045       0   252.3     .05       0
   491.7      .1       0     660     .12       0
#XS Ineff= 2 , 0
                          388.96         1487.36
Permanent Ineff=
       F       F
#Block Obstruct= 1 ,-1
  400.15  422.34 1505.63
Bank Sta=216.3,252.3
XS Rating Curve= 0 ,0
Exp/Cntr=0.3,0.1

Type RM Length L Ch R = 1 ,7015    ,330.4,326.1,312.7
XS GIS Cut Line= 2
     1992558.984      245880.083     1992574.176      245274.615
#Sta/Elev= 30
       0 1588.05    20.8 1578.83    37.2 1570.37    83.1 1543.66    89.7 1539.16
   109.4 1522.73   116.6 1513.05   119.2 1508.65   122.5 1504.99   125.8  1503.3
   142.2 1503.37     152 1502.24   155.3 1500.84   165.2 1492.18   179.2 1478.19
   180.11477.746   184.9 1476.73   202.71478.505   227.5 1477.11   250.5 1480.08
   312.8 1480.32   345.7 1478.51   401.5 1478.38     454 1480.18   532.8  1480.1
   545.9  1480.6     559 1482.46   572.1 1485.73   588.5 1491.38   605.7 1495.17
#Mann= 6 ,-1 , 0
       0      .1       0   179.2      .1       0   180.1    .045       0
   202.7     .05       0   532.8      .1       0     540     .12       0
#XS Ineff= 2 , 0
                          395.55          1484.8
Permanent Ineff=
       F       F
#Block Obstruct= 2 ,-1
  449.49   479.7 1500.05  485.34  525.45 1500.15
Bank Sta=180.1,202.7
XS Rating Curve= 0 ,0
Exp/Cntr=0.3,0.1

Type RM Length L Ch R = 1 ,6689    ,99.1,97.5,96.4
XS GIS Cut Line= 2
     1992921.398      245792.193     1992803.125      245294.146
#Sta/Elev= 30
       0 1537.11    11.9 1532.87    38.9 1521.35    59.1 1511.32    89.5 1497.25
   109.7 1489.65   119.8 1487.57   140.1 1487.94   153.6 1487.56   170.4  1486.2
   174.2 1484.55   187.3 1474.71     1931471.782   197.4 1470.74   200.8 1470.68
   227.7 1470.77     2381472.998   251.3 1473.21   258.6 1474.68   274.9 1475.34
   301.9 1474.43   328.9 1474.62   332.3 1473.91     339 1470.81   352.5  1473.8
   369.4 1475.04   406.5 1475.34   433.4  1476.4   470.5 1483.28   511.9 1496.03
#Mann= 3 , 0 , 0
       0      .1       0     193    .045       0     238     .05       0
#XS Ineff= 2 , 0
                          356.96         1480.95
Permanent Ineff=
       F       F
#Block Obstruct= 1 ,-1
   29.51   69.01  1545.4
Bank Sta=193,238
XS Rating Curve= 0 ,0
Exp/Cntr=0.5,0.3

Type RM Length L Ch R = 1 ,6591    ,30.4,30.4,30.3
XS GIS Cut Line= 4
      1993011.93      245758.803     1992975.819      245598.386
     1992967.485      245565.748     1992918.875      245378.942
#Sta/Elev= 30
       0 1548.83    24.7 1535.15    44.9 1522.27    65.1 1510.55   102.1 1491.07
   108.8  1485.1   112.2 1483.33   118.9 1484.19     129 1484.31   149.2 1482.56
   152.5 1481.48   157.4 1478.83   167.51471.455   169.4 1470.21   172.8 1469.16
   182.9 1468.75   189.7 1469.49   196.5 1469.19   211.21471.907   216.8 1472.78
   230.4 1472.54   247.3 1474.38   294.8 1472.38   308.2 1473.15   318.5 1469.93
   324.4 1469.28   335.5 1472.18   352.4 1473.94   379.5 1480.31   391.1 1481.59
#Mann= 3 , 0 , 0
       0      .1       0   167.5    .045       0   211.2     .05       0
#XS Ineff= 3 ,-1
       0     162 1481.91     212     311  1473.4     311     400    1480
Permanent Ineff=
       F       F       F
#Block Obstruct= 2 , 0
                          376.34         1501.59
Bank Sta=167.5,211.2
XS Rating Curve= 0 ,0
Exp/Cntr=0.5,0.3

Type RM Length L Ch R = 3 ,6575    ,,,
BEGIN DESCRIPTION:
Unnamed Road
Survey ID: 54089MAC100
END DESCRIPTION:
Bridge Culvert--1,0,-1,-1, 0
Deck Dist Width WeirC Skew NumUp NumDn MinLoCord MaxHiCord MaxSubmerge Is_Ogee
11,12,2.6,0, 9, 9, , , 0.98, 0, 0,0,,
     131     150     168     172     172     202     202     208     236
1483.9431482.5381481.589 1481.22 1481.221478.6041478.6041477.854  1473.5
                                 1479.521476.904
     131     150     168     172     172     202     202     208     236
1483.9431482.5381481.589 1481.22 1481.221478.6041478.6041477.854  1473.5
                                 1479.521476.904
BR Coef=-1 , 1 , 0 ,, 0 ,,,0.8,0,1.2,0,
WSPro=,,,, 1 ,,,, 0 ,,,, 0 ,,,,-1 ,-1 ,-1 , 0 , 0 , 0 , 0 , 0
BR U #Sta/Elev= 30
       0 1548.83    24.7 1535.15    44.9 1522.27    65.1 1510.55   102.1 1491.07
   108.8  1485.1   112.2 1483.33   118.9 1484.19     129 1484.31   149.2 1482.56
   152.5 1481.48   157.4 1478.83   167.51471.455   169.4 1470.21   172.8 1469.16
   182.9 1468.75   189.7 1469.49   196.5 1469.19   211.21471.907   216.8 1472.78
   230.4 1472.54   247.3 1474.38   294.8 1472.38   308.2 1473.15   318.5 1469.93
   324.4 1469.28   335.5 1472.18   352.4 1473.94   379.5 1480.31   391.1 1481.59
BR U #Mann= 3
       0      .1   167.5     .04   211.2     .05
BR D #Sta/Elev= 30
       0 1555.65    32.2 1536.56    52.7 1523.35    89.4 1502.18    99.8 1494.74
   109.9 1484.58   113.2 1483.97   133.4 1484.01   146.8 1482.94   155.7  1480.3
     167 1478.14   170.61471.911   173.8  1468.9   177.2 1468.59     184 1470.46
   190.7 1468.69   197.5  1469.1   200.9 1470.09   204.7 1472.21   204.9 1472.33
   207.7 1474.09   212.5 1474.72     228 1472.84     244 1472.29   261.9 1473.02
   312.8 1471.87   326.3 1469.54   333.1 1471.65   363.6 1474.53   391.1 1480.62
BR D #Mann= 4
       0      .1   170.6     .04   204.7     .05   204.9     .05
BC Design=,, 0 ,, 0 ,,,,,,
BC Use User HTab Curves=0
BC User HTab FreeFlow(D)= 0