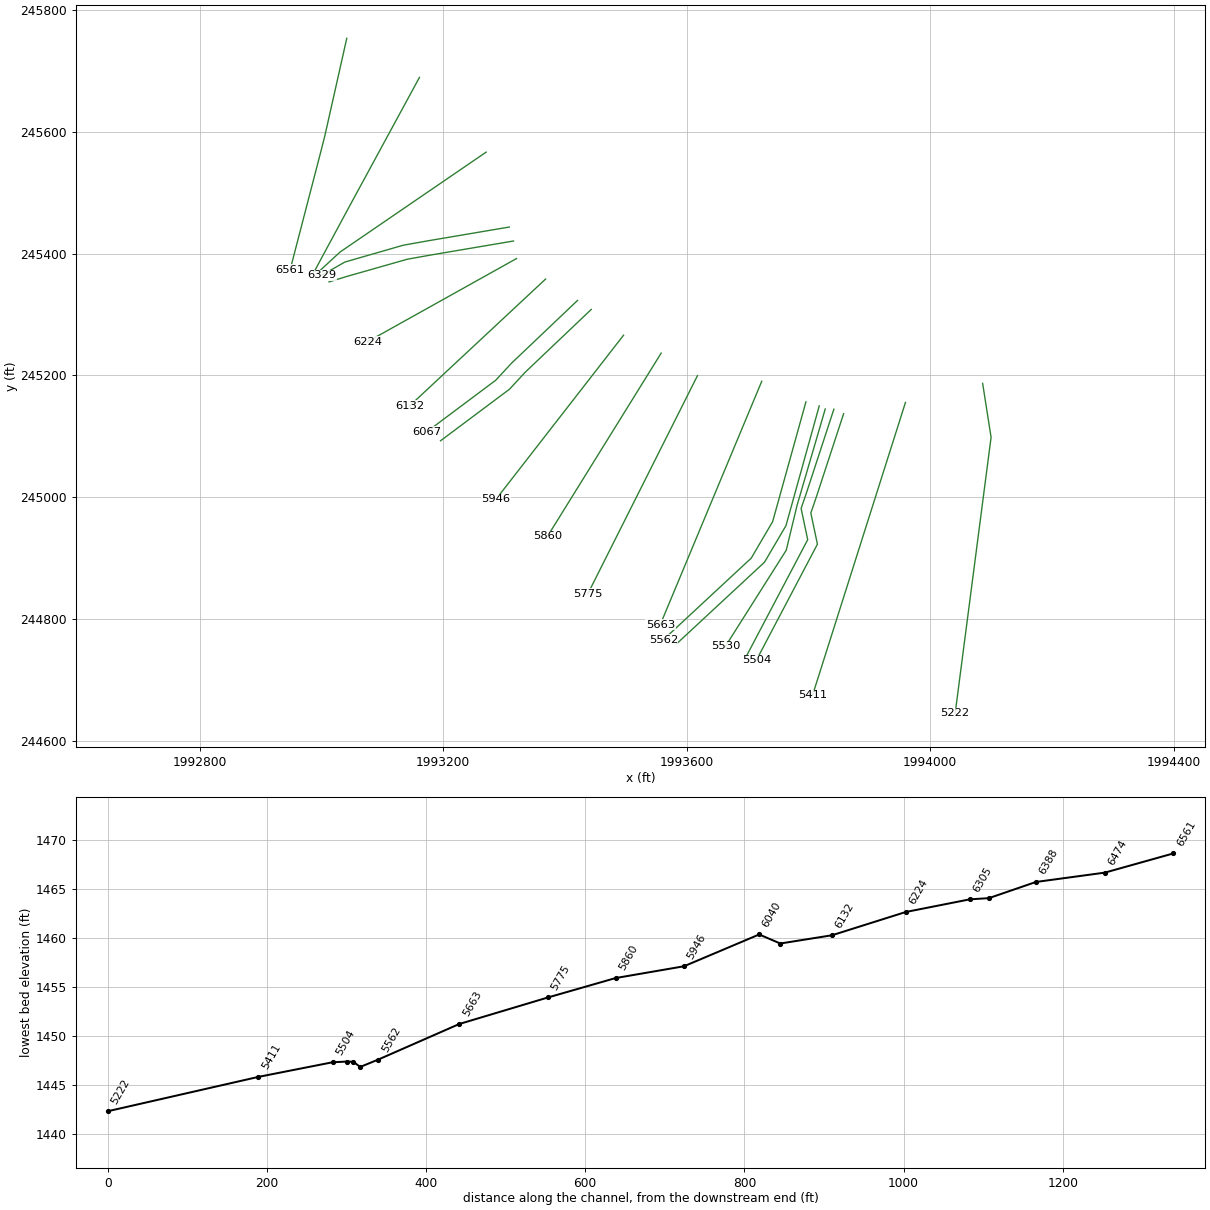
HEC-RAS study MADAMCK.prj: MADAMCK

--- MADAMCK.g01 (geometry) --- (continued)

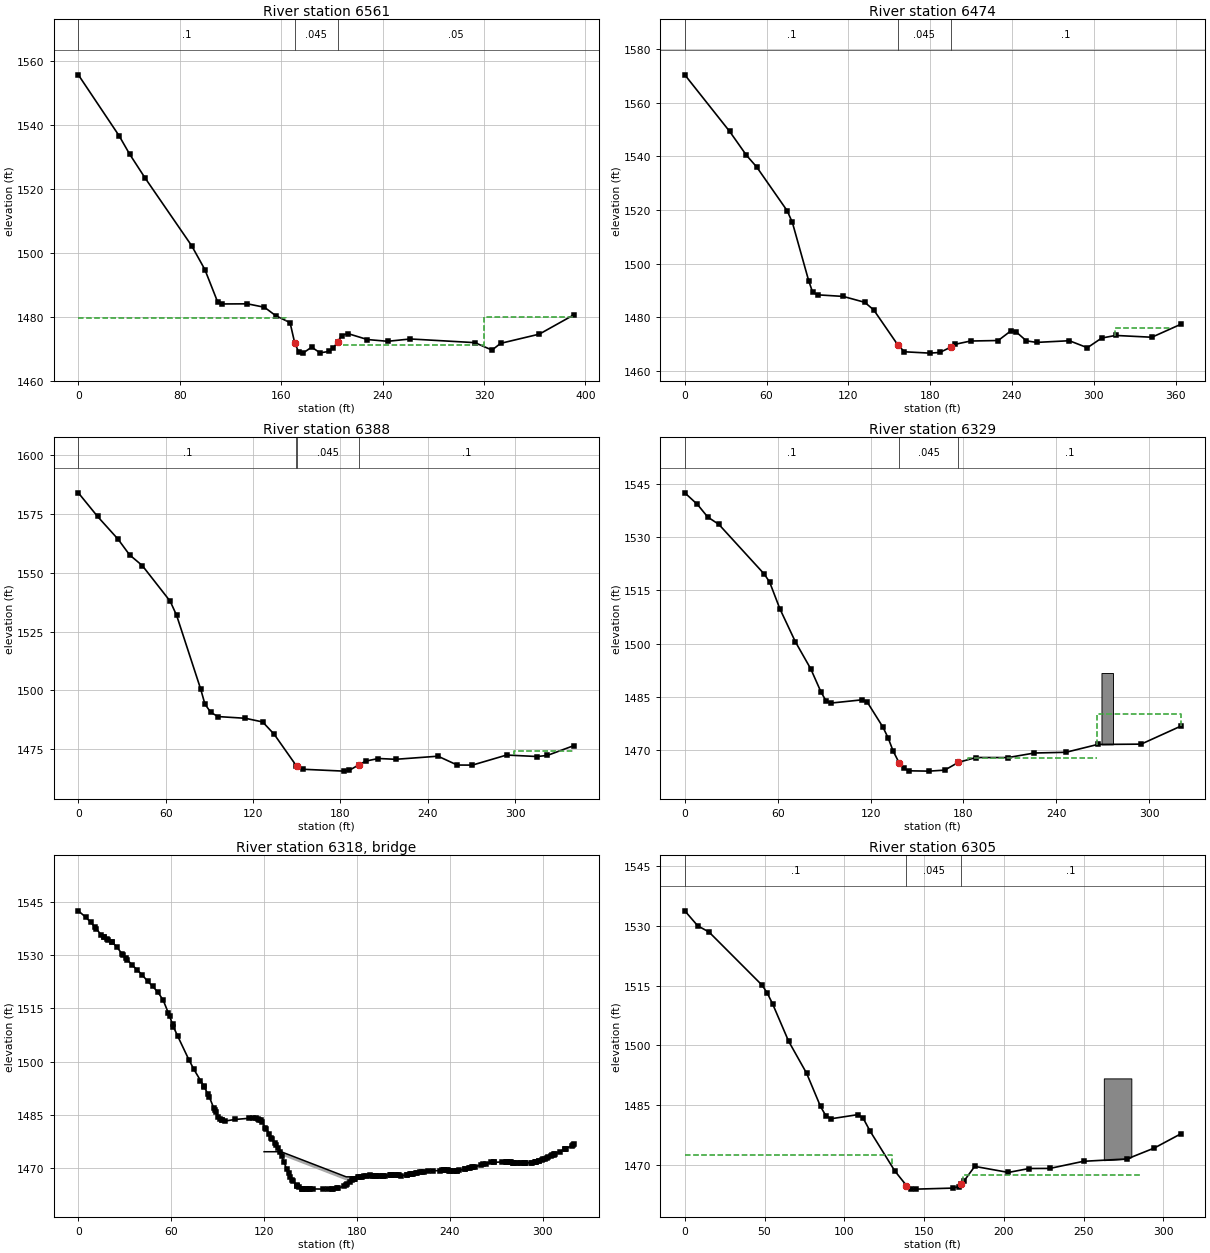
Type RM Length L Ch R = 1 ,6561    ,91.7,86.3,71.5
XS GIS Cut Line= 4
     1993041.791      245753.248      1993005.68      245592.831
     1992997.347      245560.192     1992948.736      245373.387
#Sta/Elev= 30
       0 1555.65    32.2 1536.56    40.4 1530.88    52.7 1523.35    89.4 1502.18
    99.8 1494.74   109.9 1484.58   113.2 1483.97   133.4 1484.01   146.8 1482.94
   155.7  1480.3     167 1478.14   170.61471.911   173.8  1468.9   177.2 1468.59
     184 1470.46   190.7 1468.69   197.5  1469.1   200.9 1470.09   204.7 1472.21
   207.7 1474.09   212.5 1474.72     228 1472.84     244 1472.29   261.9 1473.02
   312.8 1471.87   326.3 1469.54   333.1 1471.65   363.6 1474.53   391.1 1480.62
#Mann= 3 ,-1 , 0
       0      .1       0   170.6    .045       0   204.7     .05       0
#XS Ineff= 3 ,-1
       0     164 1479.52     209     320    1471     320     400    1480
Permanent Ineff=
       F       F       F
#Block Obstruct= 2 , 0
                          372.62         1500.62
Bank Sta=170.6,204.7
XS Rating Curve= 0 ,0
Exp/Cntr=0.5,0.3

Type RM Length L Ch R = 1 ,6474    ,95.5,86.5,61.7
XS GIS Cut Line= 3
     1993161.198      245689.111      1993046.18      245477.523
1992987.83629613245369.389944195
#Sta/Elev= 30
       0 1570.33    32.9 1549.24    45.2 1540.36    52.7 1536.01    75.1 1519.68
    78.9 1515.32    90.9 1493.56    93.8 1489.27    97.5 1488.35   116.2 1487.76
     132 1485.56   138.6 1482.72   156.2 1469.73   161.1 1467.13   179.7 1466.63
   187.1 1466.88   195.31468.914   198.4 1469.93   209.6 1471.14   229.9 1471.33
   239.4 1475.01   243.2 1474.47   250.6 1471.19   258.1 1470.63   282.1 1471.25
   295.3 1468.64   305.8 1472.25     316 1473.22   342.6 1472.55   363.7 1477.35
#Mann= 3 ,-1 , 0
       0      .1       0   156.2    .045       0   195.3      .1       0
#XS Ineff= 1 ,-1
  315.49   356.4 1475.83
Permanent Ineff=
       F
Bank Sta=156.2,195.3
XS Rating Curve= 0 ,0
Exp/Cntr=0.3,0.1

Type RM Length L Ch R = 1 ,6388    ,68.2,59.2,48.1
Node Name=B
XS GIS Cut Line= 3
      1993270.79      245566.498      1993030.99      245402.653
1992994.13483259245368.735839561
#Sta/Elev= 30
       0 1584.07    13.2 1574.02    27.3 1564.33    35.2 1557.67    43.9 1553.13
    63.1 1537.93    67.5 1531.93    84.1 1500.42    86.9 1494.25    90.9  1490.7
    95.9 1488.89   114.7 1488.16   126.6  1486.6   134.6 1481.27   149.7 1467.96
   150.11467.712   154.4 1466.47   182.3 1465.68   186.2 1466.07   192.51468.307
   197.4 1469.95   206.1 1471.05     218 1470.71     247 1472.03   260.2 1468.27
   270.6 1468.24   294.1 1472.52     315  1471.9     322 1472.34   340.5 1476.58
#Mann= 4 ,-1 , 0
       0      .1       0   149.7      .1       0   150.1    .045       0
   192.5      .1       0
#XS Ineff= 2 , 0
                          299.13         1474.42
Permanent Ineff=
       F       F
Bank Sta=150.1,192.5
XS Rating Curve= 0 ,0
Exp/Cntr=0.5,0.3

Type RM Length L Ch R = 1 ,6329    ,23.9,23.9,24.3
XS GIS Cut Line= 5
     1993308.805      245443.526     1993175.472      245420.956
       1993134.5      245413.6641993038.64930288245386.056323913
1993000.65607291245364.372156618
#Sta/Elev= 30
       0 1542.49     8.2  1539.2    14.8 1535.67      22 1533.59    51.4 1519.55
    54.8 1517.32    61.4 1509.81    71.4 1500.52    81.4 1492.83      88 1486.32
    91.4 1483.72    94.7 1483.23   114.7 1484.14     118 1483.39     128 1476.43
   131.3 1473.45   134.6 1469.68   138.41466.417   141.4 1464.91   144.6 1464.12
   157.9 1464.03   167.9 1464.31   176.8 1466.52   188.2 1467.87   208.7 1467.85
   225.9 1469.14   246.2 1469.34   266.7 1471.55   294.8 1471.64   320.3 1476.69
#Mann= 3 , 0 , 0
       0      .1       0   138.4    .045       0   176.8      .1       0
#XS Ineff= 3 ,-1
       0     121 1474.57     183     266 1467.72     266     340    1480
Permanent Ineff=
       F       F       F
#Block Obstruct= 1 ,-1
  269.17  276.59 1491.69
Bank Sta=138.4,176.8
XS Rating Curve= 0 ,0
Exp/Cntr=0.5,0.3

Type RM Length L Ch R = 3 ,6318    ,,,
BEGIN DESCRIPTION:
John Bowling Road
Survey ID: 54089MAC090
END DESCRIPTION:
Bridge Culvert--1,0,-1,-1, 0
Deck Dist Width WeirC Skew NumUp NumDn MinLoCord MaxHiCord MaxSubmerge Is_Ogee
10,12,2.6,0, 6, 6, , , 0.98, 0, 0,0,,
     120     131     131     173     173     185
1474.5741474.5741474.574  1467.5  1467.5  1467.5
                1473.574  1466.5
     120     131     131     173     173     185
1474.5741474.5741474.574  1467.5  1467.5  1467.5
                1473.574  1466.5
BR Coef=-1 , 1 , 0 ,, 0 ,,,0.8,0,1.2,0,
WSPro=,,,, 1 ,,,, 0 ,,,, 0 ,,,,-1 ,-1 ,-1 , 0 , 0 , 0 , 0 , 0
BR U #Sta/Elev= 200
       0 1542.49     4.8 1540.68     8.2  1539.2    10.6 1537.98    11.5  1537.5
    14.8 1535.67    16.3 1535.16    16.8 1535.02    18.2 1534.57    19.1 1534.35
    21.5 1533.78      22 1533.59    24.8 1532.34    28.1 1530.44    28.8 1530.11
    30.5 1529.23    31.5 1528.76    34.8 1527.19    38.1 1525.81    41.4 1524.36
    44.7 1522.66    48.1 1521.16    51.4 1519.55    54.8 1517.32    58.1 1513.79
      59 1512.77    60.9 1510.47    61.4 1509.81    64.1 1507.25    71.4 1500.52
    74.7 1497.76    78.9 1494.63    80.9 1493.19    81.4 1492.83    83.8 1490.74
    84.7 1489.92    87.4 1486.96      88 1486.32    88.9 1485.67    90.3  1484.5
    91.4 1483.72    92.9 1483.48    93.1 1483.43    94.7 1483.23   101.3 1483.67
   110.2 1484.02   112.9  1484.1   114.7 1484.14   115.9 1483.91   116.9 1483.61
     118 1483.39   118.7 1482.94   120.9 1481.33   121.3  1481.1   123.1 1479.67
   124.6 1478.49   124.9 1478.28   127.3  1476.9     128 1476.43     129 1475.52
   130.1 1474.57   131.3 1473.45   132.9 1471.55   134.6 1469.68   135.8 1468.58
     137 1467.55   137.9 1466.67   138.41466.417     141  1465.1   141.3 1464.97
   141.4 1464.91   142.4 1464.64   144.3 1464.18   144.6 1464.12   145.1 1464.11
   147.1 1464.05   147.9 1464.04   149.1 1464.05   149.9 1464.07   151.3 1464.08
   157.9 1464.03   161.3 1464.03   164.1 1464.05   164.6 1464.06   166.9 1464.22
   167.9 1464.31   171.3 1464.86   172.6 1465.21   173.5 1465.53   175.4 1466.08
   176.8 1466.52   177.6 1466.78     178 1466.88   178.1 1466.91   178.7 1466.99
   180.8 1467.34   181.4 1467.37   182.4 1467.46   183.4 1467.57   184.8 1467.65
   186.1 1467.73   188.2 1467.87   188.7 1467.88   190.6  1467.8   191.4 1467.78
   191.6 1467.76     192 1467.75     194 1467.68     195 1467.65   196.7  1467.7
   196.8 1467.71   198.4 1467.77   201.6 1467.96   201.9 1467.98     202 1467.97
   202.5 1467.96   204.6 1467.96   205.3    1468   206.4 1467.95   207.3 1467.94
   208.7 1467.85   212.1 1467.97   212.6 1468.04   214.3 1468.23   215.2 1468.34
   215.5 1468.35     216  1468.4   217.9 1468.61   218.9 1468.69   220.8 1468.77
   222.3 1468.85   223.2 1468.89   225.9 1469.14   229.2 1469.23   233.8 1469.24
   235.2 1469.31     236 1469.33   236.5 1469.33     238 1469.32   239.1 1469.29
   239.4 1469.28     240 1469.26   241.8 1469.23   242.8  1469.2   244.4 1469.26
   244.8 1469.27   246.2 1469.34   249.7 1469.68   249.9 1469.71   252.4 1469.97
   253.1 1470.02   254.4 1470.13     255 1470.17   256.5 1470.33   259.9 1470.87
   261.7 1471.07   263.3 1471.23   266.7 1471.55   268.3  1471.6   268.8  1471.6
   273.6 1471.69   276.2 1471.69   276.6 1471.69     277 1471.68   278.7 1471.62
   279.8 1471.56   280.8 1471.51   281.1  1471.5   281.5 1471.46   283.5 1471.37
   284.6 1471.35   285.9 1471.34   288.1 1471.37   288.3 1471.37   288.3 1471.38
   288.6 1471.38   292.1 1471.48   293.1 1471.52   294.8 1471.64   295.5 1471.73
   295.9 1471.79   297.4 1472.01   297.9 1472.08   299.7 1472.37   300.3 1472.47
   301.4 1472.65   302.7 1472.93   303.5 1473.08   305.1  1473.4   306.2  1473.6
   307.2 1473.79   307.5 1473.85     308 1473.95     311 1474.61   314.6 1475.42
   314.7 1475.44   314.8 1475.46   318.6 1476.26   319.5 1476.49   320.3 1476.69
BR U #Mann= 3
       0      .1   138.4     .04   176.8      .1
BR D #Sta/Elev= 200
       0  1533.8     1.9 1533.08     2.4 1532.83     5.2 1531.33     8.1 1530.04
     8.6 1529.89    11.9 1529.34    13.2    1529    13.8 1528.87    15.2 1528.47
    21.9 1525.51    22.3 1525.31    25.2 1524.22      28 1523.25    31.9 1521.82
    38.5  1519.1    42.3 1517.65    45.2 1516.56    48.5 1515.11    49.2 1514.63
    50.8 1513.74    51.8 1513.08    55.1 1510.39    58.5 1507.49    59.3 1506.65
    61.8  1504.3    65.1 1501.05    67.9  1498.9    68.5 1498.48    71.8 1496.43
    75.1 1494.03    76.4 1492.99    77.3 1492.21    78.4 1491.26    79.3 1490.47
    81.3 1488.36    82.1 1487.56    84.1 1485.64    85.1 1484.67    87.8 1482.74
    88.4 1482.36    89.3 1482.17    90.6 1481.78    91.7 1481.58    95.1 1481.79
    97.3 1482.01    99.2 1482.18   101.7 1482.36   105.1 1482.52   107.7 1482.61
   108.4 1482.61   109.3 1482.36   110.6 1482.18   111.7 1481.82   113.3 1480.63
   113.4 1480.59   116.2 1478.47   117.3 1477.78   118.4 1477.07   119.1 1476.64
   121.9 1474.93   123.4 1473.95   124.8 1473.04   125.4 1472.65   127.6 1471.21
   131.7 1468.47   133.3 1467.49     135 1466.52   135.2 1466.42   136.2 1465.98
   137.4 1465.47   138.3 1465.05     139  1464.8   141.7 1463.96   141.8 1463.95
     145 1463.91   148.3 1463.97   151.7 1464.05     155  1464.1     156 1464.11
   158.3  1464.1   158.8  1464.1   161.4 1464.12   161.6 1464.12   161.7 1464.12
     165 1464.19   168.3 1464.17   169.8 1464.35   170.1  1464.4   171.7 1464.56
   172.9 1465.19   173.9 1465.44     175 1465.91   175.8 1466.45   176.8 1467.08
   178.1 1467.73   178.4 1467.87   178.5 1467.91   178.9 1468.13   181.1 1469.38
   181.8 1469.62   182.9 1469.58   183.8 1469.55   185.2 1469.49   186.5  1469.3
   188.6 1468.94   189.1 1468.89   190.9 1468.78   191.8 1468.77   195.4 1468.62
   197.1 1468.57   197.2 1468.56   198.8 1468.46   199.7 1468.36     202 1468.15
   202.2 1468.12   202.9  1468.1     205  1468.2   205.6 1468.24   206.7  1468.3
   207.7 1468.34   209.1 1468.43   210.4 1468.59   211.5 1468.75   212.5 1468.88
     213 1468.91   214.9 1469.04   215.7 1469.08   215.9 1469.09   216.3 1469.09
   218.3 1469.04   219.3 1469.02     221 1469.02   222.7 1469.04   223.6 1469.04
   225.8 1469.07   226.1 1469.08   226.3 1469.08   226.9 1469.08   228.9 1469.11
   229.5 1469.15   230.6 1469.24   231.6 1469.31   232.9 1469.45   234.3 1469.59
   235.3 1469.73   236.3 1469.84   236.9 1469.91   238.9  1470.2   239.6 1470.28
   239.8 1470.29   240.1 1470.32   242.2 1470.48   243.2 1470.54   246.6 1470.65
   247.5 1470.69   249.6 1470.87     250  1470.9   250.2  1470.9   250.9 1470.92
   252.9 1470.92   253.4 1470.91   254.4 1470.88   255.5 1470.83   256.8 1470.82
   258.2 1470.91   259.2 1470.98   260.2 1471.05   260.8 1471.07   262.9 1471.08
   263.5  1471.1   263.6  1471.1   263.9 1471.11   266.1 1471.17     267 1471.19
   268.7 1471.28   270.5 1471.35   271.4  1471.4   273.4 1471.45   273.9 1471.46
   274.1 1471.47   274.9 1471.48   276.8 1471.49   277.3 1471.49   278.2 1471.58
   279.4 1471.66     280 1471.72   280.7 1471.79   287.6  1473.1     291 1473.61
   292.5 1473.88   294.4 1474.23   295.2 1474.38   297.6 1474.87   304.7 1476.32
   305.7 1476.54   308.1 1477.14   308.3 1477.18   308.8 1477.29   310.9 1477.77
BR D #Mann= 3
       0      .1     139     .04   172.9      .1
BC Design=,, 0 ,, 0 ,,,,,,
BC Use User HTab Curves=0
BC User HTab FreeFlow(D)= 0

Type RM Length L Ch R = 1 ,6305    ,72.8,80.5,89.5
XS GIS Cut Line= 5
     1993315.749      245420.609     1993182.416      245398.039
     1993141.444      245390.7481993042.22866877245362.534776662
1993012.71345275245353.472599236
#Sta/Elev= 30
       0  1533.8     8.1 1530.04    15.2 1528.47    48.5 1515.11    51.8 1513.08
    55.1 1510.39    65.1 1501.05    76.4 1492.99    85.1 1484.67    88.4 1482.36
    91.7 1481.58   108.4 1482.61   111.7 1481.82   116.2 1478.47   131.7 1468.47
     139  1464.8   141.7 1463.96     145 1463.91   168.3 1464.17   171.7 1464.56
   172.9 1465.19     175 1465.91   181.8 1469.62   202.9  1468.1   215.9 1469.09
   228.9 1469.11     250  1470.9   277.3 1471.49   294.4 1474.23   310.9 1477.77
#Mann= 3 ,-1 , 0
       0      .1       0     139    .045       0   172.9      .1       0
#XS Ineff= 2 ,-1
       0 129.667 1472.38 174.333   286.2  1467.4
Permanent Ineff=
       F       F
#Block Obstruct= 1 ,-1
  262.74  279.99 1491.72
Bank Sta=139,172.9
XS Rating Curve= 0 ,0
Exp/Cntr=0.5,0.3

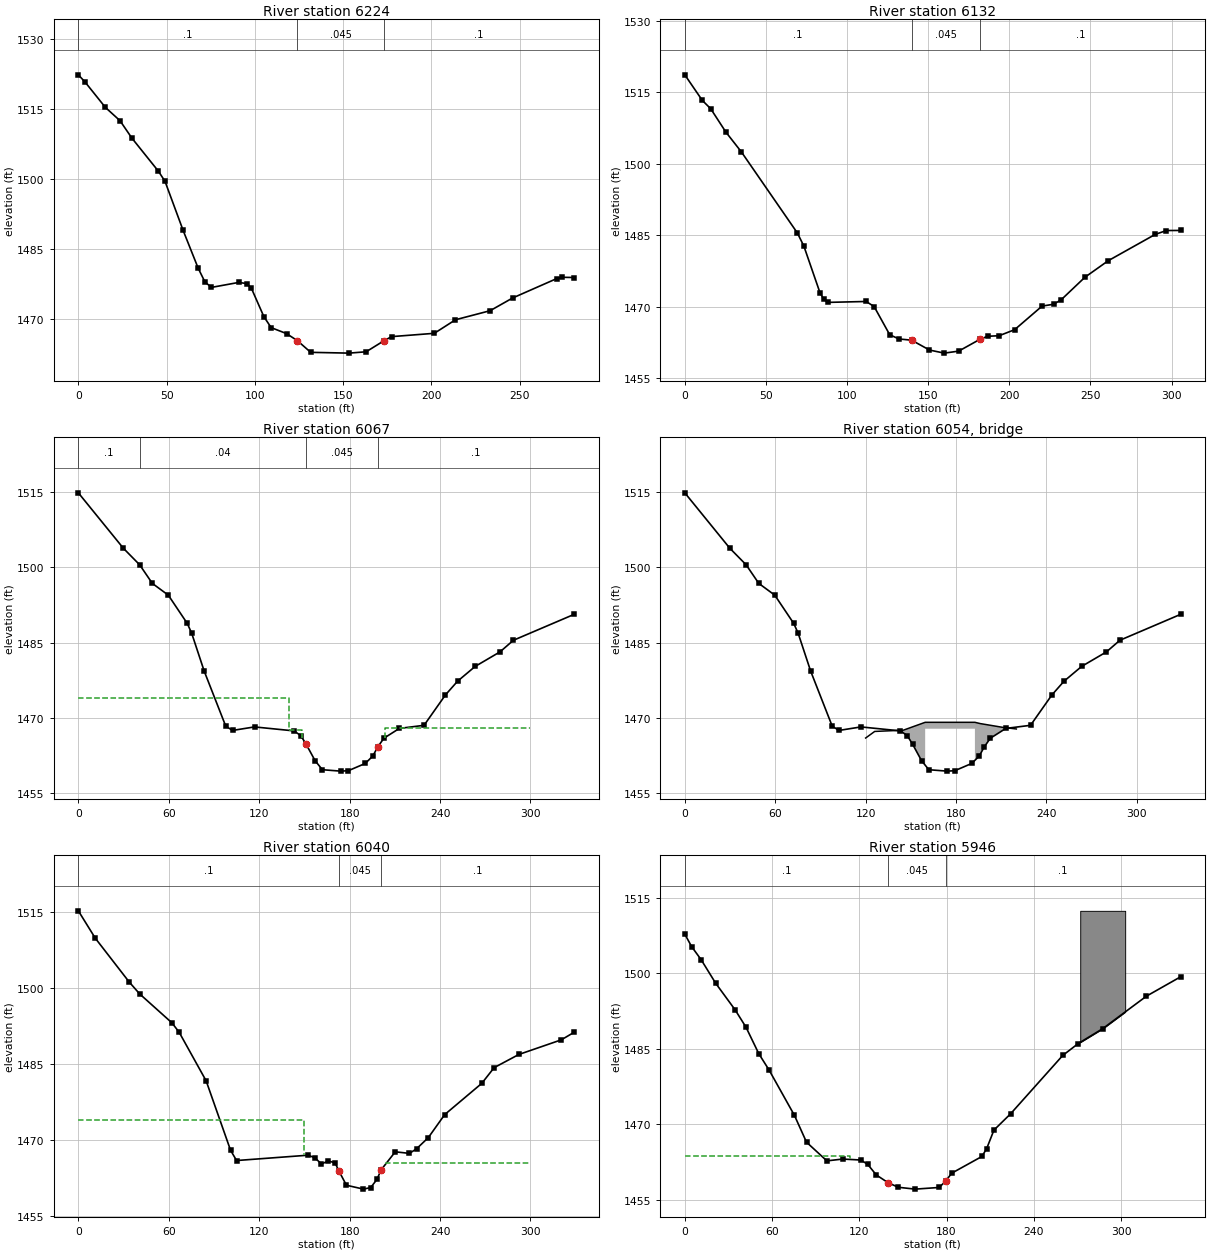
Type RM Length L Ch R = 1 ,6224    ,86.2,92.7,100.5
XS GIS Cut Line= 2
     1993320.703      245391.802     1993075.477      245255.083
#Sta/Elev= 30
       0 1522.32     3.8 1520.78    15.3 1515.34    23.6 1512.48    30.4 1508.71
    45.4 1501.62    49.1 1499.46    59.3 1488.99    67.9 1480.81    71.7 1477.89
    75.4 1476.72    90.9 1477.79    95.5 1477.53      98 1476.54   105.1 1470.43
   109.2 1468.09   117.9 1466.81   124.11465.282   131.6 1462.79   153.3 1462.62
     163 1462.91     1731465.255   177.4 1466.16   201.6 1466.87   213.6 1469.78
   233.2 1471.72   245.9 1474.44   270.8 1478.59   273.9 1478.89   280.8 1478.84
#Mann= 3 ,-1 , 0
       0      .1       0   124.1    .045       0     173      .1       0
Bank Sta=124.1,173
XS Rating Curve= 0 ,0
Exp/Cntr=0.3,0.1

Type RM Length L Ch R = 1 ,6132    ,62.8,64.9,64.1
XS GIS Cut Line= 2
     1993368.446      245358.165     1993144.922      245149.832
#Sta/Elev= 30
       0 1518.66    10.8 1513.29      16 1511.53    25.3 1506.65    34.9 1502.47
    69.4 1485.46    73.4  1482.7    83.3 1472.94    85.6 1471.59    88.1  1470.9
   111.8 1471.09   116.7 1470.02   126.3 1464.11     132 1463.22   139.81462.969
   150.8  1460.9   159.9 1460.25   168.8 1460.67     1821463.167   186.7 1463.79
   193.7  1463.9   203.3 1465.17   220.2 1470.12   227.3 1470.51   231.9 1471.42
   246.6 1476.17     261 1479.65   289.9 1485.16   296.8 1485.98   305.6    1486
#Mann= 3 ,-1 , 0
       0      .1       0   139.8    .045       0     182      .1       0
Bank Sta=139.8,182
XS Rating Curve= 0 ,0
Exp/Cntr=0.5,0.3

Type RM Length L Ch R = 1 ,6067    ,26.3,26.6,26.3
XS GIS Cut Line= 5
     1993420.867      245323.027      1993312.36      245219.945
     1993286.572      245192.104      1993254.02      245167.798
     1993173.291      245107.469
#Sta/Elev= 30
       0 1514.81    29.9 1503.77    40.7 1500.48    49.1 1496.78    59.7 1494.44
    72.3  1488.8    75.2 1486.87    83.5 1479.33    97.8 1468.37   102.3 1467.51
   116.9 1468.21   143.1 1467.42   147.6 1466.48   151.2 1464.74   157.1 1461.49
  161.93 1459.69  173.99 1459.41  179.13 1459.49   190.4 1460.94   195.4 1462.42
   198.6 1464.18   202.7 1465.95     213 1467.91   229.4 1468.53   243.6 1474.58
   251.6  1477.3   263.3 1480.25   279.8 1483.15   288.7 1485.46     329 1490.62
#Mann= 4 ,-1 , 0
       0      .1       0    40.7     .04       0   151.2    .045       0
   198.6      .1       0
#XS Ineff= 3 ,-1
       0     140    1474     140   148.5 1467.56   203.5     300 1467.96
Permanent Ineff=
       F       F       F
#Block Obstruct= 2 , 0
                          314.01         1510.62
Bank Sta=151.2,198.6
XS Rating Curve= 0 ,0
Exp/Cntr=0.5,0.3

Type RM Length L Ch R = 3 ,6054    ,,,
BEGIN DESCRIPTION:
Reed Martin Drive
Survey ID: 54089MAC080
END DESCRIPTION:
Bridge Culvert--1,0,-1,-1, 0
Deck Dist Width WeirC Skew NumUp NumDn MinLoCord MaxHiCord MaxSubmerge Is_Ogee
11,10,2.6,0, 12, 13, , , 0.98, 0, 0,0,,
     120     126     145   159.5   159.5     164     180   192.5   192.5     196
     211     220
    1466 1467.311467.5581469.1271469.1271469.1271469.1271469.1271469.1271468.877
1468.122  1467.8
                                1467.8541467.8541467.8541467.854
                
     120     126     145     164   168.5   168.5     180   192.5     196   201.5
   201.5     211     220
    1466 1467.311467.5581469.1271469.1271469.1271469.1271469.1271469.1271469.127
1469.1271468.122  1467.5
                                        1467.8541467.8541467.8541467.8541467.854
                        
BR Coef=-1 , 1 , 0 ,, 0 ,,,0.8,0,1.2,0,
WSPro=,,,, 1 ,,,, 0 ,,,, 0 ,,,,-1 ,-1 ,-1 , 0 , 0 , 0 , 0 , 0
BR U #Sta/Elev= 30
       0 1514.81    29.9 1503.77    40.7 1500.48    49.1 1496.78    59.7 1494.44
    72.3  1488.8    75.2 1486.87    83.5 1479.33    97.8 1468.37   102.3 1467.51
   116.9 1468.21   143.1 1467.42   147.6 1466.48   151.2 1464.74   157.1 1461.49
  161.93 1459.69  173.99 1459.41  179.13 1459.49   190.4 1460.94   195.4 1462.42
   198.6 1464.18   202.7 1465.95     213 1467.91   229.4 1468.53   243.6 1474.58
   251.6  1477.3   263.3 1480.25   279.8 1483.15   288.7 1485.46     329 1490.62
BR U #Mann= 4
       0      .1    40.7     .04   151.2     .04   198.6      .1
BR D #Sta/Elev= 30
       0 1515.22    11.3  1509.8    33.7  1501.2    40.7 1498.83    62.1 1493.13
    66.9 1491.27    84.8 1481.69     101    1468     105 1465.97   152.4 1467.02
   156.9 1466.53   161.3 1465.29   165.8 1465.87   170.3 1465.54     173 1463.85
  177.89  1461.1   189.2 1460.33     194 1460.64   198.1 1462.23     201 1464.17
   210.3 1467.69   219.7 1467.38   224.4 1468.28   232.2 1470.48   243.1 1475.03
   267.7 1481.19   275.9 1484.29   292.3 1486.89   320.5 1489.78     329 1491.27
BR D #Mann= 3
       0      .1     173     .04     201      .1
BC Design=,, 0 ,, 0 ,,,,,,
BC Use User HTab Curves=0
BC User HTab FreeFlow(D)= 0

Type RM Length L Ch R = 1 ,6040    ,89.9,94.5,99.2
XS GIS Cut Line= 5
     1993443.437       245308.27      1993334.93      245205.188
     1993309.142      245177.347     1993276.589      245153.041
      1993195.86      245092.712
#Sta/Elev= 30
       0 1515.22    11.3  1509.8    33.7  1501.2    40.7 1498.83    62.1 1493.13
    66.9 1491.27    84.8 1481.69     101    1468     105 1465.97   152.4 1467.02
   156.9 1466.53   161.3 1465.29   165.8 1465.87   170.3 1465.54     173 1463.85
  177.89  1461.1   189.2 1460.33     194 1460.64   198.1 1462.23     201 1464.17
   210.3 1467.69   219.7 1467.38   224.4 1468.28   232.2 1470.48   243.1 1475.03
   267.7 1481.19   275.9 1484.29   292.3 1486.89   320.5 1489.78     329 1491.27
#Mann= 3 ,-1 , 0
       0      .1       0     173    .045       0     201      .1       0
#XS Ineff= 3 ,-1
       0     150    1474     150 166.167  1465.4 203.833     300  1465.4
Permanent Ineff=
       F       F       F
#Block Obstruct= 2 , 0
                          320.34         1511.27
Bank Sta=173,201
XS Rating Curve= 0 ,0
Exp/Cntr=0.5,0.3

Type RM Length L Ch R = 1 ,5946    ,82.5,85.9,88.4
XS GIS Cut Line= 2
     1993496.484      245265.934     1993287.066      244996.837
#Sta/Elev= 30
       0 1507.81     4.7 1505.32    11.2 1502.74    21.3 1498.01    34.6 1492.75
    42.1 1489.29    50.9 1484.02      58 1480.76    75.4 1471.76    83.7 1466.43
    97.7 1462.71   108.6 1463.07   121.1 1462.88   125.8 1462.01   131.7 1459.91
   139.8 1458.37   146.8 1457.46   158.4 1457.09   174.9 1457.42   179.5  1458.7
   183.5 1460.25   204.3 1463.58   207.6 1465.14   212.6 1468.83     224 1472.05
   259.9 1483.67   270.6 1486.05   287.4    1489   317.5 1495.47     341 1499.32
#Mann= 3 ,-1 , 0
       0      .1       0   139.8    .045       0   179.5      .1       0
#XS Ineff= 2 , 0
          113.77 1463.72
Permanent Ineff=
       F       F
#Block Obstruct= 1 ,-1
  271.95  302.87 1512.44
Bank Sta=139.8,179.5
XS Rating Curve= 0 ,0
Exp/Cntr=0.3,0.1

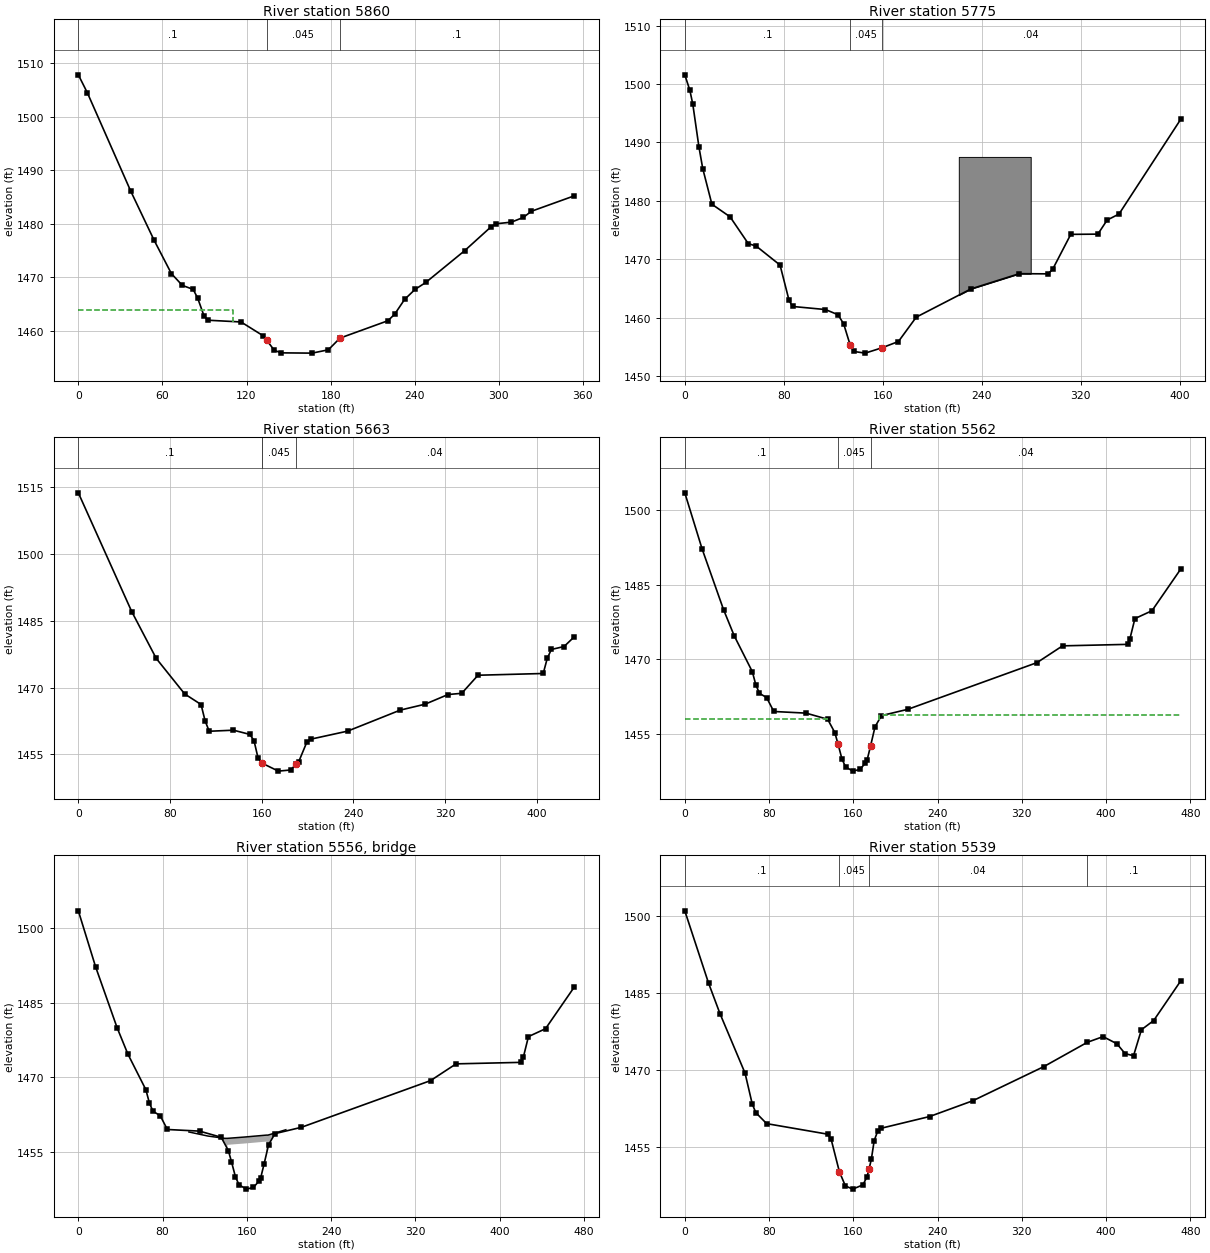
Type RM Length L Ch R = 1 ,5860    ,82.2,84.7,88.4
XS GIS Cut Line= 2
     1993558.333      245236.637     1993371.701      244936.073
#Sta/Elev= 30
       0 1507.78     6.5  1504.4    37.4 1486.09    54.1 1476.92    66.4 1470.72
    74.2 1468.52    81.9 1467.78    85.1 1466.19    89.6 1462.89    92.2 1462.03
   116.1  1461.7   132.1 1459.09   134.31458.349   139.8 1456.42   144.7 1455.94
   166.8 1455.89   178.4 1456.51   186.7 1458.69   220.9 1461.93   225.7 1463.14
   232.8  1465.9   240.2 1467.76   247.9 1469.06   275.7    1475   294.7 1479.49
   298.1 1480.01     309 1480.31   317.5 1481.19   323.3 1482.34   353.8 1485.21
#Mann= 3 , 0 , 0
       0      .1       0   134.3    .045       0   186.7      .1       0
#XS Ineff= 2 , 0
          110.65 1463.94
Permanent Ineff=
       F       F
Bank Sta=134.3,186.7
XS Rating Curve= 0 ,0
Exp/Cntr=0.3,0.1

Type RM Length L Ch R = 1 ,5775    ,110.4,111.7,113.3
XS GIS Cut Line= 2
     1993618.012      245199.745     1993437.891      244841.672
#Sta/Elev= 30
       0 1501.56     4.1 1498.91     6.5 1496.49    11.4 1489.25    14.5 1485.52
    21.9 1479.41    36.6 1477.25    51.3 1472.67    57.8 1472.23      77 1468.99
    84.3 1462.93    87.1 1461.91   113.7 1461.38   123.8  1460.5   128.4 1458.94
   133.61455.357   136.5 1454.21   145.8 1453.92   159.31454.826   172.7 1455.91
   187.1 1460.08   231.3 1464.91   270.4 1467.52   293.6 1467.49   297.3 1468.25
     312 1474.25   333.9 1474.29   341.4  1476.7     351 1477.73   400.8 1493.92
#Mann= 3 , 0 , 0
       0      .1       0   133.6    .045       0   159.3     .04       0
#Block Obstruct= 1 ,-1
  221.48  279.61 1487.51
Bank Sta=133.6,159.3
XS Rating Curve= 0 ,0
Exp/Cntr=0.3,0.1

Type RM Length L Ch R = 1 ,5663    ,98.2,101.7,103.1
XS GIS Cut Line= 2
     1993723.553      245190.413     1993556.886      244791.108
#Sta/Elev= 30
       0 1513.75    46.6 1487.06      68 1476.53    92.8 1468.56   107.1 1466.18
   110.6 1462.53   114.2 1460.17   135.4 1460.41   149.7 1459.46   153.3 1458.07
   156.8 1454.19   160.4    1453   160.61452.962   174.6 1451.21   185.3 1451.47
   190.11452.803   192.4 1453.37   199.5 1457.78     203  1458.4     235  1460.2
   280.9 1464.92   302.6 1466.25   322.6 1468.42   334.6  1468.7   348.8 1472.76
   405.7 1473.15   409.2 1476.53   412.8 1478.55   423.9 1479.21   432.7 1481.37
#Mann= 4 ,-1 , 0
       0      .1       0   160.4     .04       0   160.6    .045       0
   190.1     .04       0
Bank Sta=160.6,190.1
XS Rating Curve= 0 ,0
Exp/Cntr=0.5,0.3

Type RM Length L Ch R = 1 ,5562    ,22.9,22.8,22.9
XS GIS Cut Line= 4
     1993796.121       245156.62     1993741.433      244960.006
     1993706.277       244900.11     1993561.745      244765.995
#Sta/Elev= 30
       0 1503.44    16.4  1492.2    36.8 1479.99      47 1474.71    64.1 1467.55
    67.5 1464.85    70.9 1463.21    77.7 1462.34    84.5 1459.56   115.1 1459.23
   135.6    1458   142.4 1455.34   145.4 1453.08   149.2 1450.02   152.6 1448.45
   159.51447.591  166.24 1447.93   171.3 1449.16     173 1449.76   176.4 1452.69
   180.6  1456.5   186.7 1458.73   211.8    1460   334.4 1469.37   358.6 1472.73
   420.3 1473.03   422.6 1474.18   427.3  1478.2   443.5 1479.78   470.7 1488.11
#Mann= 3 , 0 , 0
       0      .1       0   145.4    .045       0   176.4     .04       0
#XS Ineff= 2 , 0
           135.5 1458.01   184.5         1458.82
Permanent Ineff=
       F       F
Bank Sta=145.4,176.4
XS Rating Curve= 0 ,0
Exp/Cntr=0.5,0.3

Type RM Length L Ch R = 3 ,5556    ,,,
BEGIN DESCRIPTION:
Unnamed Road
Survey ID: 54089MAC070
END DESCRIPTION:
Bridge Culvert--1,0,-1,-1, 0
Deck Dist Width WeirC Skew NumUp NumDn MinLoCord MaxHiCord MaxSubmerge Is_Ogee
6,13,2.6,0, 10, 10, , , 0.98, 0, 0,0,,
     105     123     139   141.5   141.5     158   178.5   178.5     180     197
1459.0591458.2441457.7821457.7821457.782 1458.051458.4321458.4321458.4321459.506
                                1456.482 1456.751457.132
     105     123     139   141.5   141.5     158   178.5   178.5     180     197
1459.0591458.2441457.7821457.7821457.782 1458.051458.4321458.4321458.4321459.506
                                1456.482 1456.751457.132
BR Coef=-1 , 1 , 0 ,, 0 ,,,0.8,0,1.2,0,
WSPro=,,,, 1 ,,,, 0 ,,,, 0 ,,,,-1 ,-1 ,-1 , 0 , 0 , 0 , 0 , 0
BR U #Sta/Elev= 30
       0 1503.44    16.4  1492.2    36.8 1479.99      47 1474.71    64.1 1467.55
    67.5 1464.85    70.9 1463.21    77.7 1462.34    84.5 1459.56   115.1 1459.23
   135.6    1458   142.4 1455.34   145.4 1453.08   149.2 1450.02   152.6 1448.45
   159.51447.591  166.24 1447.93   171.3 1449.16     173 1449.76   176.4 1452.69
   180.6  1456.5   186.7 1458.73   211.8    1460   334.4 1469.37   358.6 1472.73
   420.3 1473.03   422.6 1474.18   427.3  1478.2   443.5 1479.78   470.7 1488.11
BR U #Mann= 3
       0      .1   145.4     .04   176.4     .04
BR D #Sta/Elev= 30
       0 1501.08    22.5 1487.02    33.4 1481.04    57.2 1469.44      64 1463.45
    67.4 1461.75    77.7  1459.6   135.5 1457.55   138.9 1456.57   146.71450.266
   152.4 1447.47   159.41446.834  169.17 1447.67     173 1449.27   174.91450.745
   177.1 1452.67   179.8  1456.3   183.2 1458.18   186.6 1458.71   232.5 1460.99
   273.3 1464.05   340.6 1470.69   382.2 1475.46   397.1 1476.56   410.2 1475.17
     418 1473.24     426 1472.84   433.5 1477.91   445.1 1479.69   470.7 1487.39
BR D #Mann= 4
       0      .1   146.7     .04   174.9     .04   382.2      .1
BC Design=,, 0 ,, 0 ,,,,,,
BC Use User HTab Curves=0
BC User HTab FreeFlow(D)= 0

Type RM Length L Ch R = 1 ,5539    ,9,8.8,9.1
XS GIS Cut Line= 4
     1993817.996      245150.023     1993763.308      244953.408
     1993728.152      244893.513      1993583.62      244759.398
#Sta/Elev= 30
       0 1501.08    22.5 1487.02    33.4 1481.04    57.2 1469.44      64 1463.45
    67.4 1461.75    77.7  1459.6   135.5 1457.55   138.9 1456.57   146.71450.266
   152.4 1447.47   159.41446.834  169.17 1447.67     173 1449.27   174.91450.745
   177.1 1452.67   179.8  1456.3   183.2 1458.18   186.6 1458.71   232.5 1460.99
   273.3 1464.05   340.6 1470.69   382.2 1475.46   397.1 1476.56   410.2 1475.17
     418 1473.24     426 1472.84   433.5 1477.91   445.1 1479.69   470.7 1487.39
#Mann= 4 ,-1 , 0
       0      .1       0   146.7    .045       0   174.9     .04       0
   382.2      .1       0
#XS Ineff= 2 , 0
           138.5  1454.9   181.5          1455.7
Permanent Ineff=
       F       F
Bank Sta=146.7,174.9
XS Rating Curve= 0 ,0
Exp/Cntr=0.5,0.3

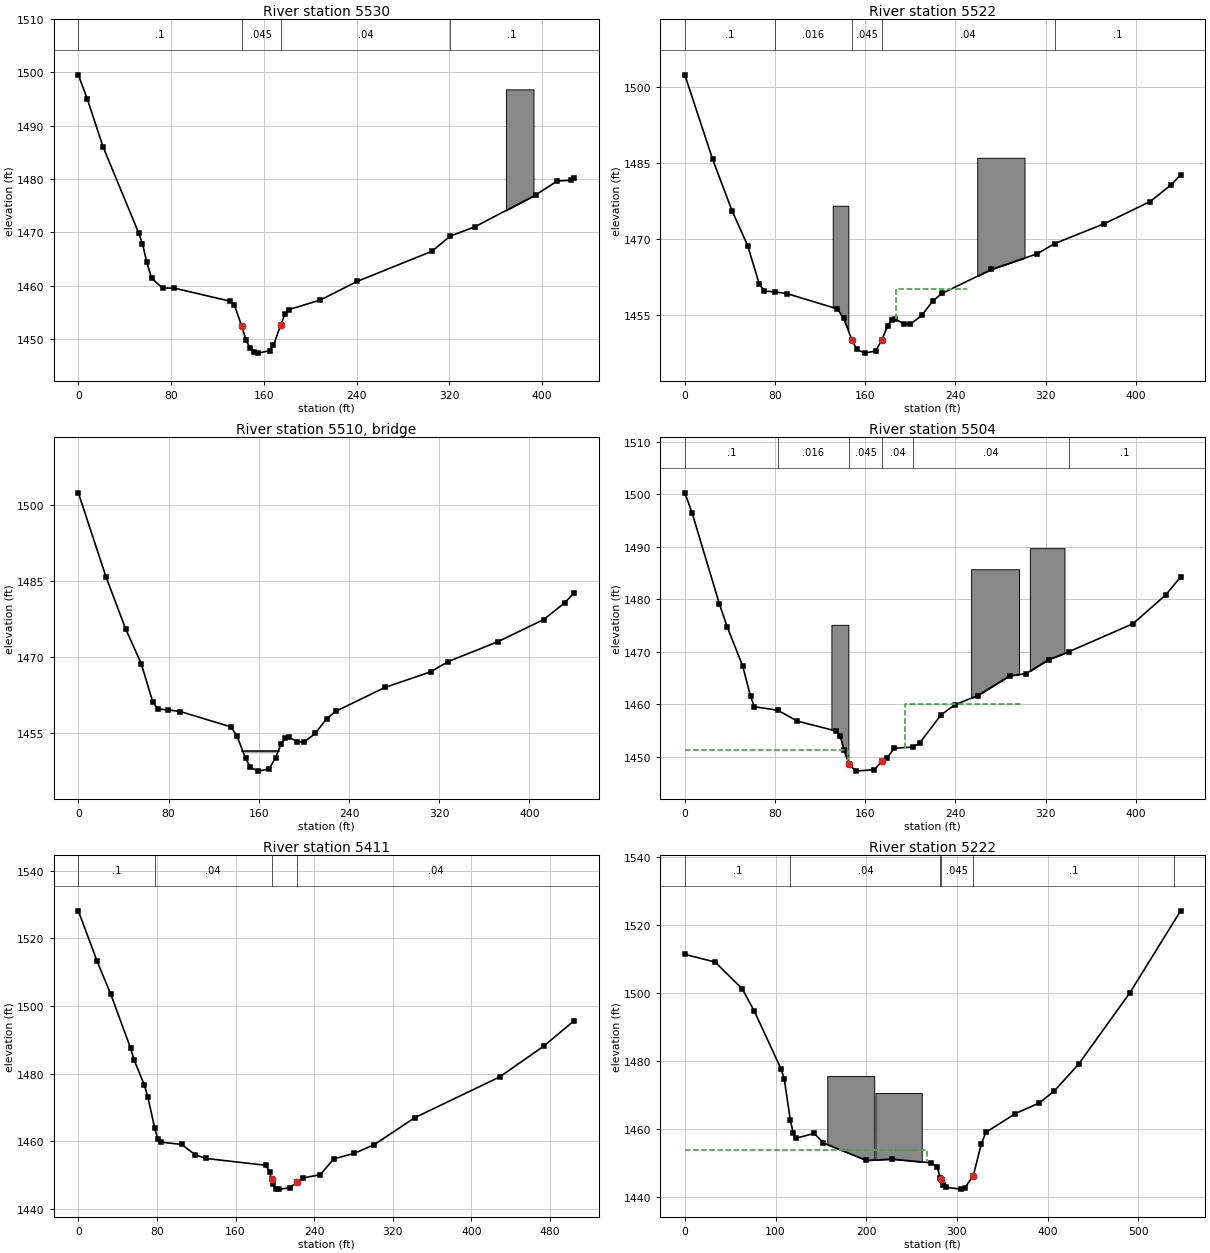
Type RM Length L Ch R = 1 ,5530    ,9.1,8.4,12.9
XS GIS Cut Line= 4
     1993827.855      245144.902     1993781.501      244986.568
     1993763.793      244913.131     1993663.706      244755.101
#Sta/Elev= 30
       0 1499.56     7.7 1495.04    21.3 1486.06    52.1 1469.88    55.3 1467.88
    58.9 1464.53    63.2  1461.4    72.6 1459.57    82.9 1459.54   130.7 1457.11
   134.6 1456.34     141 1452.37   144.4 1449.91   147.8 1448.41   151.2 1447.56
   154.7 1447.36   164.9  1447.8   168.3 1448.84   174.5 1452.63   178.4 1454.79
   181.8 1455.54   208.8 1457.33   240.5 1460.82     305 1466.47   320.5 1469.28
   342.1 1471.07   394.7 1477.06     413 1479.65   425.3 1479.78   427.6 1480.22
#Mann= 4 ,-1 , 0
       0      .1       0     141    .045       0   174.5     .04       0
  320.52      .1       0
#Block Obstruct= 1 ,-1
  368.75  392.56 1496.83
Bank Sta=141,174.5
XS Rating Curve= 0 ,0
Exp/Cntr=0.5,0.3

Type RM Length L Ch R = 1 ,5522    ,17.5,17.6,16.1
XS GIS Cut Line= 5
     1993842.041      245144.598     1993796.866      245006.794
     1993788.185       244981.62     1993799.036      244930.405
     1993698.558       244739.65
#Sta/Elev= 30
       0 1502.42    24.7  1485.7    41.9 1475.53    55.8 1468.61    66.1 1460.98
    70.6 1459.66    79.9 1459.49    90.3 1459.17   135.2 1456.14   140.8 1454.26
   148.31449.905   152.5 1448.13   159.4 1447.38   169.2 1447.81   174.91450.068
   179.9  1452.8   183.3 1453.84   186.6  1454.1   194.3 1453.18   200.1 1453.12
   210.1 1454.84   220.2 1457.78   228.2  1459.2   271.7 1463.92   312.5 1467.03
   327.8 1469.04   371.8 1472.96   412.6 1477.36   431.1 1480.65   439.6 1482.63
#Mann= 5 ,-1 , 0
       0      .1       0    79.9    .016       0   148.3    .045       0
   174.9     .04       0   327.8      .1       0
#XS Ineff= 3 ,-1
       0   145.1  1451.4   182.9     187  1451.4     187     250    1460
Permanent Ineff=
       F       F       F
#Block Obstruct= 2 ,-1
  131.17  145.02 1476.53  259.29  301.17 1486.02
Bank Sta=148.3,174.9
XS Rating Curve= 0 ,0
Exp/Cntr=0.5,0.3

Type RM Length L Ch R = 3 ,5510    ,,,
BEGIN DESCRIPTION:
Private Driveway
Owner denied access to the bridge
Assumed bridge thickness of 0.5 ft based on imagery
END DESCRIPTION:
Bridge Culvert--1,0,-1,-1, 0
Deck Dist Width WeirC Skew NumUp NumDn MinLoCord MaxHiCord MaxSubmerge Is_Ogee
8,5,2.6,0, 2, 2, , , 0.98, 0, 0,0,,
     145     178
  1451.4  1451.4
  1450.9  1450.9
     145     185
  1451.4  1451.4
  1450.9  1450.9
BR Coef=-1 , 1 , 0 ,, 0 ,,,0.8,0,1.2,0,
WSPro=,,,, 1 ,,,, 0 ,,,, 0 ,,,,-1 ,-1 ,-1 , 0 , 0 , 0 , 0 , 0
BR U #Sta/Elev= 30
       0 1502.42    24.7  1485.7    41.9 1475.53    55.8 1468.61    66.1 1460.98
    70.6 1459.66    79.9 1459.49    90.3 1459.17   135.2 1456.14   140.8 1454.26
   148.31449.905   152.5 1448.13   159.4 1447.38   169.2 1447.81   174.91450.068
   179.9  1452.8   183.3 1453.84   186.6  1454.1   194.3 1453.18   200.1 1453.12
   210.1 1454.84   220.2 1457.78   228.2  1459.2   271.7 1463.92   312.5 1467.03
   327.8 1469.04   371.8 1472.96   412.6 1477.36   431.1 1480.65   439.6 1482.63
BR U #Mann= 5
       0      .1    79.9    .016   148.3     .04   174.9     .04   327.8      .1
BR D #Sta/Elev= 30
       0 1500.26     6.5 1496.42    30.6 1479.17    37.5  1474.8    51.4 1467.25
    58.3 1461.52    61.7 1459.56    82.4  1458.9    99.7 1456.83   134.2 1454.94
   137.7 1454.08   141.1 1451.29   145.7 1448.63   151.5 1447.31   168.1  1447.6
   174.91449.229     179 1449.72   185.7 1451.67   202.5 1451.89   208.4 1452.71
   227.2 1458.02   239.4 1459.92   259.6 1461.68     288 1465.43   302.5 1465.86
   322.6 1468.52   340.3 1470.01   397.3 1475.35   426.5 1480.86   439.6 1484.25
BR D #Mann= 6
       0      .1    82.4    .016   145.7     .04   174.9     .04   202.5     .04
   340.3      .1
BC Design=,, 0 ,, 0 ,,,,,,
BC Use User HTab Curves=0
BC User HTab FreeFlow(D)= 0

Type RM Length L Ch R = 1 ,5504    ,92.7,93.2,88.8
XS GIS Cut Line= 5
     1993858.013      245137.133     1993812.838      244999.329
     1993804.157      244974.155     1993815.008       244922.94
     1993714.531      244732.185
#Sta/Elev= 30
       0 1500.26     6.5 1496.42    30.6 1479.17    37.5  1474.8    51.4 1467.25
    58.3 1461.52    61.7 1459.56    82.4  1458.9    99.7 1456.83   134.2 1454.94
   137.7 1454.08   141.1 1451.29   145.7 1448.63   151.5 1447.31   168.1  1447.6
   174.91449.229     179 1449.72   185.7 1451.67   202.5 1451.89   208.4 1452.71
   227.2 1458.02   239.4 1459.92   259.6 1461.68     288 1465.43   302.5 1465.86
   322.6 1468.52   340.3 1470.01   397.3 1475.35   426.5 1480.86   439.6 1484.25
#Mann= 6 ,-1 , 0
       0      .1       0    82.4    .016       0   145.7    .045       0
   174.9     .04       0   202.5     .04       0   340.3      .1       0
#XS Ineff= 3 ,-1
       0   145.1  1451.4     185     195  1451.4     195     300    1460
Permanent Ineff=
       F       F       F
#Block Obstruct= 3 ,-1
  129.99  145.02 1475.15  253.85  296.27 1485.72  305.94  336.62 1489.73
Bank Sta=145.7,174.9
XS Rating Curve= 0 ,0
Exp/Cntr=0.5,0.3

Type RM Length L Ch R = 1 ,5411    ,185.4,189.3,192.8
XS GIS Cut Line= 2
     1993959.664      245155.691     1993806.887      244674.788
#Sta/Elev= 30
       0 1528.18    19.2  1513.2    32.8 1503.66    53.2 1487.51    56.9 1483.94
    67.2 1476.62    70.7 1473.16    77.6    1464      81 1460.58    84.4 1459.72
   105.1 1459.04   118.9    1456   129.6 1454.91   191.2 1452.86   194.6 1450.81
   196.61448.765     198 1447.31   201.5 1445.94   204.7 1445.82   215.3 1446.19
   222.41447.863     229 1449.16   246.2 1450.07     260 1454.79   280.7 1456.38
   301.2 1458.98   342.6    1467   428.7 1479.01   473.4 1488.08   504.6 1495.66
#Mann= 4 ,-1 , 0
       0      .1       0    77.6     .04       0   196.6    .045       0
   222.4     .04       0
Bank Sta=196.6,222.4
XS Rating Curve= 0 ,0
Exp/Cntr=0.3,0.1

Type RM Length L Ch R = 1 ,5222    ,162,165.6,167.6
XS GIS Cut Line= 3
     1994086.401      245186.941     1994100.289      245098.399
     1994041.262      244645.274
#Sta/Elev= 30
       0 1511.47    33.4  1509.2    63.3 1501.32    76.6 1494.77   106.4 1477.57
   109.7 1474.65   116.3  1462.7   119.6 1458.83   122.9 1457.35   142.8 1458.72
   152.7 1455.94   200.2 1450.78   228.8 1451.15   271.8 1450.06   278.4 1448.73
   281.7 1445.53   282.2 1445.24   285.1 1443.56   288.4 1442.81   304.9 1442.32
   308.5 1442.62   318.1  1446.3   326.9  1455.7   331.9 1459.05   364.5 1464.57
   390.9 1467.72   407.5 1471.26   434.4 1479.23   490.5  1500.1   546.6 1524.29
#Mann= 6 ,-1 , 0
       0      .1       0   116.3     .04       0   281.7     .04       0
   282.2    .045       0   318.1      .1       0  539.62     .12       0
#XS Ineff= 2 , 0
           266.7 1453.94
Permanent Ineff=
       F       F
#Block Obstruct= 2 ,-1
  157.08  208.83 1475.62  210.17  261.25 1470.64
Bank Sta=282.2,318.1
XS Rating Curve= 0 ,0
Exp/Cntr=0.3,0.1