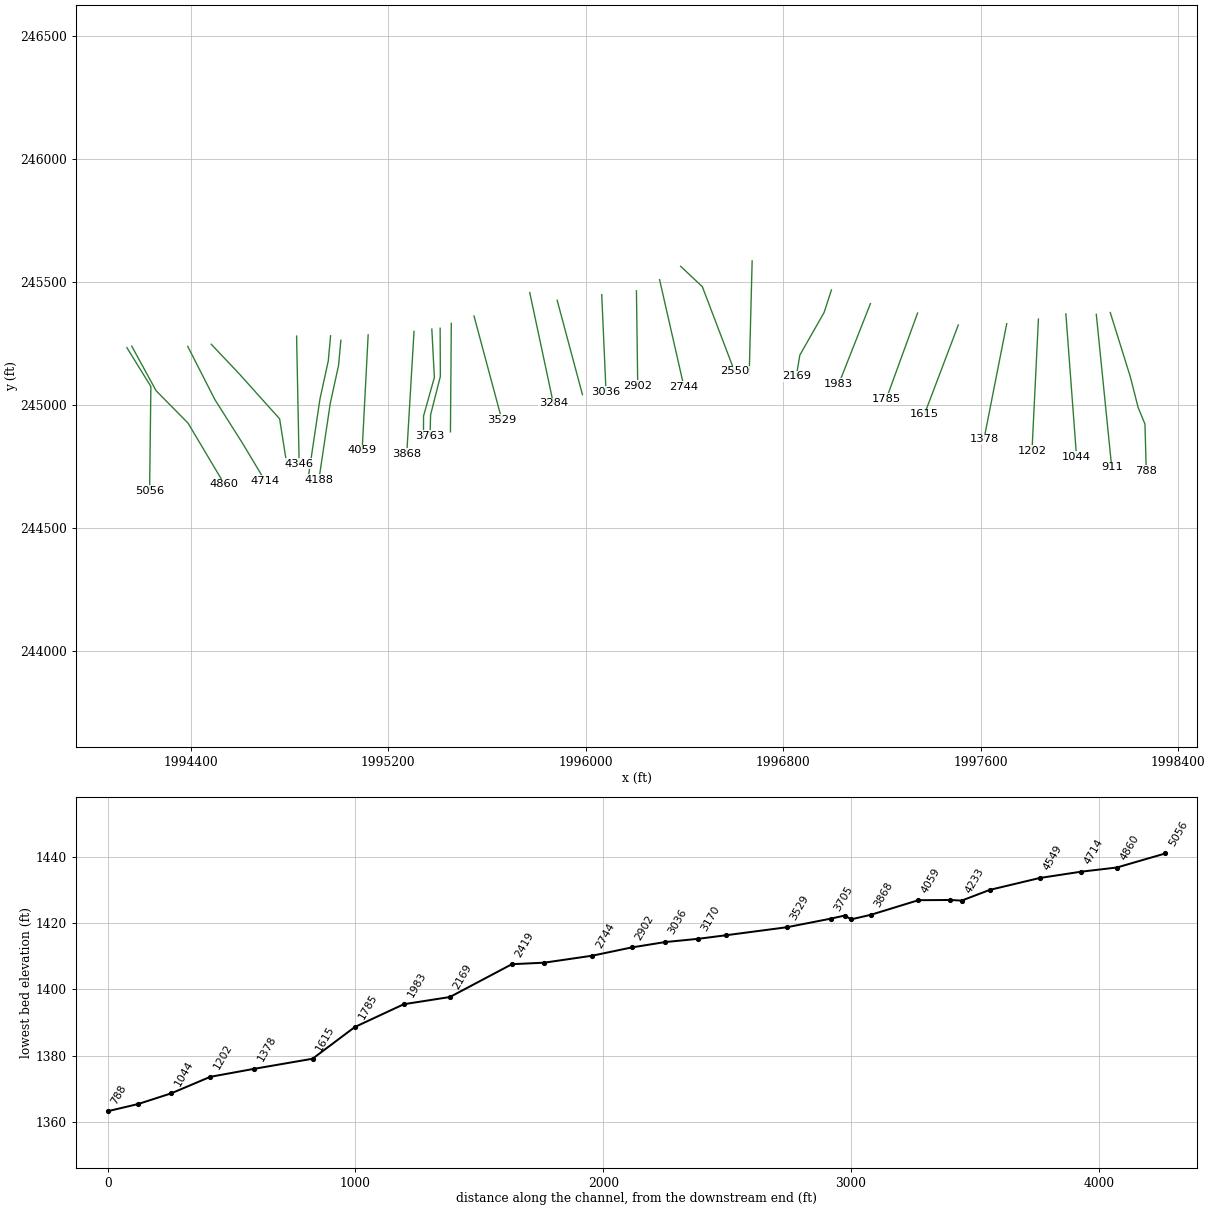
HEC-RAS study MADAMCK.prj: MADAMCK

--- MADAMCK.g01 (geometry) --- (continued)

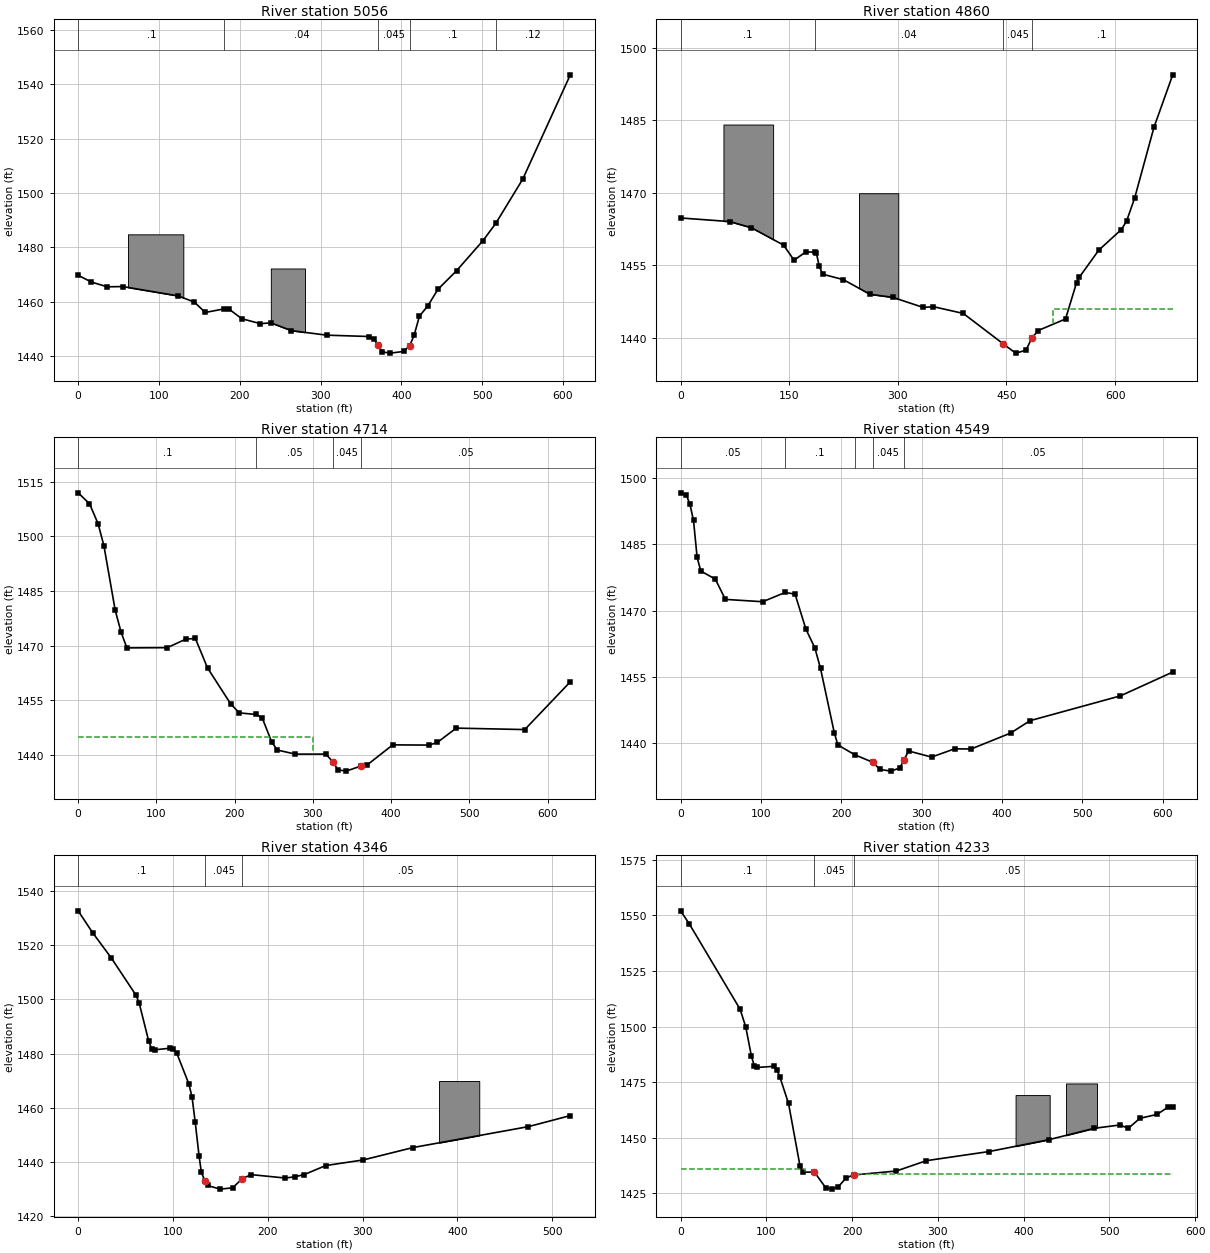
Type RM Length L Ch R = 1 ,5056    ,172.8,196.3,209.2
XS GIS Cut Line= 3
     1994141.956      245233.816     1994239.178       245075.83
      1994233.97      244652.219
#Sta/Elev= 30
       0 1469.72    16.3 1467.23      36 1465.47    55.3 1465.56   123.9 1462.12
   143.9 1459.83   157.3 1456.04   181.1 1457.37   186.1  1457.4   202.6 1453.72
   225.5 1451.92   238.6 1452.21     264 1449.35   307.5 1447.69     360 1447.19
   366.6 1446.15   371.31444.031   376.4 1441.53   386.3 1441.08   402.7 1441.69
   410.4 1443.86   415.8 1447.66   422.4 1454.69   432.6 1458.39   445.3 1464.54
   468.4 1471.41   501.1 1482.48   516.8 1488.76   550.3  1505.1   609.1 1543.43
#Mann= 5 ,-1 , 0
       0      .1       0   181.1     .04       0   371.3    .045       0
   410.4      .1       0   516.8     .12       0
#Block Obstruct= 2 ,-1
   61.66  130.15 1484.77  238.46  280.72 1472.21
Bank Sta=371.3,410.4
XS Rating Curve= 0 ,0
Exp/Cntr=0.3,0.1

Type RM Length L Ch R = 1 ,4860    ,145.4,145.8,146.2
XS GIS Cut Line= 4
     1994161.632      245239.892     1994260.373      245058.686
     1994389.497      244927.392     1994537.066      244678.911
#Sta/Elev= 30
       0 1464.81      68 1464.06    97.9 1462.78   142.2 1459.19   156.7 1456.06
   172.6 1457.75   185.7 1457.75   187.5 1457.55   191.3 1454.91   196.1 1453.16
   224.6 1452.05   261.4 1449.01     293 1448.37     335 1446.28     349 1446.44
   390.3 1445.04   445.71438.717   462.6 1436.82   476.9 1437.41   484.71439.864
   493.7  1441.5   531.5 1443.89   546.7  1451.4   550.6 1452.55   577.5 1458.16
   608.6 1462.41   615.8 1464.16   626.9 1468.91   653.6 1483.58   679.5 1494.45
#Mann= 4 ,-1 , 0
       0      .1       0   185.7     .04       0   445.7    .045       0
   484.7      .1       0
#XS Ineff= 2 , 0
                          513.86         1445.92
Permanent Ineff=
       F       F
#Block Obstruct= 2 ,-1
    59.2  127.79 1484.16  246.29  300.57 1469.93
Bank Sta=445.7,484.7
XS Rating Curve= 0 ,0
Exp/Cntr=0.3,0.1

Type RM Length L Ch R = 1 ,4714    ,156.3,165,165.2
XS GIS Cut Line= 4
     1994388.484      245239.024     1994497.859      245023.747
     1994610.706      244844.927     1994700.984      244693.885
#Sta/Elev= 30
       0 1511.96    14.5 1508.98    25.5 1503.45    32.9 1497.46    47.3 1479.77
    54.9 1473.65    62.3 1469.38   113.8 1469.44   137.6 1471.78   149.8 1471.97
   165.3 1463.89   194.8 1454.04   205.9 1451.53   227.9 1451.09   235.3  1450.1
   247.3 1443.56   254.5 1441.33   277.6 1440.21   316.4 1440.22     3261437.992
   331.9 1435.92   342.4 1435.54   361.81436.965   368.6 1437.12     402 1442.75
   448.3 1442.69     459 1443.42   483.1 1447.35   570.7 1446.95   628.9 1460.06
#Mann= 4 ,-1 , 0
       0      .1       0   227.9     .05       0     326    .045       0
   361.8     .05       0
#XS Ineff= 2 , 0
             300    1445
Permanent Ineff=
       F       F
Bank Sta=326,361.8
XS Rating Curve= 0 ,0
Exp/Cntr=0.3,0.1

Type RM Length L Ch R = 1 ,4549    ,215.3,202.5,160
XS GIS Cut Line= 4
1994483.58561934      245247.705     1994595.081      245129.649
1994760.70727785244944.5812778471994792.05911383244745.135144431
#Sta/Elev= 30
       0 1496.68     7.1 1496.21    11.6 1494.12    16.1 1490.43    20.6 1482.05
    25.2 1478.96    43.2 1477.15    55.8 1472.55   102.2 1472.02   130.1 1474.11
   142.5 1473.75     156 1465.82   167.2 1461.54   174.2 1456.91   191.4  1442.3
   195.8 1439.59   216.81437.362   239.2 1435.67   248.4 1434.03   261.9 1433.66
     273 1434.38   277.9 1436.16   283.9 1438.22   312.4 1436.84   341.1 1438.71
   361.6 1438.67   410.7 1442.27   435.1 1445.09   547.5  1450.7   612.6 1456.09
#Mann= 5 ,-1 , 0
       0     .05       0   130.1      .1       0   216.8    .045       0
   239.2    .045       0   277.9     .05       0
#Block Obstruct= 2 , 0
                          581.38         1476.09
Bank Sta=239.2,277.9
XS Rating Curve= 0 ,0
Exp/Cntr=0.3,0.1

Type RM Length L Ch R = 1 ,4346    ,117.9,113,101.7
XS GIS Cut Line= 2
     1994829.456      245280.691     1994839.873      244761.594
#Sta/Elev= 30
       0  1532.7    15.2 1524.67    34.9 1515.36    61.1 1501.54    64.4 1498.67
    74.3 1484.84    77.5 1481.76    80.8 1481.45    97.2 1482.03   100.5 1481.76
   103.8 1480.42   116.9 1468.75   120.2 1463.92   123.5 1454.74   127.6 1442.19
     130 1436.22   133.9    1433   136.6 1431.39   149.7 1430.05   162.9 1430.52
   173.11433.883   182.5  1435.4   218.6 1434.14   228.5  1434.6   238.3 1435.39
   261.3 1438.75   300.7 1440.81   353.2 1445.38   475.1 1453.11   519.2 1457.17
#Mann= 3 , 0 , 0
       0      .1       0   133.9    .045       0   173.1     .05       0
#Block Obstruct= 1 ,-1
  380.72  423.16 1469.92
Bank Sta=133.9,173.1
XS Rating Curve= 0 ,0
Exp/Cntr=0.5,0.3

Type RM Length L Ch R = 1 ,4233    ,44.8,45,44.9
XS GIS Cut Line= 4
     1994967.127      245282.141     1994957.839      245179.971
     1994924.159      245025.631     1994878.152      244715.735
#Sta/Elev= 30
       0 1552.06    10.1 1546.23    69.4 1507.78      76 1499.82    82.6 1486.69
    85.9 1482.41    89.2 1481.56   109.1  1482.1   112.4 1480.42   115.8 1477.27
   125.9 1465.36   139.3 1437.18   142.7 1434.49   156.1 1434.47   169.2 1427.47
  176.19 1426.82  183.59 1427.73     193 1431.86   201.9  1433.2   251.5 1434.96
   286.7 1439.63   359.7 1443.73   429.3 1449.05   482.4 1454.19   512.3 1455.69
   522.2  1454.2   535.5 1458.66   555.4 1460.43   568.5  1463.7   573.9 1463.77
#Mann= 3 , 0 , 0
       0      .1       0   156.1    .045       0   201.9     .05       0
#XS Ineff= 2 , 0
             145 1435.86     207         1433.61
Permanent Ineff=
       F       F
#Block Obstruct= 2 ,-1
  390.64  430.42 1469.15  449.48  485.65 1474.37
Bank Sta=156.1,201.9
XS Rating Curve= 0 ,0
Exp/Cntr=0.5,0.3

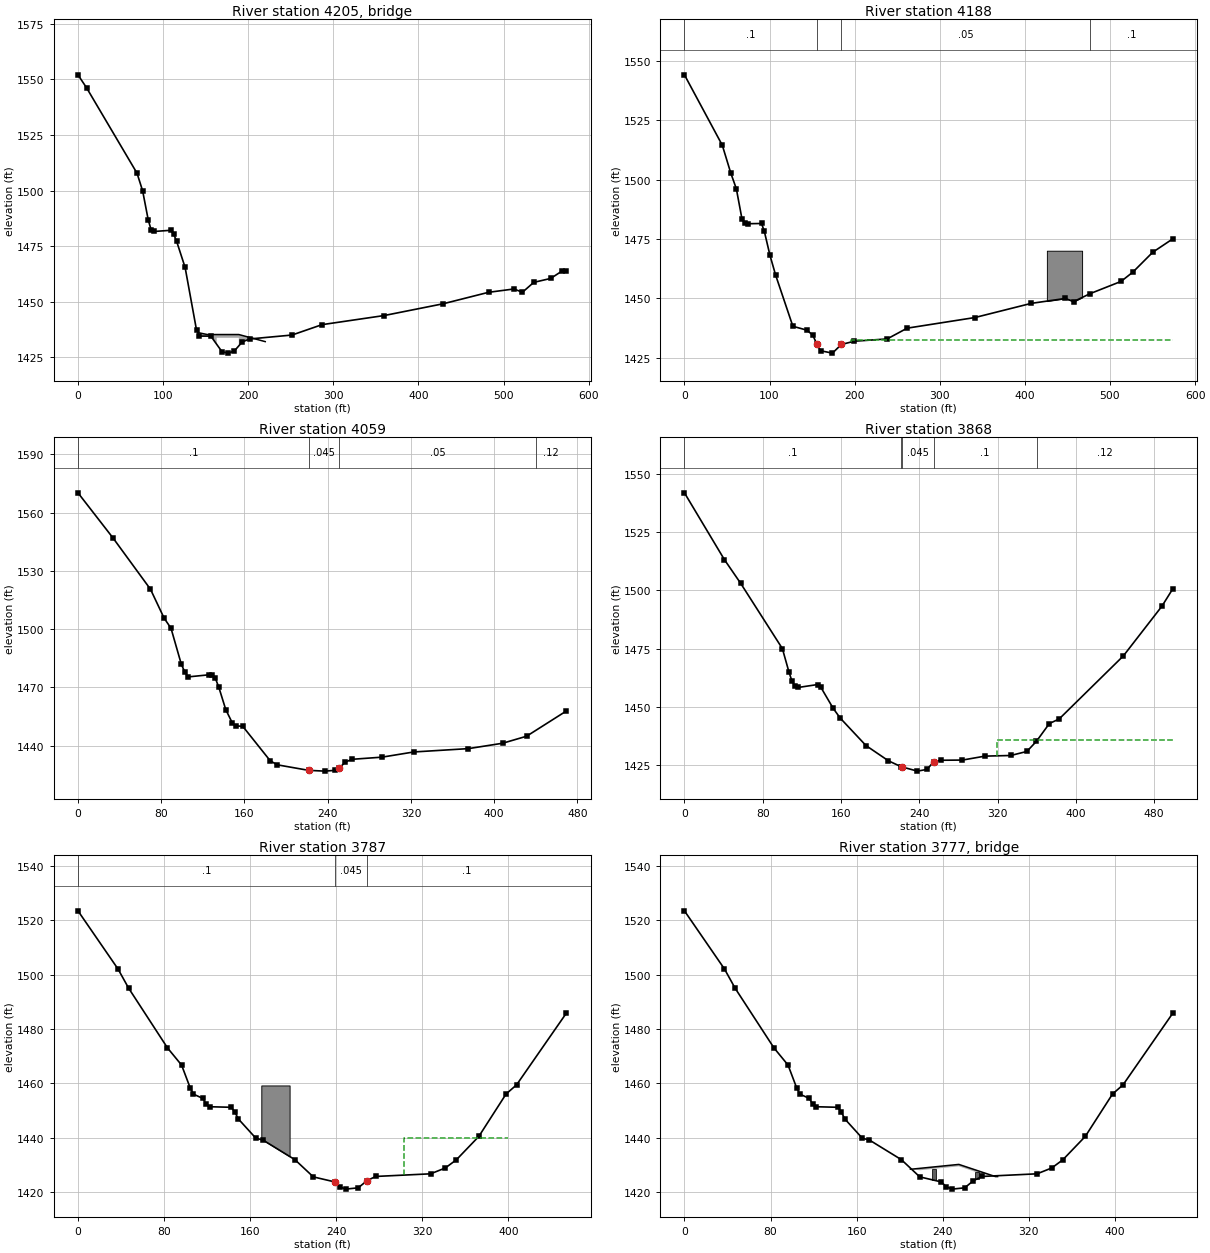
Type RM Length L Ch R = 3 ,4205    ,,,
BEGIN DESCRIPTION:
Private Driveway
Survey ID: 54089MAC050
END DESCRIPTION:
Bridge Culvert--1,0,-1,-1, 0
Deck Dist Width WeirC Skew NumUp NumDn MinLoCord MaxHiCord MaxSubmerge Is_Ogee
18,11,2.6,0, 9, 9, , , 0.98, 0, 0,0,,
     141     152     163     163     172     182     189     189     220
1436.0581435.1871435.1871435.1871435.1871435.1871435.1871435.187    1432
                        1433.7191433.7191433.7191433.719
     141     152     157     157     172     182     183     183     220
1436.0581435.1871435.1871435.1871435.1871435.1871435.1871435.187    1432
                        1433.7191433.7191433.7191433.719
BR Coef=-1 , 1 , 0 ,, 0 ,,,0.8,0,1.2,0,
WSPro=,,,, 1 ,,,, 0 ,,,, 0 ,,,,-1 ,-1 ,-1 , 0 , 0 , 0 , 0 , 0
BR U #Sta/Elev= 30
       0 1552.06    10.1 1546.23    69.4 1507.78      76 1499.82    82.6 1486.69
    85.9 1482.41    89.2 1481.56   109.1  1482.1   112.4 1480.42   115.8 1477.27
   125.9 1465.36   139.3 1437.18   142.7 1434.49   156.1 1434.47   169.2 1427.47
  176.19 1426.82  183.59 1427.73     193 1431.86   201.9  1433.2   251.5 1434.96
   286.7 1439.63   359.7 1443.73   429.3 1449.05   482.4 1454.19   512.3 1455.69
   522.2  1454.2   535.5 1458.66   555.4 1460.43   568.5  1463.7   573.9 1463.77
BR U #Mann= 3
       0      .1   156.1     .04   201.9     .05
BR D #Sta/Elev= 30
       0 1544.05    44.5 1514.43    54.4  1502.8      61 1496.12    67.6 1483.47
    70.9 1481.73    74.2 1481.43    90.6 1481.53    93.9  1478.2   100.5 1468.13
   107.2 1459.77   127.4 1438.31   144.1 1436.64   150.9  1434.5   155.4 1430.95
  159.99 1428.01   173.91427.011   184.4 1430.65   199.6 1432.02   238.2 1432.98
   261.7 1437.51   341.3 1441.98   407.4 1447.93   447.4    1450   457.4  1448.7
   476.7 1452.04     513 1457.17     527 1461.12   550.2 1469.43   573.9  1475.1
BR D #Mann= 4
       0      .1   155.4     .04   184.4     .05   476.7      .1
BC Design=,, 0 ,, 0 ,,,,,,
BC Use User HTab Curves=0
BC User HTab FreeFlow(D)= 0

Type RM Length L Ch R = 1 ,4188    ,122.2,129.4,134.4
XS GIS Cut Line= 4
     1995008.794      245263.912     1994999.506      245161.742
     1994965.825      245007.401     1994919.818      244697.506
#Sta/Elev= 30
       0 1544.05    44.5 1514.43    54.4  1502.8      61 1496.12    67.6 1483.47
    70.9 1481.73    74.2 1481.43    90.6 1481.53    93.9  1478.2   100.5 1468.13
   107.2 1459.77   127.4 1438.31   144.1 1436.64   150.9  1434.5   155.4 1430.95
  159.99 1428.01   173.91427.011   184.4 1430.65   199.6 1432.02   238.2 1432.98
   261.7 1437.51   341.3 1441.98   407.4 1447.93   447.4    1450   457.4  1448.7
   476.7 1452.04     513 1457.17     527 1461.12   550.2 1469.43   573.9  1475.1
#Mann= 4 ,-1 , 0
       0      .1       0   155.4    .045       0   184.4     .05       0
   476.7      .1       0
#XS Ineff= 2 , 0
        151.6667  1433.8195.3333          1432.5
Permanent Ineff=
       F       F
#Block Obstruct= 1 ,-1
  425.84  467.23 1470.08
Bank Sta=155.4,184.4
XS Rating Curve= 0 ,0
Exp/Cntr=0.5,0.3

Type RM Length L Ch R = 1 ,4059    ,183.3,191.3,182.9
XS GIS Cut Line= 2
     1995119.387      245285.899     1995095.081      244817.149
#Sta/Elev= 30
       0 1570.15    33.6 1546.98    69.7 1520.52    82.8 1505.66    89.4 1500.49
    99.3 1481.98   102.6 1478.02   105.8 1475.43   125.6  1476.5   128.8 1476.25
   132.1 1474.63   135.4 1470.04     142 1458.65   148.5 1451.55   151.8 1450.27
   158.4 1449.98   184.7 1432.32   191.3 1430.22   221.71427.344   237.3 1426.95
   247.1 1427.35     2511428.511     257 1431.62   263.5 1433.04   292.2 1434.14
   322.7 1436.81   375.2 1438.53   408.1  1441.3   431.1  1444.9   469.4 1457.91
#Mann= 4 ,-1 , 0
       0      .1       0   221.7    .045       0     251     .05       0
     440     .12       0
Bank Sta=221.7,251
XS Rating Curve= 0 ,0
Exp/Cntr=0.3,0.1

Type RM Length L Ch R = 1 ,3868    ,89,80.8,74.1
XS GIS Cut Line= 2
     1995305.151      245299.788     1995275.637      244801.524
#Sta/Elev= 30
       0 1541.81    40.9 1513.14    57.4 1503.07   100.1 1475.04   106.7 1465.17
   109.9 1461.07   113.2 1458.97   116.5 1458.42   136.2 1459.66   139.5  1458.4
     152 1449.45   159.2 1445.27   185.5 1433.51   208.5 1426.96   221.5 1424.43
   221.8  1424.4   238.1 1422.55     248  1423.3   254.5 1426.53   261.9 1427.21
   284.1 1427.29   307.1 1428.98   333.4 1429.25   349.9 1430.98   359.7 1435.34
   372.9 1442.95   382.9  1444.9   448.5 1471.93   487.9 1493.23   499.1 1500.74
#Mann= 5 ,-1 , 0
       0      .1       0   221.5      .1       0   221.8    .045       0
   254.5      .1       0     360     .12       0
#XS Ineff= 2 , 0
                          319.15         1436.01
Permanent Ineff=
       F       F
Bank Sta=221.8,254.5
XS Rating Curve= 0 ,0
Exp/Cntr=0.5,0.3

Type RM Length L Ch R = 1 ,3787    ,23.9,24.5,25.4
XS GIS Cut Line= 4
1995377.27875241245309.2066886211995387.60991052245112.814256418
1995343.75892951244956.2053745341995343.42311151 244861.62155594
#Sta/Elev= 30
       0 1523.47    37.2 1502.09    47.1 1495.02    83.2 1473.07    96.3 1466.75
   104.2 1458.47   107.3 1456.07     116 1454.51   119.3 1452.33   122.6 1451.44
   142.3 1451.24   145.6 1449.68   148.9 1447.01   165.3 1439.87   171.9  1439.2
   201.6 1431.98   218.7 1425.65   238.81423.786  243.24 1422.03  248.78 1421.15
  260.42 1421.63   268.51424.232   276.6 1425.81   327.7 1426.78   341.3 1428.92
   351.6 1431.92   372.5 1440.53   397.8 1456.11   407.6  1459.5   453.9 1485.89
#Mann= 3 , 0 , 0
       0      .1       0   238.8    .045       0   268.5      .1       0
#XS Ineff= 3 ,-1
       0     203 1428.62     297     303    1426     303     400    1440
Permanent Ineff=
       F       F       F
#Block Obstruct= 1 ,-1
  170.37  196.66 1459.27
Bank Sta=238.8,268.5
XS Rating Curve= 0 ,0
Exp/Cntr(USF)=0,0
Exp/Cntr=0.5,0.3

Type RM Length L Ch R = 3 ,3777    ,,,
BEGIN DESCRIPTION:
Unnamed Road
Survey ID: 54089MAC030
END DESCRIPTION:
Bridge Culvert--1,0,-1,-1, 0
Deck Dist Width WeirC Skew NumUp NumDn MinLoCord MaxHiCord MaxSubmerge Is_Ogee
16,7,2.6,0, 7, 7, , , 0.98, 0, 0,0,,
     210     211     211     255     289     289     291
1428.4831428.4831428.483 1430.24 1425.76 1425.76 1425.76
                1427.783 1429.54 1425.06
     210     211     211     255     289     289     291
1428.4831428.4831428.483 1430.24 1425.76 1425.76 1425.76
                1427.783 1429.54 1425.06
Pier Skew, UpSta & Num, DnSta & Num=  ,232, 2 ,232, 2 , 0 , 0 , 0 ,,
       4       4
       0    1429
       4       4
       0    1429
Pier Skew, UpSta & Num, DnSta & Num=  ,272, 2 ,272, 2 , 0 , 0 , 0 ,,
       4       4
       0    1429
       4       4
       0    1429
BR Coef=-1 , 1 , 0 ,1.25, 0 ,,,0.8,0,2,0,
WSPro=,,,, 1 ,,,, 0 ,,,, 0 ,,,,-1 ,-1 ,-1 , 0 , 0 , 0 , 0 , 0
BR U #Sta/Elev= 30
       0 1523.47    37.2 1502.09    47.1 1495.02    83.2 1473.07    96.3 1466.75
   104.2 1458.47   107.3 1456.07     116 1454.51   119.3 1452.33   122.6 1451.44
   142.3 1451.24   145.6 1449.68   148.9 1447.01   165.3 1439.87   171.9  1439.2
   201.6 1431.98   218.7 1425.65   238.81423.786  243.24 1422.03  248.78 1421.15
  260.42 1421.63   268.51424.232   276.6 1425.81   327.7 1426.78   341.3 1428.92
   351.6 1431.92   372.5 1440.53   397.8 1456.11   407.6  1459.5   453.9 1485.89
BR U #Mann= 3
       0      .1   238.8     .04   268.5      .1
BR D #Sta/Elev= 30
       0 1516.71    11.1 1509.95    21.7 1504.97    40.6 1494.31    83.3 1473.68
    96.4 1468.52     103 1461.94   106.2 1459.64   116.1 1457.17   125.9    1449
   145.6 1449.76   148.9 1449.17   155.5 1445.49   168.6 1440.15   198.2  1434.3
   215.1 1427.25   242.2 1423.49   252.3 1422.32   265.9 1422.65   272.7 1424.01
   279.4 1425.61   316.7 1425.99   325.8 1427.51     337 1428.02   343.7 1429.53
   356.4 1436.05   373.6 1447.33   403.3 1462.01     413 1465.41   441.7 1481.99
BR D #Mann= 3
       0      .1   242.2     .04   272.7      .1
BC Design=,, 0 ,, 0 ,,,,,,
BC Use User HTab Curves=0
BC User HTab FreeFlow(D)= 0

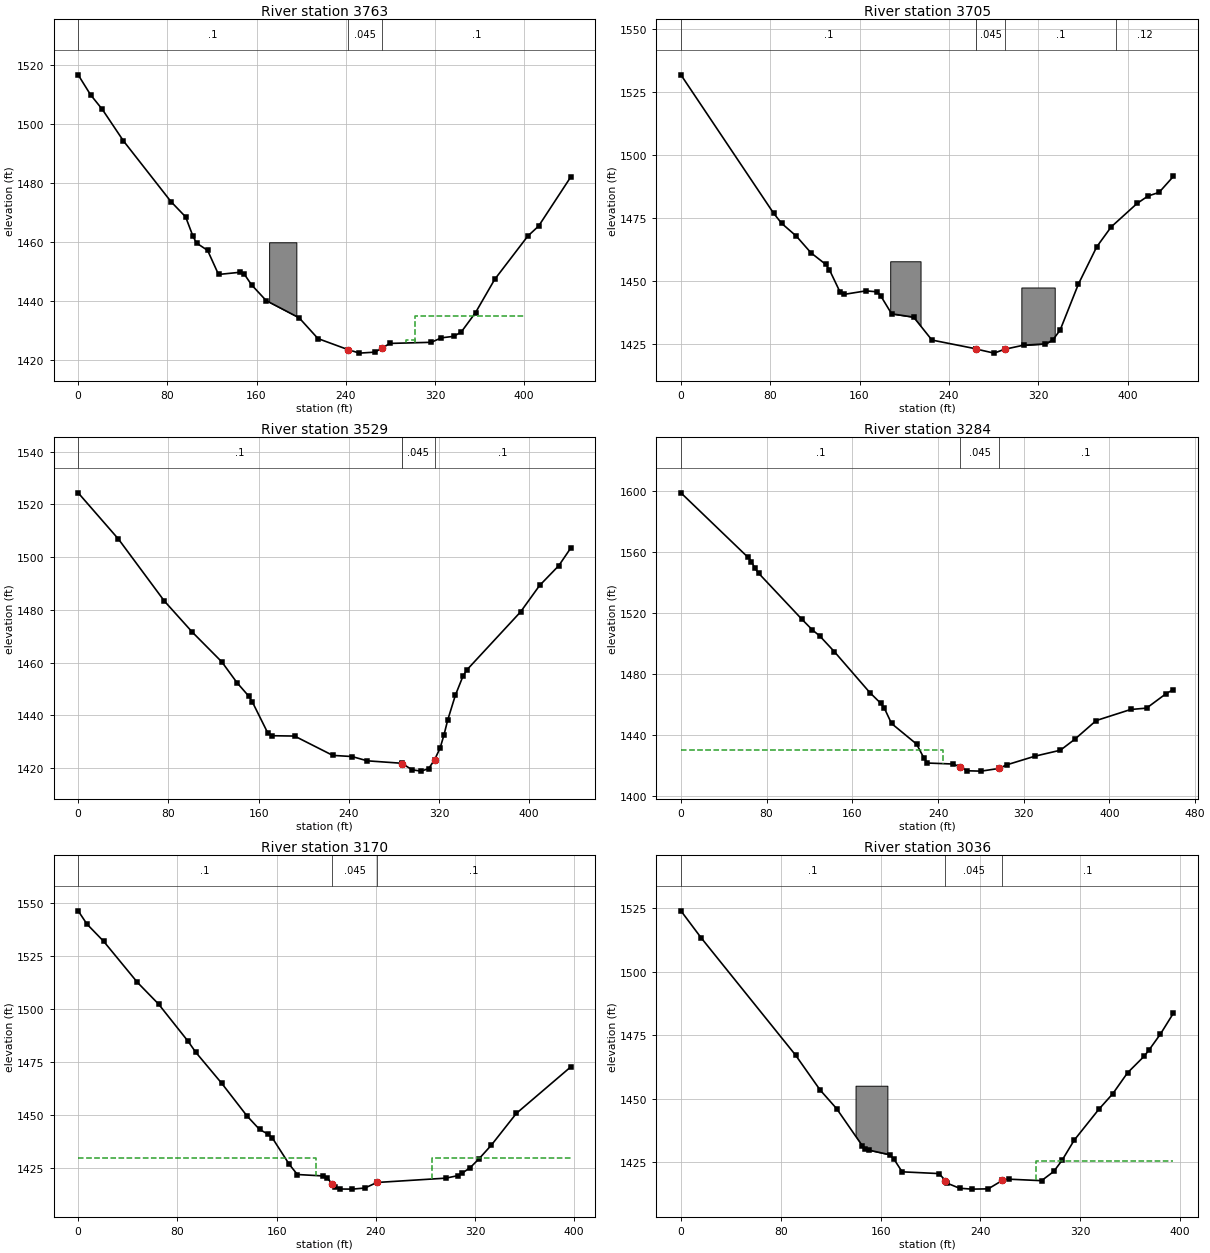
Type RM Length L Ch R = 1 ,3763    ,48.7,58,65.4
XS GIS Cut Line= 4
1995410.95025631245312.691758555 1995411.8184249245116.983664742
1995372.32635875244961.2523680571995370.08965419244875.932475042
#Sta/Elev= 30
       0 1516.71    11.1 1509.95    21.7 1504.97    40.6 1494.31    83.3 1473.68
    96.4 1468.52     103 1461.94   106.2 1459.64   116.1 1457.17   125.9    1449
   145.6 1449.76   148.9 1449.17   155.5 1445.49   168.6 1440.15   198.2  1434.3
   215.1 1427.25   242.2 1423.49   252.3 1422.32   265.9 1422.65   272.7 1424.01
   279.4 1425.61   316.7 1425.99   325.8 1427.51     337 1428.02   343.7 1429.53
   356.4 1436.05   373.6 1447.33   403.3 1462.01     413 1465.41   441.7 1481.99
#Mann= 3 ,-1 , 0
       0      .1       0   242.2    .045       0   272.7      .1       0
#XS Ineff= 3 ,-1
       0 205.667    1427 294.333     302  1426.8     302     400    1435
Permanent Ineff=
       F       F       F
#Block Obstruct= 1 ,-1
  171.29  195.71 1459.91
Bank Sta=242.2,272.7
XS Rating Curve= 0 ,0
Exp/Cntr(USF)=0,0
Exp/Cntr=0.5,0.3

Type RM Length L Ch R = 1 ,3705    ,162.2,176.1,180.9
XS GIS Cut Line= 2
     1995456.192      245332.774      1995452.72      244891.802
#Sta/Elev= 30
       0 1531.68      83 1476.82    90.2 1472.81   103.4 1467.72   116.5 1461.11
   129.6 1456.57   132.9 1454.49   142.7  1445.4     146 1444.64   165.7 1446.04
   175.5 1445.67   178.8 1444.17   188.7 1436.94   208.4 1435.63   224.8 1426.54
   264.1 1423.08   264.61422.955   280.5 1421.36   289.81422.882   306.8  1424.5
   326.5 1425.02     333 1426.56   339.6 1430.49     356 1448.76   372.4 1463.51
   385.3 1471.38   408.5 1480.69   418.3 1483.64   428.2 1485.07     441  1491.4
#Mann= 5 ,-1 , 0
       0      .1       0   264.1      .1       0   264.6    .045       0
   289.8      .1       0     390     .12       0
#Block Obstruct= 2 ,-1
  187.44   214.6 1457.77  304.88  334.74 1447.38
Bank Sta=264.6,289.8
XS Rating Curve= 0 ,0
Exp/Cntr=0.3,0.1

Type RM Length L Ch R = 1 ,3529    ,234.4,244.6,233.9
XS GIS Cut Line= 2
     1995548.206      245362.288     1995661.053      244940.413
#Sta/Elev= 30
       0  1524.4    35.7 1506.86    76.4 1483.35   101.2 1471.54   127.4 1460.23
   140.9 1452.32   151.3 1447.22   154.5 1445.01   168.1  1433.3   171.5 1432.22
   191.9 1432.09   225.8 1424.75   242.8 1424.32   256.4 1422.69     287 1421.76
   287.41421.657     296  1419.3     304 1418.78   310.8  1419.7   316.11423.155
   320.9 1427.45   324.3 1432.35   327.7 1438.15   334.5 1447.57   341.3 1454.88
   344.7  1457.2   392.3  1479.2   409.2 1489.24   426.2 1496.75   436.7 1503.37
#Mann= 4 ,-1 , 0
       0      .1       0     287      .1       0   287.4    .045       0
   316.1      .1       0
Bank Sta=287.4,316.1
XS Rating Curve= 0 ,0
Exp/Cntr=0.3,0.1

Type RM Length L Ch R = 1 ,3284    ,113.1,113.7,116.9
Node Name=A
XS GIS Cut Line= 2
       1995773.9      245457.774     1995869.386      245008.122
#Sta/Elev= 30
       0  1598.8    62.4 1556.67    65.8 1553.77    69.1 1549.37    72.5 1546.12
   112.7 1516.09   122.8 1508.87   129.5 1505.05   143.3 1494.63   176.4 1467.82
   186.5 1460.87   189.9 1457.66   196.6 1447.61     220 1434.09   226.7 1425.15
   230.1 1421.68   253.6 1421.04   260.81419.316     267 1416.59   280.4 1416.37
   296.71418.116   304.1 1420.48   330.7 1426.21   354.2 1430.07   367.6 1437.21
   387.7 1449.53   419.9 1456.78   434.7 1457.67   453.1 1467.25   459.7 1469.81
#Mann= 3 , 0 , 0
       0      .1       0   260.8    .045       0   296.7      .1       0
#XS Ineff= 2 , 0
             245    1430
Permanent Ineff=
       F       F
Bank Sta=260.8,296.7
XS Rating Curve= 0 ,0
Exp/Cntr=0.3,0.1

Type RM Length L Ch R = 1 ,3170    ,138.5,134,124
XS GIS Cut Line= 2
     1995885.012      245426.524     1995987.442      245042.844
#Sta/Elev= 30
       0 1546.17     7.1 1539.92    20.6  1531.8    47.8  1512.5    64.8 1502.33
    88.6 1484.84    94.9  1479.6   115.7 1465.09   136.1 1449.73   146.3 1443.33
   153.1 1441.15   156.5 1439.42   170.3 1426.87   176.8 1422.15   197.2 1421.49
   200.6 1420.63   204.8 1417.83   207.4 1416.31   210.8 1415.34     221 1415.28
   231.2  1415.8   240.91418.405   296.6 1420.45   305.9 1421.59   309.3 1422.65
   316.1 1425.38   322.9 1429.33   333.1 1435.91   353.4 1450.93   397.1  1472.7
#Mann= 3 , 0 , 0
       0      .1       0   204.8    .045       0   240.9      .1       0
#XS Ineff= 2 , 0
             192    1430     285            1430
Permanent Ineff=
       F       F
Bank Sta=204.8,240.9
XS Rating Curve= 0 ,0
Exp/Cntr=0.3,0.1

Type RM Length L Ch R = 1 ,3036    ,134.6,134.4,133.2
XS GIS Cut Line= 2
     1996065.567      245449.094     1996082.928      245054.997
#Sta/Elev= 30
       0    1524    16.3  1513.3    91.8 1467.15   111.5 1453.38   124.7 1446.04
   145.4 1431.33   147.6 1430.25   150.9 1429.64   167.4 1427.84   170.7  1426.1
   177.2 1421.11   206.8 1420.42   211.91417.631   213.3 1416.63   223.2 1414.64
     233 1414.29   246.2  1414.4   257.61417.755   262.6 1418.22   288.9 1417.62
   298.7 1421.26   305.3 1425.62   315.1 1433.61   334.8 1445.76   345.9 1451.85
   357.8 1460.15     371 1466.62   375.1  1469.2   384.1 1475.38   394.5 1483.61
#Mann= 3 , 0 , 0
       0      .1       0   211.9    .045       0   257.6      .1       0
#XS Ineff= 2 , 0
                          284.85          1425.5
Permanent Ineff=
       F       F
#Block Obstruct= 1 ,-1
   139.9  165.41 1455.06
Bank Sta=211.9,257.6
XS Rating Curve= 0 ,0
Exp/Cntr=0.3,0.1

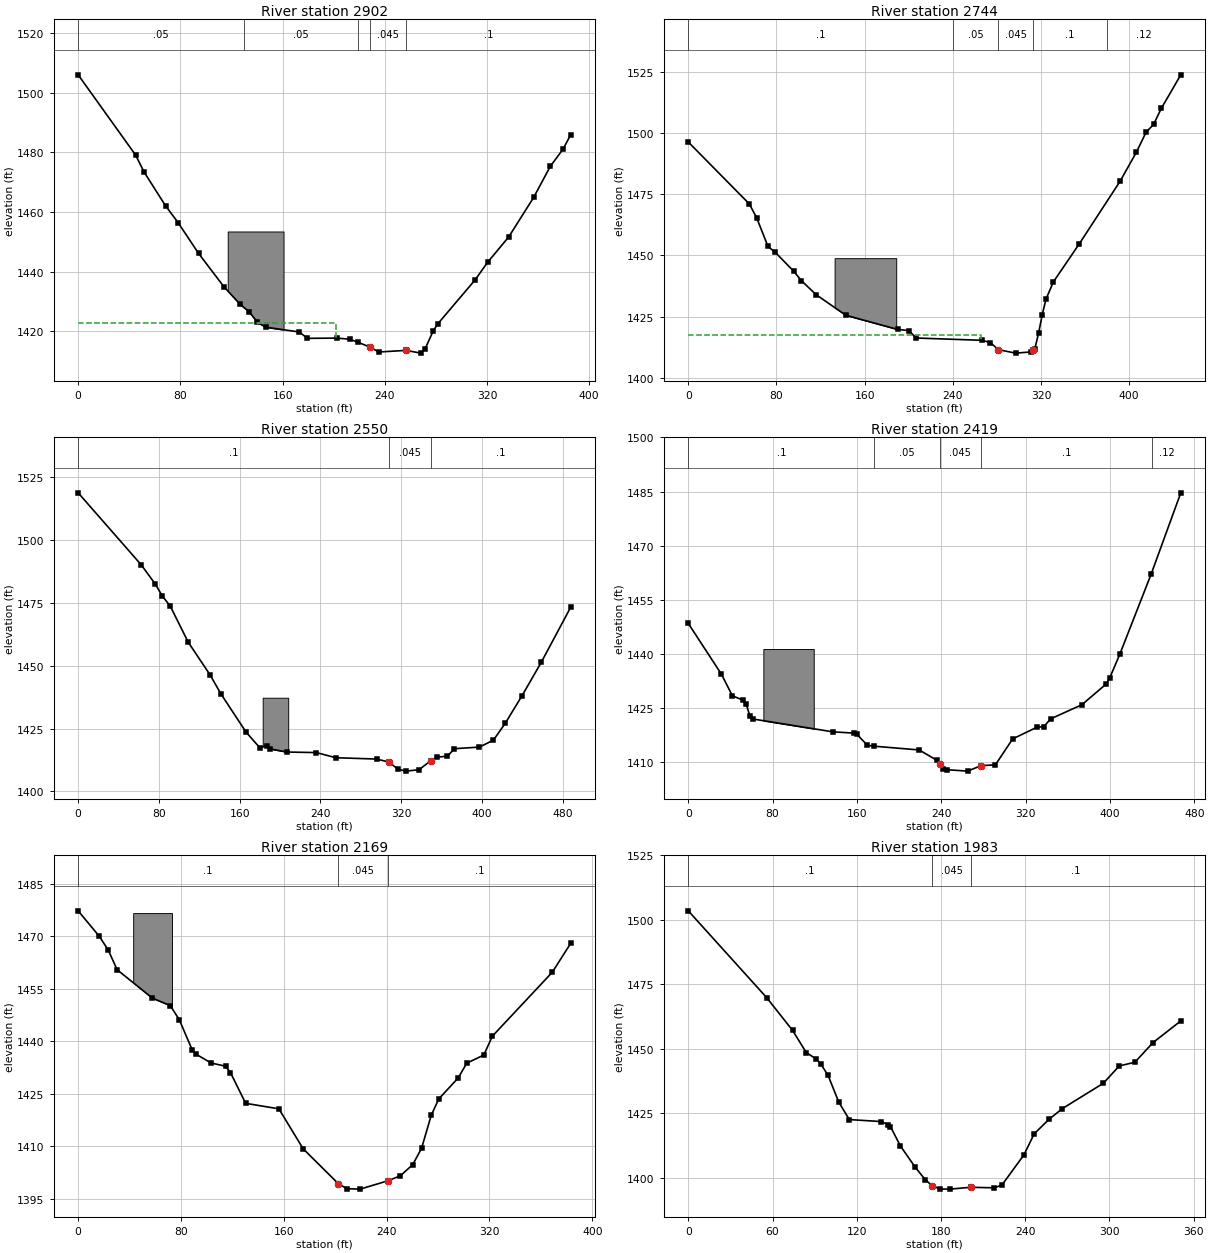
Type RM Length L Ch R = 1 ,2902    ,147.9,158.2,161.4
XS GIS Cut Line= 2
     1996206.192      245464.719     1996211.401      245079.302
#Sta/Elev= 30
       0 1506.01      45 1479.07    51.6 1473.41    68.4 1462.08    78.2 1456.45
    94.2 1446.14   114.1 1434.92   126.7 1429.06   133.6 1426.63   140.2 1423.08
   146.7 1421.37     173 1419.77   179.5 1417.63   202.5 1417.71   212.4 1417.35
   218.9 1416.33   228.71414.636   235.3 1413.05   256.71413.593   268.1 1412.67
   271.4 1413.98     278 1420.19   281.3  1422.4   310.8 1437.29   320.6  1443.2
     337 1451.64   356.6 1464.95   369.5 1475.27   379.7  1481.2   385.5 1485.92
#Mann= 5 ,-1 , 0
       0     .05       0     130     .05       0   218.9      .1       0
   228.7    .045       0   256.7      .1       0
#XS Ineff= 2 , 0
          201.69 1422.61
Permanent Ineff=
       F       F
#Block Obstruct= 1 ,-1
  117.05  160.75 1453.47
Bank Sta=228.7,256.7
XS Rating Curve= 0 ,0
Exp/Cntr=0.3,0.1

Type RM Length L Ch R = 1 ,2744    ,187.8,193.6,197
XS GIS Cut Line= 2
     1996299.942      245509.857       1996398.9      245074.094
#Sta/Elev= 30
       0 1496.26    55.4 1471.01    62.2 1465.22    72.3 1453.69      79 1451.25
    95.8 1443.52   102.5 1439.79     116 1434.03   142.9 1425.64   189.9 1419.86
   200.1 1419.39   206.8 1416.35   266.8 1415.41   274.1 1414.47   281.41411.603
     297 1410.19   311.1 1410.68   313.11411.474   314.5 1412.03   317.9 1418.44
   321.2 1425.89   324.6 1432.23   331.3 1439.23   354.6 1454.62   391.9 1480.31
   406.7 1492.17   415.4 1500.27   422.2 1503.42   429.3 1510.02   446.9 1523.65
#Mann= 5 ,-1 , 0
       0      .1       0     240     .05       0   281.4    .045       0
   313.1      .1       0     380     .12       0
#XS Ineff= 2 , 0
          265.92 1417.41
Permanent Ineff=
       F       F
#Block Obstruct= 1 ,-1
  132.77  188.69  1448.9
Bank Sta=281.4,313.1
XS Rating Curve= 0 ,0
Exp/Cntr=0.3,0.1

Type RM Length L Ch R = 1 ,2550    ,140.9,131.3,116.6
XS GIS Cut Line= 3
 1996385.1487081245564.3145880641996473.14172719245481.497628917
1996603.40590252 245138.15231912
#Sta/Elev= 30
       0 1518.71    62.5 1490.09    76.5  1482.4    83.4 1477.68    91.3 1473.65
     109 1459.38   130.8 1446.29   141.3  1438.9   166.3 1423.63   179.9 1417.44
   186.9 1418.21   190.4  1416.9     207 1415.67   236.1 1415.45   255.3 1413.41
   295.7 1412.88   308.21411.669   316.8 1408.86   324.8 1408.08   337.8 1408.63
   349.61412.271   355.4 1413.64   365.9 1414.01   372.9    1417   397.5 1417.63
   411.5 1420.37   423.3 1427.13   439.6 1437.86   458.9  1451.3   488.1 1473.23
#Mann= 3 ,-1 , 0
       0      .1       0   308.2    .045       0   349.6      .1       0
#Block Obstruct= 1 ,-1
  182.87  208.16 1437.26
Bank Sta=308.2,349.6
XS Rating Curve= 0 ,0
Exp/Cntr(USF)=0,0
Exp/Cntr=0.3,0.1

Type RM Length L Ch R = 1 ,2419    ,259.7,250.1,231.5
XS GIS Cut Line= 2
     1996674.942      245586.246     1996662.789      245119.233
#Sta/Elev= 30
       0 1448.51    31.4 1434.47    41.9 1428.45    51.7  1427.3      55 1426.13
    58.3    1423    61.6 1422.03   137.1 1418.49   156.8 1418.14     160 1417.78
   169.9 1414.77   176.4 1414.51   219.1 1413.47   235.5 1410.66   238.51409.603
   242.1 1408.29   245.4    1408   265.1 1407.61   277.71409.128   291.3 1409.34
   307.7 1416.53   330.7 1419.76   337.3 1419.96   343.8 1422.09   373.4    1426
   396.3  1431.7   399.6 1433.29   409.5 1440.09   439.1 1462.17   467.2 1484.67
#Mann= 5 ,-1 , 0
       0      .1       0   176.4     .05       0   238.5    .045       0
   277.7      .1       0     440     .12       0
#Block Obstruct= 1 ,-1
   71.22  119.02 1441.43
Bank Sta=238.5,277.7
XS Rating Curve= 0 ,0
Exp/Cntr=0.3,0.1

Type RM Length L Ch R = 1 ,2169    ,180.4,185.8,188.7
XS GIS Cut Line= 4
     1996996.123      245468.1911996966.59310827245377.125166107
1996868.07176443245203.4164809191996853.69149648245116.871499378
#Sta/Elev= 30
       0 1477.26    16.5 1469.95    23.4 1466.04    30.3 1460.43    57.6 1452.34
    71.7 1450.15    78.6 1446.18    88.9 1437.37    91.5 1436.33   103.4 1433.76
   114.7 1432.84   118.5 1431.02   130.3 1422.23   156.2 1420.65     175 1409.25
   202.41399.266     209 1397.83   219.4  1397.7     241 1400.09   250.7 1401.51
   260.3  1404.7   267.2 1409.39   274.7 1418.81   280.6  1423.5   295.7 1429.49
   302.3 1433.69   315.6 1436.04   322.3 1441.44   368.9 1459.71   383.2 1467.96
#Mann= 3 , 0 , 0
       0      .1       0   202.4    .045       0     241      .1       0
#Block Obstruct= 1 ,-1
    42.8   72.99 1476.61
Bank Sta=202.4,241
XS Rating Curve= 0 ,0
Exp/Cntr=0.3,0.1

Type RM Length L Ch R = 1 ,1983    ,197.2,197.8,198.6
XS GIS Cut Line= 2
     1997154.109      245412.635     1997025.637      245086.246
#Sta/Elev= 30
       0 1503.48    55.9 1469.77    74.3 1457.09    84.1 1448.46    91.1 1446.04
    94.5 1443.98    99.6 1439.61   107.2 1429.27   114.7 1422.51     137 1421.75
   142.6 1420.53     144 1419.79   151.1 1412.26   161.6 1404.07   168.7 1399.24
   173.71396.858   179.3 1395.59   186.3 1395.53   201.21396.245   218.1 1396.04
   223.5 1397.18   239.2 1408.92   246.3 1416.92   256.8 1422.55   266.5 1426.78
   295.6 1436.58     307 1443.32   318.1 1444.74   330.9 1452.31   350.8 1460.78
#Mann= 3 , 0 , 0
       0      .1       0   173.7    .045       0   201.2      .1       0
Bank Sta=173.7,201.2
XS Rating Curve= 0 ,0
Exp/Cntr=0.3,0.1

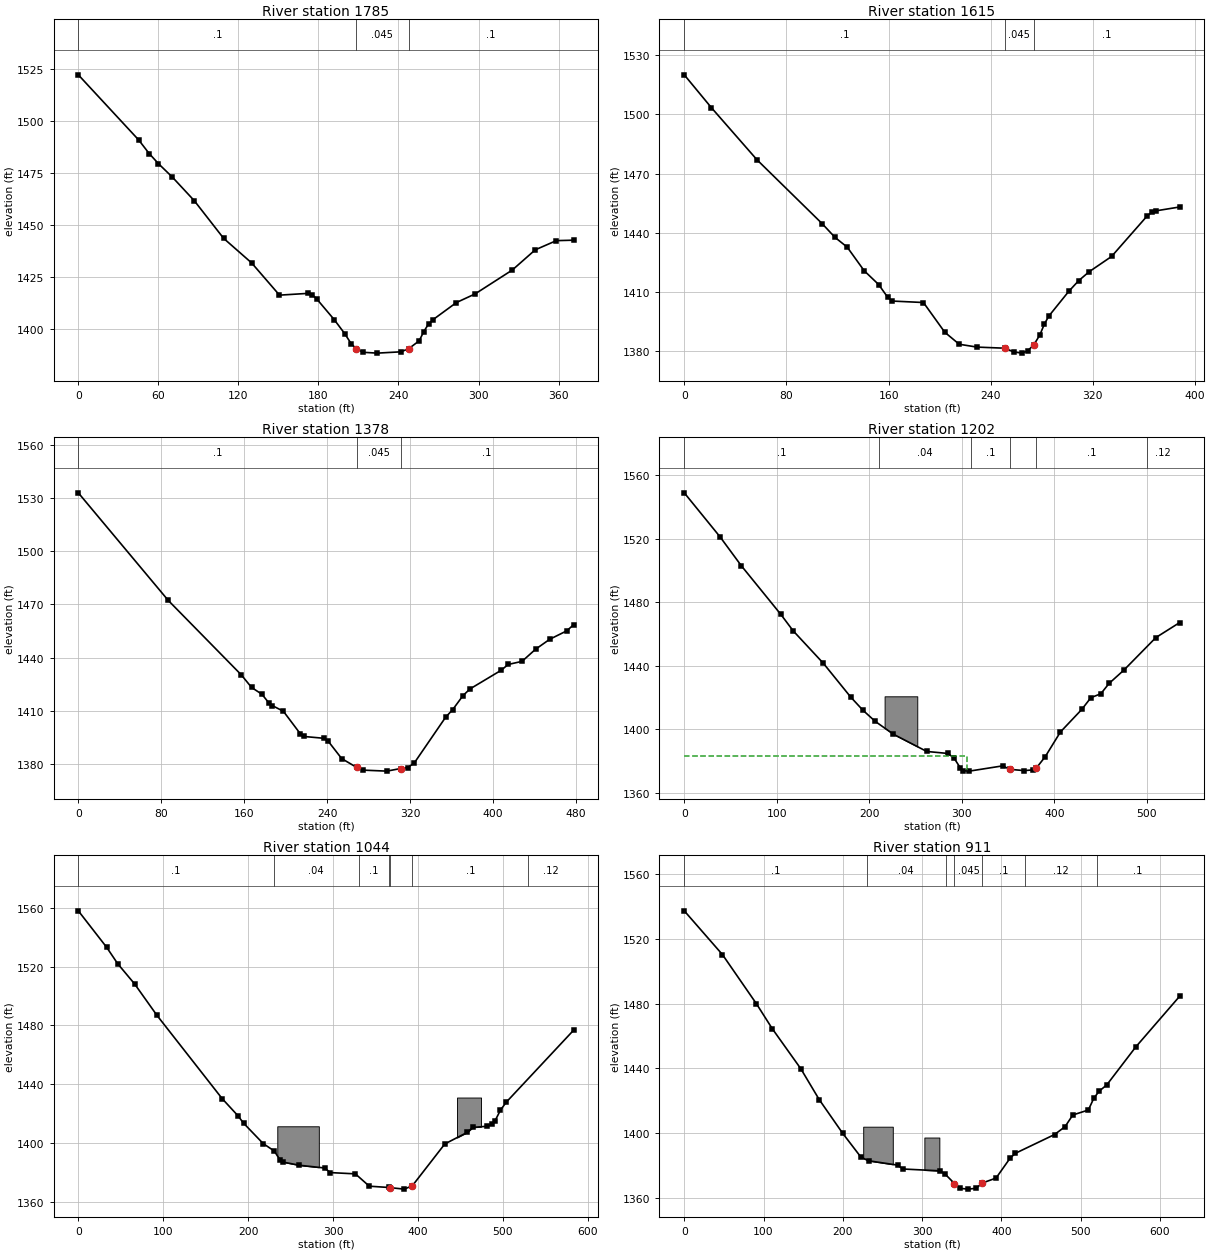
Type RM Length L Ch R = 1 ,1785    ,169.4,170.5,168.5
XS GIS Cut Line= 2
     1997345.081      245374.441     1997218.345      245025.482
#Sta/Elev= 30
       0 1521.97    45.3 1490.73    53.1 1484.27    60.1 1479.39    70.5 1472.96
    86.9 1461.69   108.9 1443.65   129.9 1431.87   150.8 1416.42   171.8 1417.25
   175.2  1416.7   178.7  1414.6   191.8  1404.7   199.7 1397.97   204.6 1393.09
   208.41390.748   213.6 1389.03   224.1 1388.64   241.6 1389.26   247.51390.674
   255.5 1394.54     259    1399   262.5 1402.59     266 1404.73   283.4 1412.87
   297.4    1417   325.3 1428.45   342.5 1438.13   358.3 1442.53   371.3 1442.75
#Mann= 3 ,-1 , 0
       0      .1       0   208.4    .045       0   247.5      .1       0
Bank Sta=208.4,247.5
XS Rating Curve= 0 ,0
Exp/Cntr=0.3,0.1

Type RM Length L Ch R = 1 ,1615    ,228.5,236.7,238.1
XS GIS Cut Line= 2
     1997510.011       245325.83     1997372.859      244962.983
#Sta/Elev= 30
       0 1520.07    21.3 1503.39    56.9 1477.06   107.9 1444.72     118 1437.73
   127.6 1432.76   140.9  1420.8   152.2 1413.83   159.2 1407.46   162.7 1405.45
   187.3  1404.7     204 1389.65   215.3 1383.56   229.3 1382.11     2511381.558
     258 1379.68   264.4 1379.06     269 1380.25   273.8 1383.35   278.4 1388.19
     282  1393.8   285.5 1397.85   301.1 1410.37   308.9  1415.8     317 1420.27
   334.6 1428.03   362.6 1448.65   366.1 1450.42   369.6 1451.18   387.9 1453.11
#Mann= 3 , 0 , 0
       0      .1       0     251    .045       0   273.8      .1       0
Bank Sta=251,273.8
XS Rating Curve= 0 ,0
Exp/Cntr=0.3,0.1

Type RM Length L Ch R = 1 ,1378    ,167.8,176.3,179.5
XS GIS Cut Line= 2
     1997706.192      245331.038     1997614.178      244862.288
#Sta/Elev= 30
       0  1532.9    86.8  1472.2   157.1 1430.32   167.1 1423.17   177.1 1419.33
   183.8 1414.43   187.2 1412.92   197.8 1409.72   213.9 1397.21   217.2 1395.56
   237.3 1394.49   240.6 1393.16     254 1383.07   268.31378.142   274.1 1376.58
   297.5    1376   310.8 1377.46   317.5 1377.89   324.2 1380.77   354.3 1406.45
     361 1410.65     371 1418.59   377.7 1422.33   407.8 1432.86   414.5 1436.13
   427.9 1437.88   440.9 1444.69   454.6 1450.33   470.9 1455.05   477.7 1458.54
#Mann= 3 ,-1 , 0
       0      .1       0   268.3    .045       0   310.8      .1       0
Bank Sta=268.3,310.8
XS Rating Curve= 0 ,0
Exp/Cntr=0.3,0.1

Type RM Length L Ch R = 1 ,1202    ,153.9,158,160.3
XS GIS Cut Line= 2
     1997834.664      245350.135     1997808.623      244815.413
#Sta/Elev= 30
       0 1548.88    38.7 1521.14    61.7 1502.93   104.4 1472.29   117.6 1462.03
   150.4 1441.47     180 1420.17   193.1 1411.95   206.3 1404.97     226 1396.85
   262.1 1385.98   285.1 1384.71   291.7 1381.72   298.2 1375.78   301.5 1373.88
   308.1 1373.59   344.2 1376.91   351.7 1374.74   367.2 1373.92   377.1 1374.37
   380.4 1375.42   390.2 1382.74   406.6 1398.27   429.6 1412.42   439.5 1419.86
   450.2 1422.31   459.2 1428.85   475.3 1437.29   509.7  1457.7   535.4 1467.14
#Mann= 6 ,-1 , 0
       0      .1       0     210     .04       0     310      .1       0
   351.7    .045       0   380.4      .1       0     500     .12       0
#XS Ineff= 2 , 0
          305.92 1382.91
Permanent Ineff=
       F       F
#Block Obstruct= 1 ,-1
  216.52  251.85 1420.72
Bank Sta=351.7,380.4
XS Rating Curve= 0 ,0
Exp/Cntr=0.3,0.1

Type RM Length L Ch R = 1 ,1044    ,132.3,132.8,133
XS GIS Cut Line= 2
     1997945.775      245370.969     1997989.178      244789.371
#Sta/Elev= 30
       0 1558.05    33.4 1533.19    46.5 1521.94    66.3 1508.27    92.6 1486.88
   169.4 1430.18   187.8 1418.64   194.6 1413.47   217.6 1399.64   230.8  1394.5
   237.4 1388.44   240.6 1387.05   260.4 1384.83     290 1382.99   296.6 1379.85
   326.2 1378.98   342.6 1370.59   365.7  1369.7   366.8 1369.61   383.7 1368.59
   393.21370.824   431.5 1399.35   457.8  1407.2   464.4  1410.6   481.7 1411.41
   487.4 1412.81   490.7 1415.18     497 1422.34   503.8 1427.75   583.2 1476.83
#Mann= 7 ,-1 , 0
       0      .1       0     230     .04       0     330      .1       0
   365.7      .1       0   366.8    .045       0   393.2      .1       0
     530     .12       0
#Block Obstruct= 2 ,-1
  234.26  283.17 1411.37  445.88  474.14 1430.95
Bank Sta=366.8,393.2
XS Rating Curve= 0 ,0
Exp/Cntr=0.3,0.1

Type RM Length L Ch R = 1 ,911     ,121.9,123.1,128
XS GIS Cut Line= 2
      1998069.04      245369.233     1998131.539      244747.705
#Sta/Elev= 30
       0 1537.24    48.2 1510.19    91.1 1479.79   110.9 1464.52   147.1 1439.64
   170.2 1420.67   199.9 1399.78     223 1385.01   232.9 1382.86   269.1  1380.2
   275.7 1377.81   321.9 1376.69   328.5 1374.91   340.81368.801   348.3 1365.84
   358.2 1365.38     368 1365.89   376.11369.201   393.2 1372.21   410.9 1384.49
   417.5 1387.48     467  1399.1   480.2 1403.94     490 1411.16   509.6 1414.24
   516.4 1421.41     523 1425.76   532.9 1429.79   569.2 1453.06   624.7 1484.46
#Mann= 7 ,-1 , 0
       0      .1       0     230     .04       0     330      .1       0
   340.8    .045       0   376.1      .1       0     430     .12       0
     520      .1       0
#Block Obstruct= 2 ,-1
  225.66  262.98 1403.94   302.8  321.69 1397.25
Bank Sta=340.8,376.1
XS Rating Curve= 0 ,0
Exp/Cntr=0.5,0.3

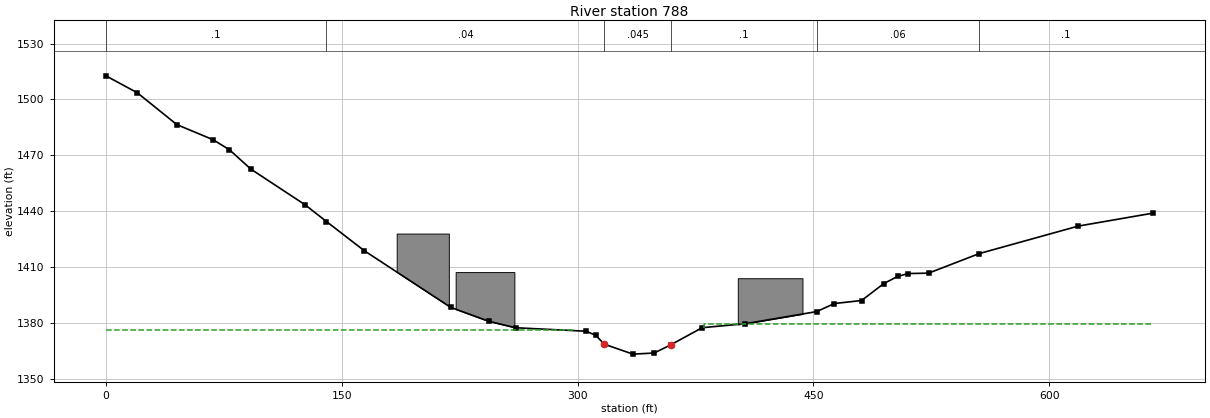
Type RM Length L Ch R = 1 ,788     ,74.1,74.1,74.2
XS GIS Cut Line= 5
       1998125.6      245376.505     1998207.197      245114.352
     1998238.447      244991.088     1998266.225       244923.38
     1998271.433      244732.407
#Sta/Elev= 30
       0 1512.66      20 1503.55    45.1 1486.47    68.2 1478.34    78.5    1473
    92.2 1462.56   126.6 1443.45   140.3 1434.39   164.4 1418.71   219.3 1388.32
   243.4 1380.88   260.6 1377.37   305.5 1375.49   311.6 1373.26     3171368.529
   335.21363.201  348.65 1363.79   359.3 1368.21   379.2  1377.4   406.5 1379.52
   452.1 1386.05   463.3 1390.38   480.6 1391.99   494.8 1401.13   503.5 1404.91
   510.1 1406.47   523.2 1406.69   555.5 1417.21   618.4 1431.96     666 1438.93
#Mann= 6 ,-1 , 0
       0      .1       0   140.3     .04       0     317    .045       0
   359.3      .1       0   452.1     .06       0   555.5      .1       0
#XS Ineff= 2 , 0
           297.5 1376.03   380.5         1379.28
Permanent Ineff=
       F       F
#Block Obstruct= 3 ,-1
  184.94  218.11 1427.95  222.44   259.8 1407.26  401.88  443.02 1403.96
Bank Sta=317,359.3
XS Rating Curve= 0 ,0
Exp/Cntr=0.5,0.3