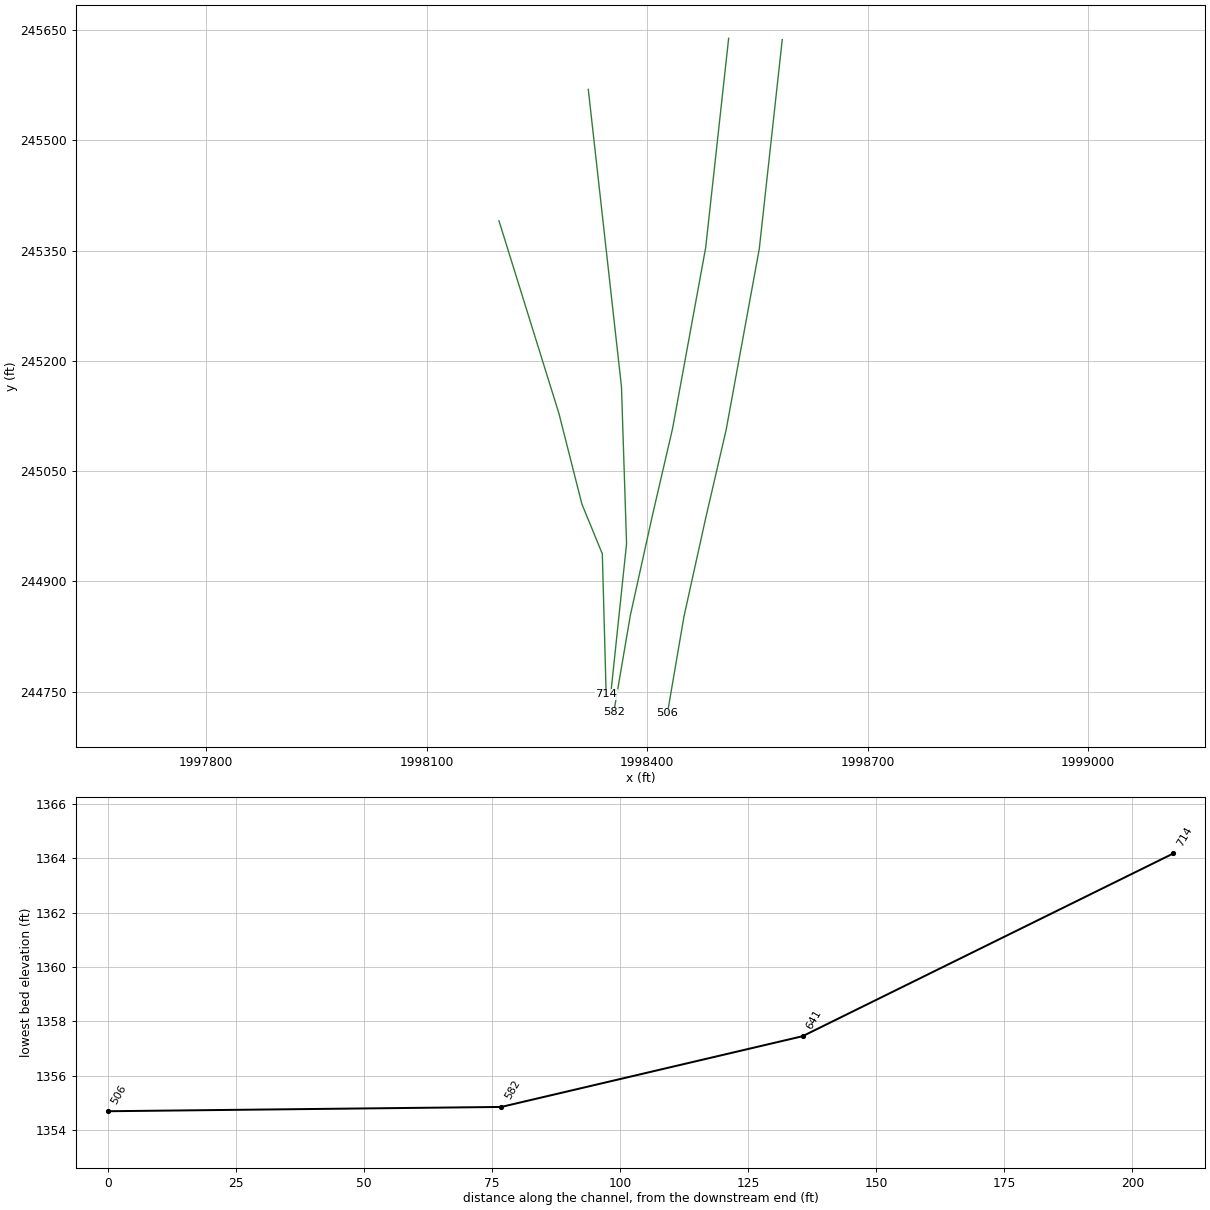
HEC-RAS study MADAMCK.prj: MADAMCK

--- MADAMCK.g01 (geometry) --- (continued)

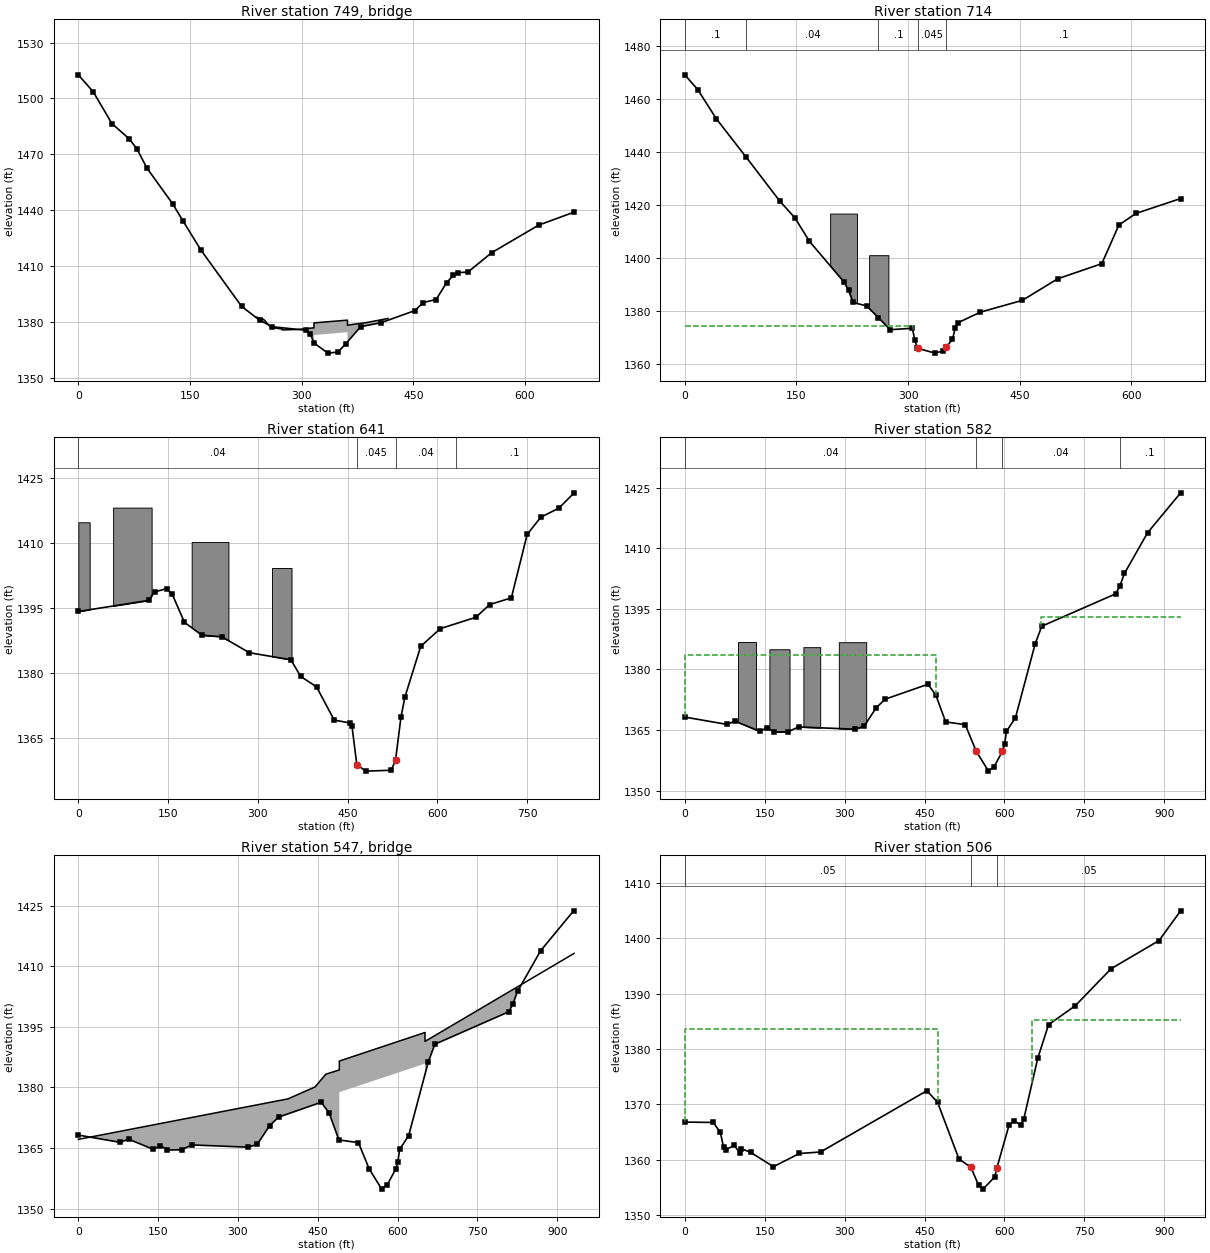
Type RM Length L Ch R = 3 ,749     ,,,
BEGIN DESCRIPTION:
Madams Creek Rd
Survey ID: 54089MAC020
END DESCRIPTION:
Bridge Culvert--1,0,-1,-1, 0
Deck Dist Width WeirC Skew NumUp NumDn MinLoCord MaxHiCord MaxSubmerge Is_Ogee
18,34,2.6,0, 36, 35, , , 0.98, 0, 0,0,,
 239.465  240.84 241.363 242.901 246.337 246.603  247.46 249.224 249.773 250.818
 251.844 253.209 254.465 255.807 256.645 257.085 258.499 259.706 260.081 262.326
 263.517 264.947 266.953 269.539 270.774 272.808 273.826     274     294     315
   316.5   316.5   361.5   361.5     387     416
1382.5311382.3561382.3031382.0731381.6831381.6571381.5251381.192 1381.031380.525
1380.1041379.3571378.8231378.2211377.8561377.6921377.3171377.0581377.0091376.833
1376.7331376.6271376.4851376.3591376.3071376.2351376.1931375.6661375.8821376.743
1376.7431379.4431380.9251378.2251379.6141381.831
                                                                                
                                                                                
                                                                                
        1372.9431374.425
 239.465  240.84 241.363 242.901 246.337 246.603  247.46 249.224 249.773 250.818
 251.844 253.209 254.465 255.807 256.645 257.085 258.499 259.706 260.081 262.326
 263.517 264.947 266.953 269.539 270.774 272.808 273.826     274     294   313.5
   313.5   358.5   358.5     387     416
1382.5311382.3561382.3031382.0731381.6831381.6571381.5251381.192 1381.031380.525
1380.1041379.3571378.8231378.2211377.8561377.6921377.3171377.0581377.0091376.833
1376.7331376.6271376.4851376.3591376.3071376.2351376.1931375.6661375.8821376.743
1379.4431380.9251378.2251379.6141381.831
                                                                                
                                                                                
                                                                                
1372.9431374.425
BR Coef=-1 , 1 , 0 ,, 0 ,,,0.8,0,1.2,0,
WSPro=,,,, 1 ,,,, 0 ,,,, 0 ,,,,-1 ,-1 ,-1 , 0 , 0 , 0 , 0 , 0
BR U #Sta/Elev= 30
       0 1512.66      20 1503.55    45.1 1486.47    68.2 1478.34    78.5    1473
    92.2 1462.56   126.6 1443.45   140.3 1434.39   164.4 1418.71   219.3 1388.32
   243.4 1380.88   260.6 1377.37   305.5 1375.49   311.6 1373.26     3171368.529
   335.21363.201  348.65 1363.79   359.3 1368.21   379.2  1377.4   406.5 1379.52
   452.1 1386.05   463.3 1390.38   480.6 1391.99   494.8 1401.13   503.5 1404.91
   510.1 1406.47   523.2 1406.69   555.5 1417.21   618.4 1431.96     666 1438.93
BR U #Mann= 6
       0      .1   140.3     .04     317     .04   359.3      .1   452.1     .06
   555.5      .1
BR D #Sta/Elev= 30
       0 1469.17    17.4 1463.59    42.5 1452.53    82.7 1438.01   127.4  1421.6
     148 1415.17   167.3  1406.4   213.3 1391.18   220.1 1387.81   225.9 1383.31
   244.2 1381.99     260  1377.6   275.8 1373.01   305.6 1373.57     309 1369.11
   312.3 1366.02   313.71365.932     3361364.177   346.2 1364.97   351.51366.583
   359.5 1369.33   363.1 1373.47   366.5 1375.59     397 1379.64   453.5  1384.1
     501 1392.24   560.1 1397.92   583.1 1412.51     606 1416.88     666  1422.5
BR D #Mann= 5
       0      .1    82.7     .04     260      .1   313.7     .04   351.5      .1
BC Design=,, 0 ,, 0 ,,,,,,
BC Use User HTab Curves=0
BC User HTab FreeFlow(D)= 0

Type RM Length L Ch R = 1 ,714     ,80.4,72.4,69.9
XS GIS Cut Line= 5
     1998198.517      245390.394     1998280.114      245128.241
     1998311.364      245004.977     1998339.142      244937.269
      1998344.35      244746.296
#Sta/Elev= 30
       0 1469.17    17.4 1463.59    42.5 1452.53    82.7 1438.01   127.4  1421.6
     148 1415.17   167.3  1406.4   213.3 1391.18   220.1 1387.81   225.9 1383.31
   244.2 1381.99     260  1377.6   275.8 1373.01   305.6 1373.57     309 1369.11
   312.3 1366.02   313.71365.932     3361364.177   346.2 1364.97   351.51366.583
   359.5 1369.33   363.1 1373.47   366.5 1375.59     397 1379.64   453.5  1384.1
     501 1392.24   560.1 1397.92   583.1 1412.51     606 1416.88     666  1422.5
#Mann= 5 ,-1 , 0
       0      .1       0    82.7     .04       0     260      .1       0
   313.7    .045       0   351.5      .1       0
#XS Ineff= 2 , 0
        306.1667 1374.37365.8333         1374.37
Permanent Ineff=
       F       F
#Block Obstruct= 2 ,-1
  195.22  231.22 1416.83  247.57  273.49 1401.13
Bank Sta=313.7,351.5
XS Rating Curve= 0 ,0
Exp/Cntr=0.5,0.3

Type RM Length L Ch R = 1 ,641     ,68.2,58.8,50.1
XS GIS Cut Line= 4
     1998320.044      245569.213     1998365.183      245164.699
     1998372.128      244951.157     1998350.391      244744.508
#Sta/Elev= 30
       0 1394.28   117.4 1396.84   127.3  1398.8   147.6 1399.54     157 1398.24
   177.3 1391.78   206.6  1388.8   239.6 1388.46   285.8 1384.77   355.1 1383.15
   371.6 1379.29     398  1376.9   427.6 1369.22   454.2 1368.56   457.2 1367.88
   465.31358.977   480.1 1357.45   522.8 1357.65     530 1359.95   539.2 1370.01
   545.7 1374.54   572.1 1386.24   604.9 1390.33   664.2 1392.94   687.3 1395.87
   723.6 1397.44     750 1412.07   772.8 1416.04   802.9 1418.12   828.5 1421.66
#Mann= 4 ,-1 , 0
       0     .04       0   465.3    .045       0     530     .04       0
  630.68      .1       0
#Block Obstruct= 4 ,-1
       0   18.95 1414.86   58.14  122.48 1418.25  189.37  250.78  1410.3
  323.68  356.25 1404.32
Bank Sta=465.3,530
XS Rating Curve= 0 ,0
Exp/Cntr=0.5,0.3

Type RM Length L Ch R = 1 ,582     ,74.5,76.8,76.5
XS GIS Cut Line= 6
     1998511.016      245638.658     1998479.766      245353.936
     1998434.627      245107.407      1998406.85      244987.616
     1998377.336      244853.936     1998354.766      244721.991
#Sta/Elev= 30
       0 1368.22    78.3 1366.43    94.7  1367.2   141.1 1364.67   154.3 1365.59
   167.5 1364.52   193.9 1364.59   213.6 1365.78   319.6 1365.22   336.3 1365.94
   359.7 1370.58   376.3 1372.66   456.4 1376.34   471.2  1373.7   489.7 1367.02
   526.4 1366.35     547  1359.8   570.11354.848   580.7 1355.94   596.2 1359.75
   600.4 1361.54   603.8 1364.67   620.8 1368.09   657.7 1386.33   670.1  1390.7
   808.8 1398.72   816.5 1400.59   825.4 1403.78   868.7 1413.82   930.8 1423.71
#Mann= 4 ,-1 , 0
       0     .04       0     547    .045       0   596.2     .04       0
   816.5      .1       0
#XS Ineff= 2 , 0
           472.5 1383.57   669.5         1393.03
Permanent Ineff=
       F       F
#Block Obstruct= 4 ,-1
   99.95  133.55  1386.8  158.83  196.64    1385  222.63  254.18 1385.52
  289.13  340.53 1386.75
Bank Sta=547,596.2
XS Rating Curve= 0 ,0
Exp/Cntr=0.5,0.3

Type RM Length L Ch R = 3 ,547     ,,,
BEGIN DESCRIPTION:
State Route 26
Survey ID: 54089MAC010
END DESCRIPTION:
Bridge Culvert--1,0,-1,-1, 0
Deck Dist Width WeirC Skew NumUp NumDn MinLoCord MaxHiCord MaxSubmerge Is_Ogee
17,34,2.6,0, 9, 10, , , 0.98, 0, 0,0,,
       0     394     445     465   490.5   490.5   651.5   651.5 931.807
1367.1581377.1841380.1441383.283 1384.34 1386.541393.6041391.4041413.183
                                         1378.841385.904
       0     394     445     465   483.5   483.5   644.5   644.5     660 931.807
1367.1581377.1841380.1441383.283 1384.05 1386.251393.6041391.4041391.4041413.183
                                         1378.551385.904
BR Coef=-1 , 1 , 0 ,, 0 ,,,0.8,0,1.2,0,
WSPro=,,,, 1 ,,,, 0 ,,,, 0 ,,,,-1 ,-1 ,-1 , 0 , 0 , 0 , 0 , 0
BR U #Sta/Elev= 30
       0 1368.22    78.3 1366.43    94.7  1367.2   141.1 1364.67   154.3 1365.59
   167.5 1364.52   193.9 1364.59   213.6 1365.78   319.6 1365.22   336.3 1365.94
   359.7 1370.58   376.3 1372.66   456.4 1376.34   471.2  1373.7   489.7 1367.02
   526.4 1366.35   546.5 1359.89   570.11354.848   580.7 1355.94   596.2 1359.75
   600.4 1361.54   603.8 1364.67   620.8 1368.09   657.7 1386.33   670.1  1390.7
   808.8 1398.72   816.5 1400.59   825.4 1403.78   868.7 1413.82   930.8 1423.71
BR U #Mann= 4
       0     .04   546.5     .04   596.2     .04   816.5      .1
BR D #Sta/Elev= 30
       0 1366.81    53.5 1366.74    66.7 1364.93    72.9 1362.25    76.6  1361.8
    93.1 1362.59   102.7 1361.29   106.3 1361.99   123.5 1361.34   166.4 1358.75
   215.2 1361.13   254.8  1361.4   454.6 1372.48   474.6 1370.36   514.7 1360.14
   537.1 1358.63  551.53 1355.39   559.8 1354.69   581.8 1356.89   585.61358.437
   608.7 1366.27   618.8 1366.98   630.9 1366.28   636.4 1367.38   662.6 1378.34
   682.8 1384.41   733.2 1387.85   800.3 1394.53   890.2 1399.61   930.8 1404.99
BR D #Mann= 3
       0     .05   537.1     .04   585.6     .05
BC Design=,, 0 ,, 0 ,,,,,,
BC Use User HTab Curves=0
BC User HTab FreeFlow(D)= 0

Type RM Length L Ch R = 1 ,506     ,506,506,506
XS GIS Cut Line= 6
     1998583.933      245636.922     1998552.683      245352.199
     1998507.544      245105.671     1998479.766       244985.88
     1998450.253      244852.199     1998427.683      244720.255
#Sta/Elev= 30
       0 1366.81    53.5 1366.74    66.7 1364.93    72.9 1362.25    76.6  1361.8
    93.1 1362.59   102.7 1361.29   106.3 1361.99   123.5 1361.34   166.4 1358.75
   215.2 1361.13   254.8  1361.4   454.6 1372.48   474.6 1370.36   514.7 1360.14
   537.1 1358.63  551.53 1355.39   559.8 1354.69   581.8 1356.89   585.61358.437
   608.7 1366.27   618.8 1366.98   630.9 1366.28   636.4 1367.38   662.6 1378.34
   682.8 1384.41   733.2 1387.85   800.3 1394.53   890.2 1399.61   930.8 1404.99
#Mann= 3 ,-1 , 0
       0     .05       0   537.1    .045       0   585.6     .05       0
#XS Ineff= 2 , 0
        476.1667 1383.71651.8333         1385.26
Permanent Ineff=
       F       F
Bank Sta=537.1,585.6
XS Rating Curve= 0 ,0
Exp/Cntr=0.5,0.3
LCMann Table=0

Chan Stop Cuts=-1
Use User Specified Reach Order=0
Composite Channel Slope=5